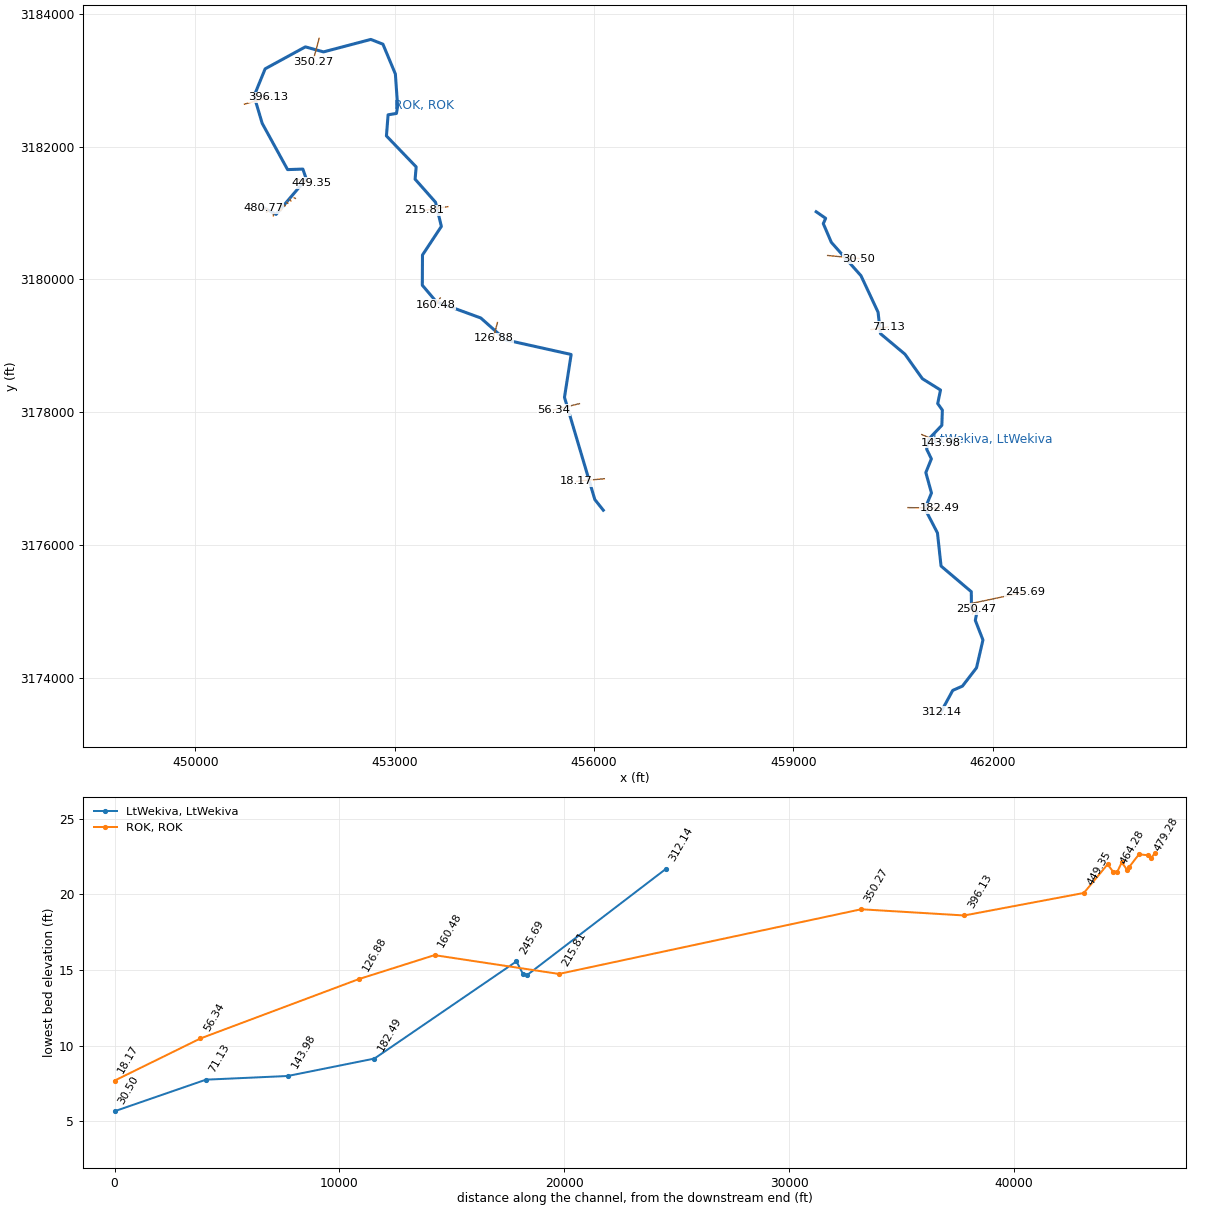
--- wekiva_ras.prj (project) ---

Proj Title=wekiva_ras
Current Plan=p05
Default Exp/Contr=0.3,0.1
English Units
Geom File=g06
Flow File=f03
Plan File=p02
Plan File=p01
Plan File=p03
Plan File=p04
Plan File=p05
Y Axis Title=Elevation
X Axis Title(PF)=Main Channel Distance
X Axis Title(XS)=Station
BEGIN DESCRIPTION:
END DESCRIPTION:
DSS File=dss
DSS Export Rating Curves= 0
DSS Export Rating Curve Sorted= 0
DSS Export Volume Flow Curves= 0
DXF OffsetX= 0
DXF OffsetY= 0
DXF ScaleX= 1
DXF ScaleY= 10
Specific Locations Profile Table=stations                             , 8
LtWekiva        ,LtWekiva        ,312.14
LtWekiva        ,LtWekiva        ,248.51
ROK             ,ROK             ,480.77
ROK             ,ROK             ,126.88
wekiva          ,wek_run         ,793.32
wekiva          ,wekiva_riv_up   ,739.30
wekiva          ,wekiva_riv_down ,405.81
wekiva          ,wekiva_riv_down ,318.86

--- wekiva_ras.p05 (plan) ---

Plan Title=Plan 05
Program Version=5.03
Short Identifier=10
Geom File=g06
Flow File=f03
Subcritical Flow
K Sum by GR= 0
Std Step Tol= 0.01
Critical Tol= 0.01
Num of Std Step Trials= 20
Max Error Tol= 0.3
Flow Tol Ratio= 0.001
Split Flow NTrial= 30
Split Flow Tol= 0.02
Split Flow Ratio= 0.02
Log Output Level= 0
Friction Slope Method= 1
Unsteady Friction Slope Method= 2
Unsteady Bridges Friction Slope Method= 1
Parabolic Critical Depth
Global Vel Dist= 0 , 0 , 0
Global Log Level= 0
CheckData=True
Encroach Param=-1 ,0,0, 0
Computation Interval=1MIN
Output Interval=1HOUR
Instantaneous Interval=1HOUR
Mapping Interval=1HOUR
Run HTab= 0
Run UNet= 0
Run Sediment= 0
Run PostProcess= 0
Run WQNet= 0
Run RASMapper= 0
UNET Theta= 1
UNET Theta Warmup= 1
UNET ZTol= 0.02
UNET ZSATol= 0.02
UNET MxIter= 20
UNET Max Iter WO Improvement= 0
UNET MaxInSteps= 0
UNET DtIC= 0
UNET DtMin= 0
UNET MaxCRTS= 20
UNET WFStab= 2
UNET SFStab= 1
UNET WFX= 1
UNET SFX= 1
UNET DSS MLevel= 4
UNET Pardiso=0
UNET DZMax Abort= 100
UNET Use Existing IB Tables=-1
UNET Froude Reduction=False
UNET Froude Limit= 0.8
UNET Froude Power= 4
UNET Time Slicing=0,0, 5
UNET D1 Cores= 0
UNET D2 Coriolis=0
UNET D2 Cores= 0
UNET D2 Theta= 1
UNET D2 Theta Warmup= 1
UNET D2 Z Tol= 0.01
UNET D2 Volume Tol= 0.01
UNET D2 Max Iterations= 20
UNET D2 Equation= 0
UNET D2 RampUpFraction=0.1
UNET D2 TimeSlices= 1
UNET D2 BCVolumeCheck=0
UNET D1D2 MaxIter= 0
UNET D1D2 ZTol=0.01
UNET D1D2 QTol=0.1
UNET D1D2 MinQTol=1
DSS File=dss
Write IC File= 0
Write IC File at Fixed DateTime=0
Write IC File at Sim End=0
Echo Input=False
Echo Parameters=False
Echo Output=False
Write Detailed= 0
HDF Write Warmup=0
HDF Write Time Slices=0
HDF Flush=0
HDF Face Node Velocities=0
HDF Compression= 1
HDF Chunk Size= 1
HDF Spatial Parts= 1
HDF Use Max Rows=0
HDF Fixed Rows= 1
Calibration Method= 0
Calibration Iterations= 20
Calibration Max Change=0.05
Calibration Tolerance=0.2
Calibration Maximum=1.5
Calibration Minimum=0.5
Calibration Optimization Method= 1
WQ AD Non Conservative
WQ ULTIMATE=-1
WQ Max Comp Step=1HOUR
WQ Output Interval=15MIN
WQ Output Selected Increments= 0
WQ Output face flow=0
WQ Output face velocity=0
WQ Output face area=0
WQ Output face dispersion=0
WQ Output cell volume=0
WQ Output cell surface area=0
WQ Output cell continuity=0
WQ Output cumulative cell continuity=0
WQ Output face conc=0
WQ Output face dconc_dx=0
WQ Output face courant=0
WQ Output face peclet=0
WQ Output face adv mass=0
WQ Output face disp mass=0
WQ Output cell mass=0
WQ Output cell source sink temp=0
WQ Output nsm pathways=0
WQ Output nsm derived pathways=0
WQ Output MaxMinRange=-1
WQ Daily Max Min Mean=-1
WQ Daily Range=0
WQ Daily Time=0
WQ Create Restart=0
WQ Fixed Restart=0
WQ System Summary=0
WQ Write To DSS=0
WQ Use Fixed Temperature=0
Sorting and Armoring Iterations= 10
XS Update Threshold= 0.02
Bed Roughness Predictor= 0
Hydraulics Update Threshold= 0.02
Energy Slope Method= 1
Volume Change Method= 1
Sediment Retention Method= 0
XS Weighting Method= 0
Number of US Weighted Cross Sections= 1
Number of DS Weighted Cross Sections= 1
Upstream XS Weight=0
Main XS Weight=1
Downstream XS Weight=0
Number of DS XS's Weighted with US Boundary= 1
Upstream Boundary Weight= 1
Weight of XSs Associated with US Boundary= 0
Number of US XS's Weighted with DS Boundary= 1
Downstream Boundary Weight= 0.5
Weight of XSs Associated with DS Boundary= 0.5
Percentile Method= 0
Sediment Output Level= 4
Mass or Volume Output= 0
Output Increment Type= 1
Profile and TS Output Increment= 1
XS Output Flag= 0
XS Output Increment= 10
Write Gradation File= 0
Read Gradation Hotstart= 0
Write HDF5 File= 1
Write DSS Sediment File= 0
SV Curve= 0
Specific Gage Flag= 0

--- wekiva_ras.p01 (plan) ---

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Plan Title=Plan 01
Short Identifier=Plan 01
Geom File=g01
Flow File=f03

--- wekiva_ras.p02 (plan) ---

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Plan Title=Plan 02
Short Identifier=t3
Geom File=g05
Flow File=f03

--- wekiva_ras.p03 (plan) ---

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Plan Title=Plan 03
Short Identifier=r021
Geom File=g02
Flow File=f03

--- wekiva_ras.p04 (plan) ---

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Plan Title=Plan 04
Short Identifier=Plan 04
Geom File=g03
Flow File=f03

--- wekiva_ras.f03 (steady flow) ---

Flow Title=Flow 03
Program Version=5.03
Number of Profiles= 13
Profile Names=PF 1,PF 2,PF 3,PF 4,PF 5,PF 6,PF 7,PF 8,PF 9,PF 10,PF 11,PF 12,PF 13
River Rch & RM=LtWekiva,LtWekiva        ,312.14
     .87      .4    5.33    14.1    20.5    44.8    80.3    64.8     279     295
     340     269     536
River Rch & RM=LtWekiva,LtWekiva        ,245.69
   28.24   26.78   35.07   49.79   65.03   84.62  123.17  105.62  319.49  335.65
   382.4  310.12  585.67
River Rch & RM=LtWekiva,LtWekiva        ,182.49
   28.59   27.13   35.46   50.36   65.85  101.12  124.64  107.23  326.02  345.44
   398.4  316.17  648.79
River Rch & RM=LtWekiva,LtWekiva        ,30.50
   30.72   31.37   35.71   50.52   61.86  129.08  209.37  137.68   313.2  374.29
  437.52  438.08 1009.91
River Rch & RM=ROK,ROK             ,480.77
   47.09   46.24   48.38   49.15   56.58   51.01   57.32   58.77   59.58   59.66
   57.34   59.69   73.21
River Rch & RM=ROK,ROK             ,350.27
   47.09   46.24   48.38   50.26   58.48      58   62.91   63.73   69.04   70.14
   71.24   71.65  115.42
River Rch & RM=ROK,ROK             ,215.81
   49.31    48.3   51.23   52.82   65.04   68.42   70.36    73.8   77.43   81.81
   82.52   83.88  207.52
River Rch & RM=ROK,ROK             ,18.17
    52.3   54.72   55.89   61.67   71.81  131.41   94.41  130.43  148.37  183.82
  179.37  214.39  430.34
River Rch & RM=wekiva,wek_run         ,793.32
   50.49   50.23   52.19   54.43    63.3   59.48   65.09   54.97   58.93   59.98
    57.3   59.35      58
River Rch & RM=wekiva,wekiva_riv_up   ,747.19
  102.95  105.16  108.18  117.41   136.9  205.64     164  189.47  212.15  253.65
  248.22     281  535.53
River Rch & RM=wekiva,wekiva_riv_up   ,579.74
  106.51  111.72   114.1  120.43  137.05  255.07  203.39  277.94   258.9  317.58
  348.02  371.32  571.98
River Rch & RM=wekiva,wekiva_riv_down ,544.57
  137.22  143.08  149.81  170.96   198.9  384.15  412.76  415.61  572.09  691.87
  785.54  809.39 1581.89
River Rch & RM=wekiva,wekiva_riv_down ,477.90
     139  144.36  152.69  183.62  210.07  391.46  449.06  461.99  647.52  778.65
  906.07  907.78 1709.58
River Rch & RM=wekiva,wekiva_riv_down ,386.11
     150     155     164  195.33  223.89  403.89  463.76  476.43  661.91  793.14
  919.73  922.28 1724.18
River Rch & RM=wekiva,wekiva_riv_down ,333.01
     150     155     164     196     225     407     467     479     665     797
     922     927    1740
River Rch & RM=wekiva,wekiva_riv_down ,143.23
  164.18  169.55  179.02  233.29  258.73  395.52  515.01  550.61  661.51  833.27
   899.7  988.06 1842.51
River Rch & RM=wekiva,wekiva_riv_down ,25.630*
  215.86   218.8  233.25  315.37  455.56  565.43  842.59  803.89   927.4 1115.52
 1326.81  1284.9 3163.88
Boundary for River Rch & Prof#=LtWekiva,LtWekiva        , 1
Up Type= 0
Dn Type= 0
Boundary for River Rch & Prof#=LtWekiva,LtWekiva        , 2
Up Type= 0
Dn Type= 0
Boundary for River Rch & Prof#=LtWekiva,LtWekiva        , 3
Up Type= 0
Dn Type= 0
Boundary for River Rch & Prof#=LtWekiva,LtWekiva        , 4
Up Type= 0
Dn Type= 0
Boundary for River Rch & Prof#=LtWekiva,LtWekiva        , 5
Up Type= 0
Dn Type= 0
Boundary for River Rch & Prof#=LtWekiva,LtWekiva        , 6
Up Type= 0
Dn Type= 0
Boundary for River Rch & Prof#=LtWekiva,LtWekiva        , 7
Up Type= 0
Dn Type= 0
Boundary for River Rch & Prof#=LtWekiva,LtWekiva        , 8
Up Type= 0
Dn Type= 0
Boundary for River Rch & Prof#=LtWekiva,LtWekiva        , 9
Up Type= 0
Dn Type= 0
Boundary for River Rch & Prof#=LtWekiva,LtWekiva        , 10
Up Type= 0
Dn Type= 0
Boundary for River Rch & Prof#=LtWekiva,LtWekiva        , 11
Up Type= 0
Dn Type= 0
Boundary for River Rch & Prof#=LtWekiva,LtWekiva        , 12
Up Type= 0
Dn Type= 0
Boundary for River Rch & Prof#=LtWekiva,LtWekiva        , 13
Up Type= 0
Dn Type= 0
Boundary for River Rch & Prof#=ROK,ROK             , 1
Up Type= 0
Dn Type= 0
Boundary for River Rch & Prof#=ROK,ROK             , 2
Up Type= 0
Dn Type= 0
Boundary for River Rch & Prof#=ROK,ROK             , 3
Up Type= 0
Dn Type= 0
Boundary for River Rch & Prof#=ROK,ROK             , 4
Up Type= 0
Dn Type= 0
Boundary for River Rch & Prof#=ROK,ROK             , 5
Up Type= 0
Dn Type= 0
Boundary for River Rch & Prof#=ROK,ROK             , 6
Up Type= 0
Dn Type= 0
Boundary for River Rch & Prof#=ROK,ROK             , 7
Up Type= 0
Dn Type= 0
Boundary for River Rch & Prof#=ROK,ROK             , 8
Up Type= 0
Dn Type= 0
Boundary for River Rch & Prof#=ROK,ROK             , 9
Up Type= 0
Dn Type= 0
Boundary for River Rch & Prof#=ROK,ROK             , 10
Up Type= 0
Dn Type= 0
Boundary for River Rch & Prof#=ROK,ROK             , 11
Up Type= 0
Dn Type= 0
Boundary for River Rch & Prof#=ROK,ROK             , 12
Up Type= 0
Dn Type= 0
Boundary for River Rch & Prof#=ROK,ROK             , 13
Up Type= 0
Dn Type= 0
Boundary for River Rch & Prof#=wekiva,wek_run         , 1
Up Type= 0
Dn Type= 0
Boundary for River Rch & Prof#=wekiva,wek_run         , 2
Up Type= 0
Dn Type= 0
Boundary for River Rch & Prof#=wekiva,wek_run         , 3
Up Type= 0
Dn Type= 0
Boundary for River Rch & Prof#=wekiva,wek_run         , 4
Up Type= 0
Dn Type= 0
Boundary for River Rch & Prof#=wekiva,wek_run         , 5
Up Type= 0
Dn Type= 0
Boundary for River Rch & Prof#=wekiva,wek_run         , 6
Up Type= 0
Dn Type= 0
Boundary for River Rch & Prof#=wekiva,wek_run         , 7
Up Type= 0
Dn Type= 0
Boundary for River Rch & Prof#=wekiva,wek_run         , 8
Up Type= 0
Dn Type= 0
Boundary for River Rch & Prof#=wekiva,wek_run         , 9
Up Type= 0
Dn Type= 0
Boundary for River Rch & Prof#=wekiva,wek_run         , 10
Up Type= 0
Dn Type= 0
Boundary for River Rch & Prof#=wekiva,wek_run         , 11
Up Type= 0
Dn Type= 0
Boundary for River Rch & Prof#=wekiva,wek_run         , 12
Up Type= 0
Dn Type= 0
Boundary for River Rch & Prof#=wekiva,wek_run         , 13
Up Type= 0
Dn Type= 0
Boundary for River Rch & Prof#=wekiva,wekiva_riv_up   , 1
Up Type= 0
Dn Type= 0
Boundary for River Rch & Prof#=wekiva,wekiva_riv_up   , 2
Up Type= 0
Dn Type= 0
Boundary for River Rch & Prof#=wekiva,wekiva_riv_up   , 3
Up Type= 0
Dn Type= 0
Boundary for River Rch & Prof#=wekiva,wekiva_riv_up   , 4
Up Type= 0
Dn Type= 0
Boundary for River Rch & Prof#=wekiva,wekiva_riv_up   , 5
Up Type= 0
Dn Type= 0
Boundary for River Rch & Prof#=wekiva,wekiva_riv_up   , 6
Up Type= 0
Dn Type= 0
Boundary for River Rch & Prof#=wekiva,wekiva_riv_up   , 7
Up Type= 0
Dn Type= 0
Boundary for River Rch & Prof#=wekiva,wekiva_riv_up   , 8
Up Type= 0
Dn Type= 0
Boundary for River Rch & Prof#=wekiva,wekiva_riv_up   , 9
Up Type= 0
Dn Type= 0
Boundary for River Rch & Prof#=wekiva,wekiva_riv_up   , 10
Up Type= 0
Dn Type= 0
Boundary for River Rch & Prof#=wekiva,wekiva_riv_up   , 11
Up Type= 0
Dn Type= 0
Boundary for River Rch & Prof#=wekiva,wekiva_riv_up   , 12
Up Type= 0
Dn Type= 0
Boundary for River Rch & Prof#=wekiva,wekiva_riv_up   , 13
Up Type= 0
Dn Type= 0
Boundary for River Rch & Prof#=wekiva,wekiva_riv_down , 1
Up Type= 0
Dn Type= 1
Dn Known WS=-0.03
Boundary for River Rch & Prof#=wekiva,wekiva_riv_down , 2
Up Type= 0
Dn Type= 1
Dn Known WS=-0.14
Boundary for River Rch & Prof#=wekiva,wekiva_riv_down , 3
Up Type= 0
Dn Type= 1
Dn Known WS=0.01
Boundary for River Rch & Prof#=wekiva,wekiva_riv_down , 4
Up Type= 0
Dn Type= 1
Dn Known WS=0.91
Boundary for River Rch & Prof#=wekiva,wekiva_riv_down , 5
Up Type= 0
Dn Type= 1
Dn Known WS=1.55
Boundary for River Rch & Prof#=wekiva,wekiva_riv_down , 6
Up Type= 0
Dn Type= 1
Dn Known WS=1.31
Boundary for River Rch & Prof#=wekiva,wekiva_riv_down , 7
Up Type= 0
Dn Type= 1
Dn Known WS=1.89
Boundary for River Rch & Prof#=wekiva,wekiva_riv_down , 8
Up Type= 0
Dn Type= 1
Dn Known WS=2.93
Boundary for River Rch & Prof#=wekiva,wekiva_riv_down , 9
Up Type= 0
Dn Type= 1
Dn Known WS=3.17
Boundary for River Rch & Prof#=wekiva,wekiva_riv_down , 10
Up Type= 0
Dn Type= 1
Dn Known WS=3.33
Boundary for River Rch & Prof#=wekiva,wekiva_riv_down , 11
Up Type= 0
Dn Type= 1
Dn Known WS=2.22
Boundary for River Rch & Prof#=wekiva,wekiva_riv_down , 12
Up Type= 0
Dn Type= 1
Dn Known WS=3.49
Boundary for River Rch & Prof#=wekiva,wekiva_riv_down , 13
Up Type= 0
Dn Type= 1
Dn Known WS=4.51
DSS Import GetInterval= 0
DSS Import GetPeak= 0
DSS Import FillOption= 0

--- wekiva_ras.g06 (geometry) ---

Geom Title=wekiva_ras_2018_ft_10
Program Version=5.03

Junct Name=Junc_LtWek
Junct Desc=, 0 , 0 ,-1 ,0
Up River,Reach=LtWekiva        ,LtWekiva
Up River,Reach=wekiva          ,wekiva_riv_up
Dn River,Reach=wekiva          ,wekiva_riv_down
Junc L&A=0,0
Junc L&A=0,0

Junct Name=Junc_Rok
Junct Desc=, 0 , 0 ,-1 ,0
Up River,Reach=ROK             ,ROK
Up River,Reach=wekiva          ,wek_run
Dn River,Reach=wekiva          ,wekiva_riv_up
Junc L&A=0,0
Junc L&A=0,0

River Reach=LtWekiva        ,LtWekiva
Reach XY= 30
 461210.722404883173468.02397002461399.0711048793173813.90187002
 461544.923404883173878.29017002 461756.951404883174153.97287002
 461853.759004883174572.90287002461738.7675048793174868.43627002
 461763.894404883174995.06247002 461680.720004883175051.39747002
461678.4189048793175299.57177002461223.1042048793175685.60017002
 461168.883004883176184.43507002 460980.871804883176547.67637002
 461078.951904883176785.36127002460994.0494048793177093.09957002
 461077.364904883177299.00777002461005.9516048793177446.19837002
 461043.245204883177602.24967002 461235.178304883177804.45507002
 461242.721704883178033.17637002461172.4933048793178132.16257002
 461215.341304883178335.29367002 460941.987104883178505.89197002
460679.7417048793178874.86057002460311.0410048793179183.65647002
 460274.997604883179507.23687002 460017.978804883180055.95667002
459571.6459048793180558.36217002 459450.507804883180840.31237002
459486.1704048793180920.25557002 459343.436962483181018.99032073

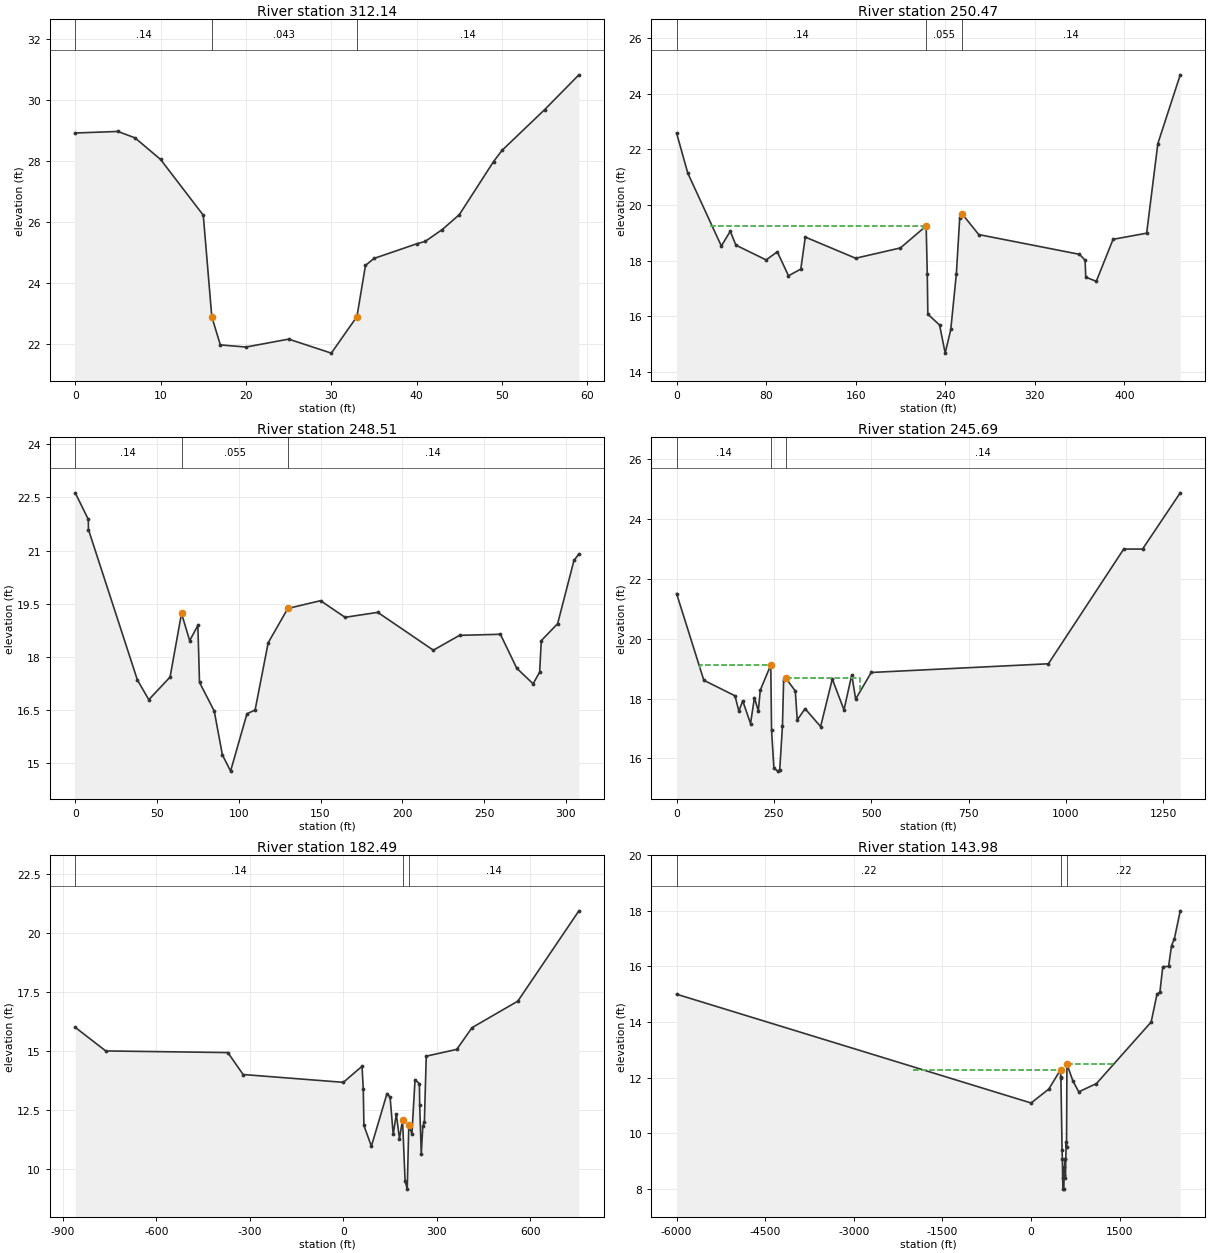
Type RM Length L Ch R = 1 ,312.14  ,6167.191,6167.191,6167.191
BEGIN DESCRIPTION:
TheSprings
END DESCRIPTION:
Node Name=TheSprings
XS GIS Cut Line= 2
461204.5570048793173492.65727002461225.0887048793173489.69387002
#Sta/Elev= 21
       0   28.92       5   28.97       7   28.76      10   28.05      15   26.22
      16   22.88      17   21.96      20   21.89      25   22.15      30   21.69
      33   22.89      34   24.57      35    24.8      40   25.28      41   25.36
      43   25.75      45   26.24      49   27.98      50   28.35      55   29.69
      59   30.83
#Mann= 3 , 0 , 0
       0     .14       0      16    .043       0      33     .14       0
Bank Sta=16,33
XS Rating Curve= 0 ,0
Exp/Cntr=0.3,0.1

Type RM Length L Ch R = 1 ,250.47  ,195.8661,195.8661,195.8661
BEGIN DESCRIPTION:
MFL_SLB_south
END DESCRIPTION:
Node Name=MFL_SLB_south
XS GIS Cut Line= 2
 461695.722804883174963.91247002461744.7818048793175039.17377002
#Sta/Elev= 30
       0  22.582      10  21.142      40  18.522      48  19.052      53  18.552
      80  18.022      90  18.312     100  17.452     111  17.692     115  18.842
     160  18.082     200  18.452     223  19.242     224  17.512   224.5  16.072
     235  15.682     240  14.672     245  15.522     250  17.532     253  19.542
     255  19.682     270  18.932     360  18.222     365  18.012   365.6  17.402
     375  17.252     390  18.762     420  18.982     430  22.202     450  24.672
#Mann= 3 , 0 , 0
       0     .14       0     223    .055       0     255     .14       0
#XS Ineff= 2 ,-1
      30     220   19.24     255     425   19.68
Permanent Ineff=
       F       F
Bank Sta=223,255
XS Rating Curve= 0 ,0
Exp/Cntr=0.3,0.1

Type RM Length L Ch R = 1 ,248.51  ,282.3819,282.3819,282.3819
BEGIN DESCRIPTION:
MFL_SLB_bridge
END DESCRIPTION:
Node Name=MFL_SLB_bridge
XS GIS Cut Line= 2
461657.0487048793175034.72957002461736.0472048793175081.44547002
#Sta/Elev= 30
       0  22.632       8  21.882     8.1  21.592      38  17.342      45  16.782
      58  17.422      65  19.222      70  18.452      75  18.882      76  17.272
      85  16.462      90  15.222      95  14.762     105  16.382     110  16.492
     118  18.392     130  19.362     150  19.582     165  19.112     185  19.252
     219  18.182     235  18.602     260  18.632     270  17.672     280  17.232
     284  17.562     285  18.452     295  18.932     305  20.722     308  20.902
#Mann= 3 , 0 , 0
       0     .14       0      65    .055       0     130     .14       0
#XS Ineff= 2 ,-1
      20      65   19.22     130     300   19.36
Permanent Ineff=
       F       F
Bank Sta=65,130
XS Rating Curve= 0 ,0
Exp/Cntr=0.3,0.1

Type RM Length L Ch R = 1 ,245.69  ,6319.948,6319.948,6319.948
BEGIN DESCRIPTION:
MFL_SLB_north
END DESCRIPTION:
Node Name=MFL_SLB_north
XS GIS Cut Line= 3
461616.7210048793175109.23877002 461714.682104883175129.98127002
462481.3654001193175292.32048682
#Sta/Elev= 30
       0  21.512      70  18.612     150  18.092     160  17.582     170  17.922
     190  17.162     200  18.032     210  17.582     215  18.282     242  19.122
     244  16.932     250  15.672     260  15.572     265  15.622     272  17.092
     275  18.622     280  18.692     305  18.252     310  17.282     330  17.662
     370  17.062     400  18.652     430  17.622     450  18.792     460  17.982
     500  18.872954.9455 19.16271148.509      23  1196.9      231293.682 24.8808
#Mann= 3 , 0 , 0
       0     .14       0     242    .055       0     280     .14       0
#XS Ineff= 2 ,-1
      60     242   19.12     280     470   18.69
Permanent Ineff=
       F       F
Bank Sta=242,280
XS Rating Curve= 0 ,0
Exp/Cntr=0.3,0.1

Type RM Length L Ch R = 1 ,182.49  ,3850.361,3850.361,3850.361
BEGIN DESCRIPTION:
MFL_Sabol
MFL_Sabol
END DESCRIPTION:
Node Name=MFL_Sabol
XS GIS Cut Line= 2
 460724.291904883176565.62067002 461198.426104883176557.15397002
#Sta/Elev= 30
-860.094      16-762.169      15-370.471 14.9302-321.509      14       0  13.668
      60  14.348      64  13.378      66  11.838      90  10.958     140  13.188
     150  13.038     160  11.458     170  12.328     180  11.278     190  12.078
     198   9.498     205   9.138     210  11.838     220  11.488     230  13.768
     244  13.618     245  12.688     250  10.618     255  11.818     260  11.988
     266  14.778363.9624 15.0659412.9247 15.9882559.8115 17.1129755.6606 20.9429
#Mann= 3 , 0 , 0
-860.094     .14       0     190    .055       0     210     .14       0
#XS Ineff= 1 ,-1
      64     120   12.08
Permanent Ineff=
       F
Bank Sta=190,210
XS Rating Curve= 0 ,0
Exp/Cntr=0.3,0.1

Type RM Length L Ch R = 1 ,143.98  ,3642.73,3642.73,3642.73
BEGIN DESCRIPTION:
LW2
END DESCRIPTION:
Node Name=LW2
XS GIS Cut Line= 2
 460933.299004883177665.03007002461212.6995048793177544.37987002
#Sta/Elev= 30
   -6000      15       0  11.086     300  11.586     500  12.286   501.5  12.006
     505  11.986     525   9.386     530   9.086     535   8.386     540   7.986
     555   7.986     560   8.786     565   8.486     570   9.086     575   9.086
     580   8.386     595   9.686     600   9.486     607  12.486     707  11.886
     807  11.486    1107  11.7862032.791      142131.163      152180.349  15.072
2229.535 15.99112327.908      162377.094 16.7483 2426.28      172524.652      18
#Mann= 3 , 0 , 0
   -6000     .22       0     500      .2       0     607     .22       0
#XS Ineff= 2 ,-1
   -2000     500   12.29     607    1400   12.49
Permanent Ineff=
       F       F
Bank Sta=500,607
XS Rating Curve= 0 ,0
Vertical n Elevations= 5
      30      48      70     120     640
Vertical n for Station=-6000
     .22     .22     .22     .22     .22
Vertical n for Station=500
      .2    .155    .127    .109    .091
Vertical n for Station=607
     .22     .22     .22     .22     .22
Vertical n Flow=-1
Exp/Cntr=0.3,0.1

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
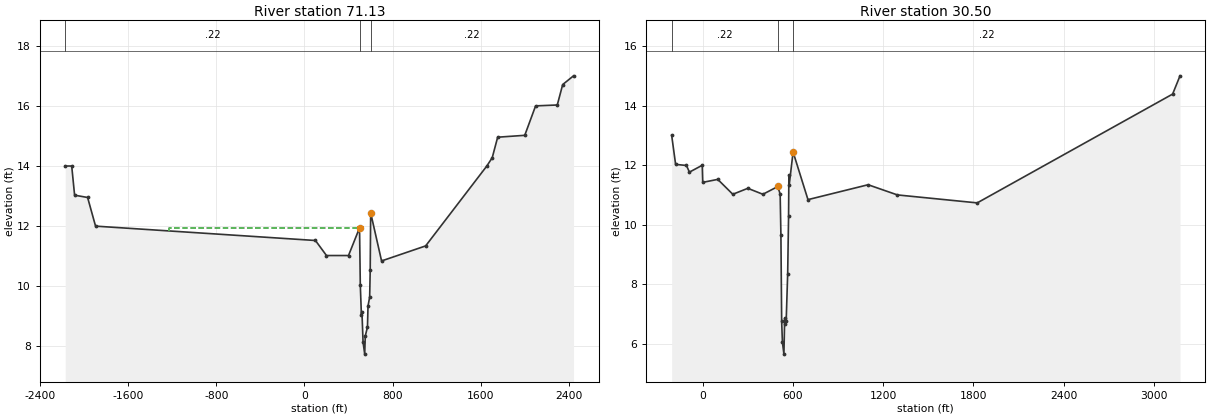
Type RM Length L Ch R = 1 ,71.13   ,4063.156,4063.156,4063.156
BEGIN DESCRIPTION:
LW1
END DESCRIPTION:
Node Name=LW1
XS GIS Cut Line= 2
460177.6475048793179246.18327002 460425.298004883179284.28337002
#Sta/Elev= 30
-2170.99      14-2111.97      14-2085.74 13.0294-1967.72 12.9532-1895.59      12
     100  11.522     200  11.022     400  11.022     500  11.942     507  10.042
     517   9.042     522   9.142     532   8.142     547   7.742     552   8.342
     572   8.642     577   9.342     592   9.642     597  10.542     601  12.442
     700  10.842    1100  11.3421655.207      141704.387 14.27811753.567 14.9583
1999.466 15.02082097.825      162294.545 16.02972343.725 16.70992442.084      17
#Mann= 3 , 0 , 0
-2170.99     .22       0     500      .2       0     601     .22       0
#XS Ineff= 2 ,-1
-1226.79     500   11.94     601    1350   12.44
Permanent Ineff=
       F       F
Bank Sta=500,601
XS Rating Curve= 0 ,0
Vertical n Elevations= 5
      30      50      70     140    1020
Vertical n for Station=-2170.99
     .22     .22     .22     .22     .22
Vertical n for Station=500
      .2    .155    .127    .109    .091
Vertical n for Station=601
     .22     .22     .22     .22     .22
Vertical n Flow=-1
Exp/Cntr=0.3,0.1

Type RM Length L Ch R = 1 ,30.50   ,3049.836,3049.836,3049.836
BEGIN DESCRIPTION:
WK18
END DESCRIPTION:
Node Name=WK18
XS GIS Cut Line= 2
 459515.919704883180360.70577002 459987.937304883180315.19737002
#Sta/Elev= 30
 -206.62      13 -180.39 12.0255-108.269 11.9891-88.6005  11.765 -3.3673 11.9961
       0  11.422     100  11.522     200  11.022     300  11.222     400  11.022
     500  11.283     515  11.023     520   9.653     525   6.753     530   6.053
     540   5.653     545   6.853     550   6.653     555   6.753     565   8.353
     571  10.293     573  11.663     575  11.323     601  12.442     700  10.842
    1100  11.3421294.801      111825.869 10.7326 3125.62 14.38723174.641      15
#Mann= 3 , 0 , 0
 -206.62     .22       0     500      .2       0     601     .22       0
#XS Ineff= 2 ,-1
     100     500   11.28     601    2450   12.44
Permanent Ineff=
       F       F
Bank Sta=500,601
XS Rating Curve= 0 ,0
Vertical n Elevations= 5
      30      50      70     140    1020
Vertical n for Station=-206.62
     .22     .22     .22     .22     .22
Vertical n for Station=500
      .2    .155    .127    .109    .091
Vertical n for Station=601
     .22     .22     .22     .22     .22
Vertical n Flow=-1
Exp/Cntr=0.3,0.1

River Reach=ROK             ,ROK
Reach XY= 30
 451023.213404883181083.14707002 451213.005804883180978.54017002
451667.4719048793181512.95497002451616.6891048793181661.33587002
 451386.579704883181653.40107002 451004.122004883182350.07717002
450881.9259048793182761.10017002451048.6541048793183170.39177002
 451654.178504883183501.00377002451927.1358048793183425.22637002
452639.4171048793183613.01687002 452821.763304883183541.14077002
453009.2232048793183092.49347002453042.9461048793182603.84157002
 453025.092804883182498.70537002452899.4583048793182478.53767002
 452874.331504883182160.48417002453321.9868048793181694.31427002
453306.1172048793181509.16877002 453613.921704883181161.35967002
 453701.204604883180798.34217002453417.2045048793180367.87887002
453414.5596048793179912.94997002 453624.832004883179664.78887002
 454294.638804883179419.86777002 454666.170704883179090.68087002
455655.0262048793178870.54787002 455554.633404883178225.81147002
 456011.347704883176686.76737002456138.8371248563176526.33636962

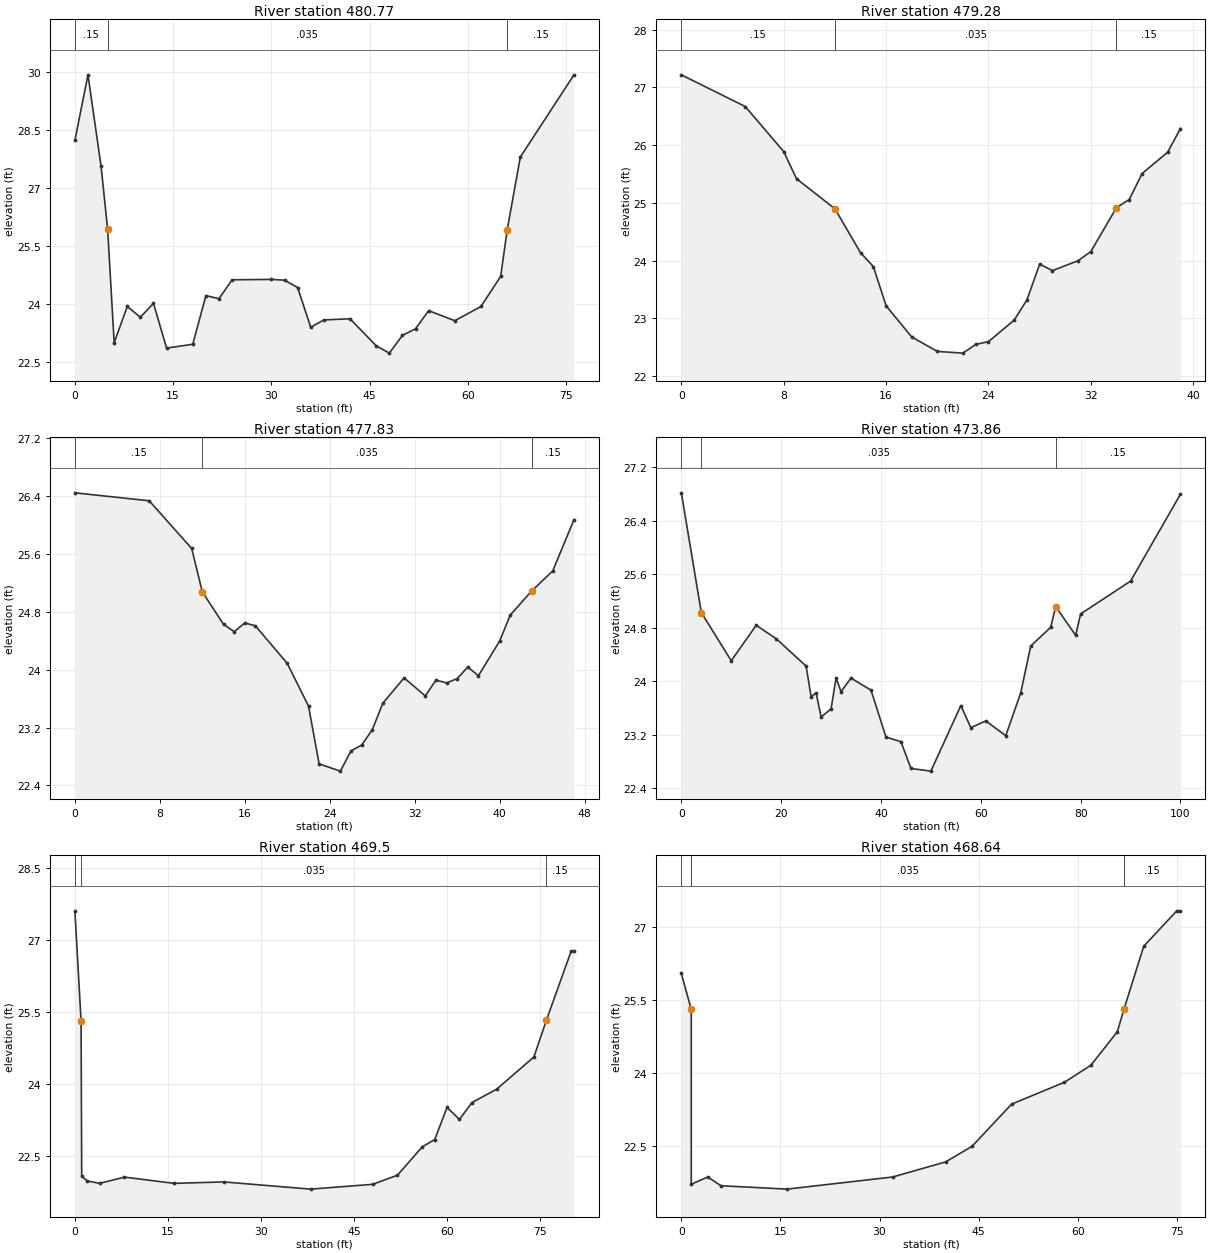
Type RM Length L Ch R = 1 ,480.77  ,149.0814,149.0814,149.0814
BEGIN DESCRIPTION:
RokSpr02
END DESCRIPTION:
Node Name=RokSpr02
XS GIS Cut Line= 2
451026.6781048793181095.07657002451022.5373048793181071.37427002
#Sta/Elev= 30
       0  28.228       2  29.928       4  27.558       5  25.928       6  22.988
       8  23.928      10  23.648      12  24.008      14  22.848      18  22.948
      20  24.208      22  24.128      24  24.618      30  24.628      32  24.608
      34  24.418      36  23.388      38  23.578      42  23.608      46  22.908
      48  22.718      50  23.178      52  23.348      54  23.818      58  23.558
      62  23.928      65  24.708      66  25.918      68  27.798   76.19  29.928
#Mann= 3 , 0 , 0
       0     .15       0       5    .035       0      66     .15       0
Bank Sta=5,66
XS Rating Curve= 0 ,0
Exp/Cntr=0.3,0.1

Type RM Length L Ch R = 1 ,479.28  ,145.1115,145.1115,145.1115
BEGIN DESCRIPTION:
RokSpr03
END DESCRIPTION:
Node Name=RokSpr03
XS GIS Cut Line= 2
451082.3677048793181066.28987002451051.4643048793181054.43647002
#Sta/Elev= 24
       0  27.218       5  26.668       8  25.888       9  25.418      12  24.898
      14  24.138      15  23.898      16  23.218      18  22.678      20  22.428
      22  22.398      23  22.548      24  22.598      26  22.968      27  23.318
      28  23.938      29  23.828      31  23.998      32  24.158      34  24.918
      35  25.058      36  25.508      38  25.878      39  26.288
#Mann= 3 , 0 , 0
       0     .15       0      12    .035       0      34     .15       0
Bank Sta=12,34
XS Rating Curve= 0 ,0
Exp/Cntr=0.3,0.1

Type RM Length L Ch R = 1 ,477.83  ,396.8176,396.8176,396.8176
BEGIN DESCRIPTION:
RokSpr04
END DESCRIPTION:
Node Name=RokSpr04
XS GIS Cut Line= 2
 451097.184404883181024.59137002 451068.609404883181013.79637002
#Sta/Elev= 28
       0  26.448       7  26.338      11  25.678      12  25.078      14  24.628
      15  24.528      16  24.648      17  24.608      20  24.088      22  23.498
      23  22.698      25  22.598      26  22.878      27  22.958      28  23.168
      29  23.538      31  23.888      33  23.638      34  23.858      35  23.818
      36  23.878      37  24.038      38  23.918      40  24.398      41  24.758
      43  25.088      45  25.368      47  26.078
#Mann= 3 , 0 , 0
       0     .15       0      12    .035       0      43     .15       0
Bank Sta=12,43
XS Rating Curve= 0 ,0
Exp/Cntr=0.3,0.1

Type RM Length L Ch R = 1 ,473.86  ,436.3189,436.3189,436.3189
BEGIN DESCRIPTION:
RokSpr05
END DESCRIPTION:
Node Name=RokSpr05
XS GIS Cut Line= 2
451175.4950048793180987.69237002451172.3109048793180957.39027002
#Sta/Elev= 30
       0  26.818       4  25.028      10  24.308      15  24.838      19  24.638
      25  24.228      26  23.768      27  23.828      28  23.468      30  23.588
      31  24.048      32  23.848      34  24.048      38  23.868      41  23.168
      44  23.098      46  22.698      50  22.658      56  23.638      58  23.308
      61  23.408      65  23.188      68  23.828      70  24.528      74  24.808
      75  25.118      79  24.688      80  25.008      90  25.498     100  26.798
#Mann= 3 , 0 , 0
       0     .15       0       4    .035       0      75     .15       0
Bank Sta=4,75
XS Rating Curve= 0 ,0
Exp/Cntr=0.3,0.1

Type RM Length L Ch R = 1 ,469.5   ,86.1877,86.1877,86.1877
BEGIN DESCRIPTION:
RokSpr08
END DESCRIPTION:
Node Name=RokSpr08
XS GIS Cut Line= 2
 451256.572004883181058.88917002451286.3376048793181034.67977002
#Sta/Elev= 21
       0  27.608       1  25.318     1.1  22.088       2  21.988       4  21.938
       8  22.068      16  21.938      24  21.968      38  21.818      48  21.918
      52  22.108      56  22.698      58  22.848      60  23.518      62  23.268
      64  23.618      68  23.898      74  24.568      76  25.328      80  26.768
   80.46  26.768
#Mann= 3 , 0 , 0
       0     .15       0       1    .035       0      76     .15       0
Bank Sta=1,76
XS Rating Curve= 0 ,0
Exp/Cntr=0.3,0.1

Type RM Length L Ch R = 1 ,468.64  ,242.6181,242.6181,242.6181
BEGIN DESCRIPTION:
RokSpr09
END DESCRIPTION:
Node Name=RokSpr09
XS GIS Cut Line= 2
 451276.415704883181079.12987002 451298.510204883181052.33677002
#Sta/Elev= 17
       0  26.048     1.5  25.308     1.5  21.708       4  21.858       6  21.678
      16  21.608      32  21.858      40  22.168      44  22.488      50  23.358
      58  23.808      62  24.158      66  24.848      67  25.308      70  26.608
      75  27.338   75.56  27.338
#Mann= 3 , 0 , 0
       0     .15       0     1.5    .035       0      67     .15       0
Bank Sta=1.5,67
XS Rating Curve= 0 ,0
Exp/Cntr=0.3,0.1

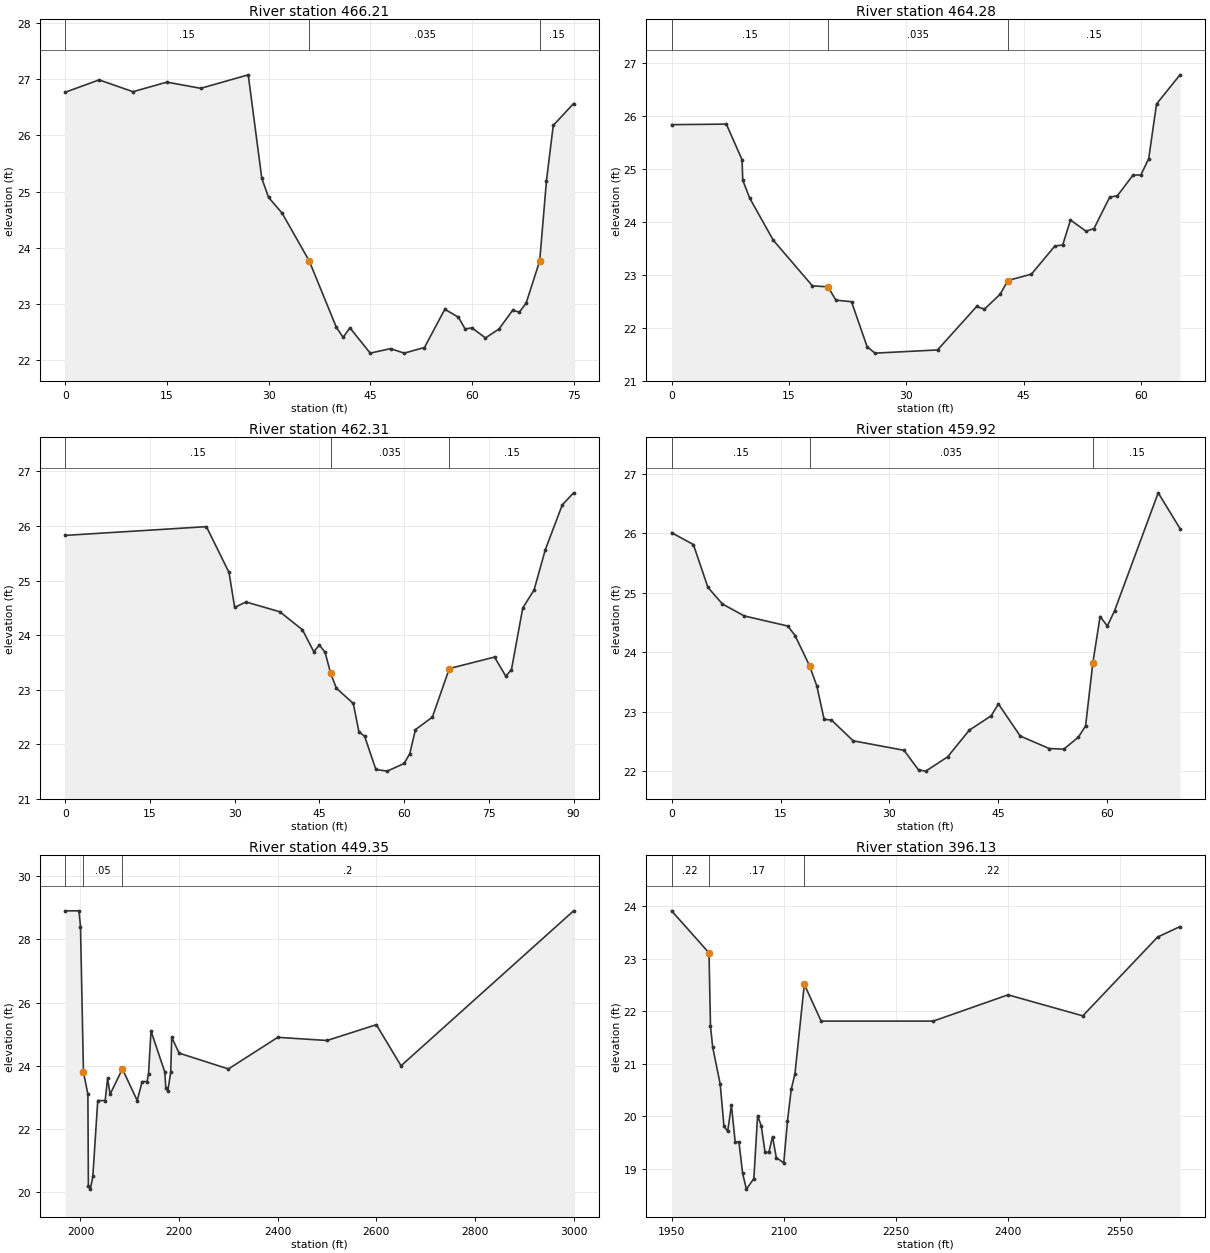
Type RM Length L Ch R = 1 ,466.21  ,193.2415,193.2415,193.2415
BEGIN DESCRIPTION:
RokSpr11
END DESCRIPTION:
Node Name=RokSpr11
XS GIS Cut Line= 2
451331.5027048793181121.98737002 451349.007504883181107.29797002
#Sta/Elev= 30
       0  26.768       5  26.988      10  26.778      15  26.948      20  26.838
      27  27.078      29  25.238      30  24.898      32  24.618      36  23.768
      40  22.588      41  22.408      42  22.578      45  22.128      48  22.208
      50  22.128      53  22.228      56  22.908      58  22.768      59  22.558
      60  22.578      62  22.398      64  22.558      66  22.888      67  22.858
      68  23.018      70  23.768      71  25.198      72  26.178      75  26.568
#Mann= 3 , 0 , 0
       0     .15       0      36    .035       0      70     .15       0
Bank Sta=36,70
XS Rating Curve= 0 ,0
Exp/Cntr=0.3,0.1

Type RM Length L Ch R = 1 ,464.28  ,196.4567,196.4567,196.4567
BEGIN DESCRIPTION:
RokSpr12
END DESCRIPTION:
Node Name=RokSpr12
XS GIS Cut Line= 2
 451376.887304883181161.36027002 451390.891104883181147.35337002
#Sta/Elev= 30
       0  25.828       7  25.838       9  25.168     9.1  24.778      10  24.438
      13  23.648      18  22.788      20  22.768      21  22.518      23  22.488
      25  21.638      26  21.518      34  21.578      39  22.398      40  22.348
      42  22.628      43  22.888      46  23.008      49  23.538      50  23.558
      51  24.028      53  23.818      54  23.868      56  24.458      57  24.488
      59  24.878      60  24.878      61  25.188      62  26.218      65  26.768
#Mann= 3 , 0 , 0
       0     .15       0      20    .035       0      43     .15       0
Bank Sta=20,43
XS Rating Curve= 0 ,0
Exp/Cntr=0.3,0.1

Type RM Length L Ch R = 1 ,462.31  ,239.5341,239.5341,239.5341
BEGIN DESCRIPTION:
RokSpr13
END DESCRIPTION:
Node Name=RokSpr13
XS GIS Cut Line= 2
451422.9117048793181205.33417002 451436.623104883181181.58607002
#Sta/Elev= 30
       0  25.828      25  25.988      29  25.148      30  24.508      32  24.608
      38  24.428      42  24.098      44  23.698      45  23.818      46  23.688
      47  23.298      48  23.028      51  22.748      52  22.228      53  22.148
      55  21.538      57  21.508      60  21.648      61  21.828      62  22.268
      65  22.498      68  23.388      76  23.598      78  23.248      79  23.368
      81  24.498      83  24.828      85  25.568      88  26.388      90  26.608
#Mann= 3 , 0 , 0
       0     .15       0      47    .035       0      68     .15       0
Bank Sta=47,68
XS Rating Curve= 0 ,0
Exp/Cntr=0.3,0.1

Type RM Length L Ch R = 1 ,459.92  ,1057.185,1057.185,1057.185
BEGIN DESCRIPTION:
RokSpr14
END DESCRIPTION:
Node Name=RokSpr14
XS GIS Cut Line= 2
451484.9297048793181229.40207002 451504.259604883181220.38617002
#Sta/Elev= 30
       0  26.008       3  25.808       5  25.088       7  24.808      10  24.608
      16  24.438      17  24.278      19  23.768      20  23.428      21  22.868
      22  22.858      25  22.508      32  22.348      34  22.018      35  21.998
      38  22.238      41  22.688      44  22.928      45  23.128      48  22.588
      52  22.378      54  22.368      56  22.568      57  22.758      58  23.818
      59  24.598      60  24.438      61  24.698      67  26.678      70  26.078
#Mann= 3 , 0 , 0
       0     .15       0      19    .035       0      58     .15       0
Bank Sta=19,58
XS Rating Curve= 0 ,0
Exp/Cntr=0.3,0.1

Type RM Length L Ch R = 1 ,449.35  ,5321.588,5321.588,5321.588
BEGIN DESCRIPTION:
ROK7
END DESCRIPTION:
Node Name=ROK7
XS GIS Cut Line= 2
 451531.470204883181508.48117002 451753.720604883181451.33097002
#Sta/Elev= 30
    1969    28.9    1997    28.9    2000    28.4    2006    23.8    2015    23.1
    2016    20.2    2020    20.1    2025    20.5    2035    22.9    2050    22.9
    2055    23.6    2060    23.1    2085    23.9    2115    22.9    2125    23.5
    2135    23.5    2138   23.75    2143    25.1    2171    23.8    2173    23.3
    2177    23.2    2183    23.8    2185    24.9    2200    24.4    2300    23.9
    2400    24.9    2500    24.8    2600    25.3    2650      24    3000    28.9
#Mann= 3 , 0 , 0
    1969      .2       0    2006     .05       0    2085      .2       0
Bank Sta=2006,2085
XS Rating Curve= 0 ,0
Exp/Cntr=0.3,0.1

Type RM Length L Ch R = 1 ,396.13  ,4586.122,4586.122,4586.122
BEGIN DESCRIPTION:
ROK6
END DESCRIPTION:
Node Name=ROK6
XS GIS Cut Line= 2
450737.7186048793182638.78337002451099.6693048793182740.38357002
#Sta/Elev= 30
    1950   23.91    2000   23.11    2002   21.71    2005   21.31    2015   20.61
    2020   19.81    2025   19.71    2030   20.21    2035   19.51    2040   19.51
    2045   18.91    2050   18.61    2060   18.81    2065   20.01    2070   19.81
    2075   19.31    2080   19.31    2085   19.61    2090   19.21    2100   19.11
    2105   19.91    2110   20.51    2115   20.81  2127.5   22.51    2150   21.81
    2300   21.81    2400   22.31    2500   21.91    2600   23.41    2630   23.61
#Mann= 3 , 0 , 0
    1950     .22       0    2000     .17       0  2127.5     .22       0
Bank Sta=2000,2127.5
XS Rating Curve= 0 ,0
Vertical n Elevations= 2
      46     120
Vertical n for Station=1950
     .22     .22
Vertical n for Station=2000
     .17    .085
Vertical n for Station=2127.5
     .22     .22
Vertical n Flow=-1
Exp/Cntr=0.3,0.1

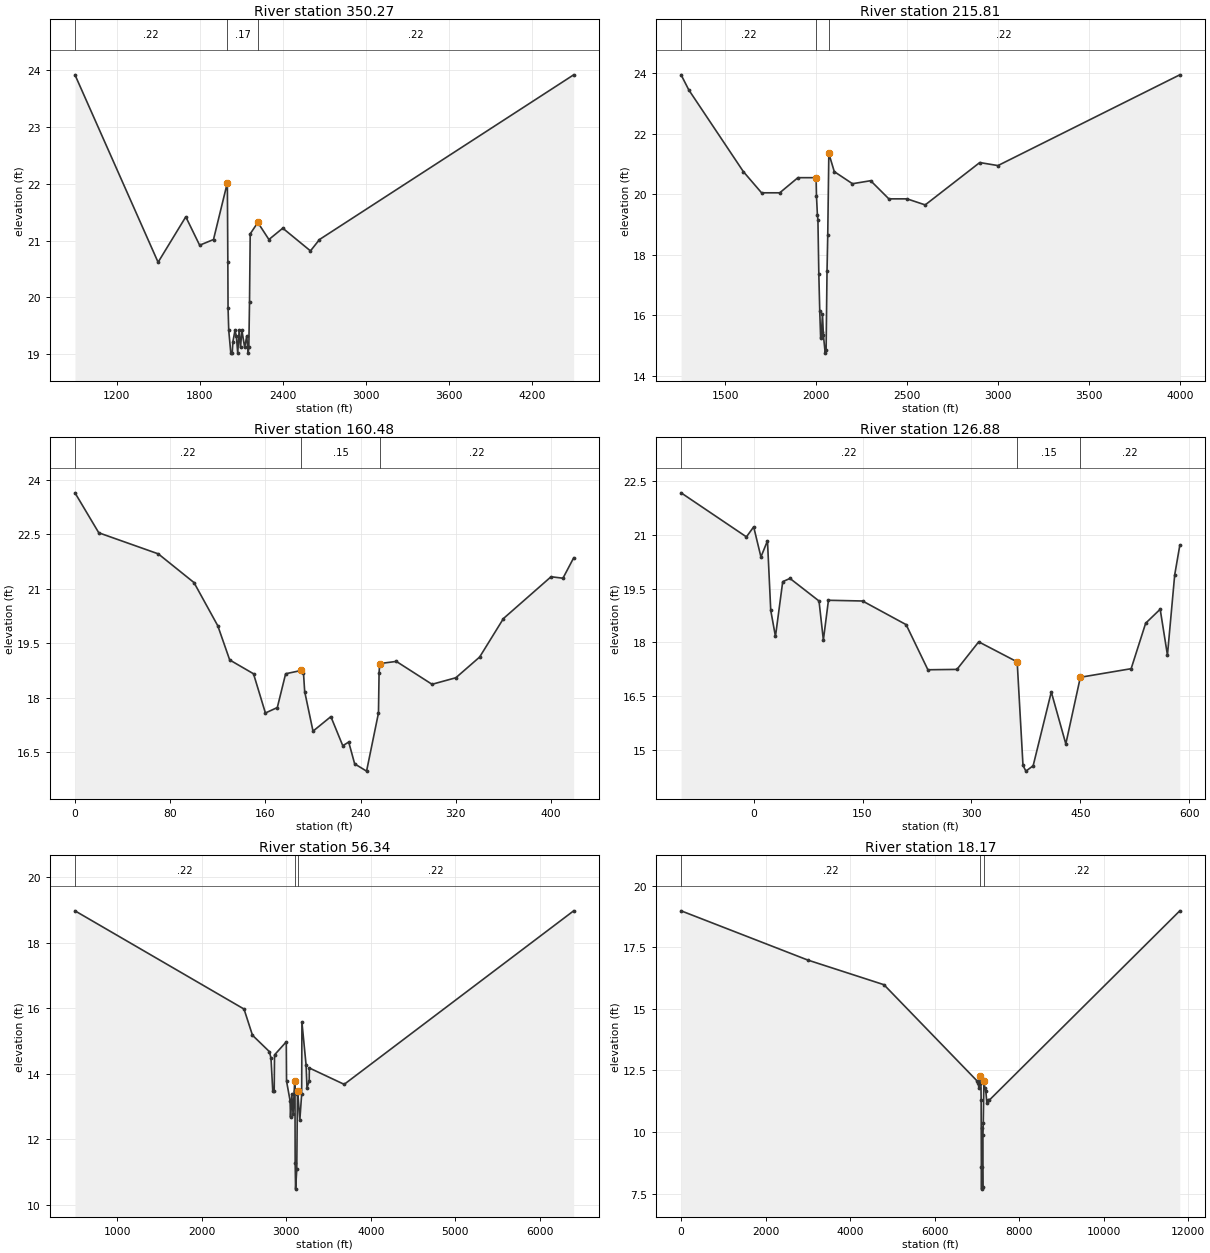
Type RM Length L Ch R = 1 ,350.27  ,13446.29,13446.29,13446.29
BEGIN DESCRIPTION:
ROK5
END DESCRIPTION:
Node Name=ROK5
XS GIS Cut Line= 2
 451861.670804883183629.38537002 451766.420704883183273.78467002
#Sta/Elev= 30
     900   23.92    1500   20.62    1700   21.42    1800   20.92    1900   21.02
    2000   22.02  2003.5   20.63    2005   19.82    2010   19.42    2025   19.02
    2035   19.02    2040   19.22    2055   19.42    2065   19.32    2075   19.02
    2085   19.42    2095   19.12    2105   19.42    2125   19.12    2140   19.32
    2150   19.02    2155   19.12    2160   19.92    2165   21.12    2220   21.32
    2300   21.02    2400   21.22    2600   20.82    2665   21.02    4500   23.92
#Mann= 3 , 0 , 0
     900     .22       0    2000     .17       0    2220     .22       0
Bank Sta=2000,2220
XS Rating Curve= 0 ,0
Vertical n Elevations= 2
      46     120
Vertical n for Station=900
     .22     .22
Vertical n for Station=2000
     .17    .085
Vertical n for Station=2220
     .22     .22
Vertical n Flow=-1
Exp/Cntr=0.3,0.1

Type RM Length L Ch R = 1 ,215.81  ,5532.677,5532.677,5532.677
BEGIN DESCRIPTION:
ROK4
END DESCRIPTION:
Node Name=ROK4
XS GIS Cut Line= 2
 453798.424704883181095.73027002453442.8240048793181038.58017002
#Sta/Elev= 30
  1257.5   23.94    1300   23.44    1600   20.74    1700   20.04    1800   20.04
    1900   20.54    2000   20.54    2002   19.94    2007   19.32    2010   19.14
    2015   17.34    2020   16.14    2025   15.24    2030   15.44    2035   16.04
    2040   15.34    2050   14.74    2055   14.84    2060   17.44    2064   18.64
    2070   21.34    2100   20.74    2200   20.34    2300   20.44    2400   19.84
    2500   19.84    2600   19.64    2900   21.04    3000   20.94    4000   23.94
#Mann= 3 , 0 , 0
  1257.5     .22       0    2000     .15       0    2070     .22       0
Bank Sta=2000,2070
XS Rating Curve= 0 ,0
Exp/Cntr=0.3,0.1

Type RM Length L Ch R = 1 ,160.48  ,3360.203,3360.203,3360.203
BEGIN DESCRIPTION:
ROK3
END DESCRIPTION:
Node Name=ROK3
XS GIS Cut Line= 2
 453683.837304883179720.61477002 453618.766804883179618.24147002
#Sta/Elev= 30
       0  23.645      20  22.545      70  21.965     100  21.175     120  19.985
     130  19.045     150  18.665     160  17.585     170  17.735     177  18.665
     190  18.755     192  18.685     193  18.175     200  17.085     215  17.485
     225  16.685     230  16.785     235  16.185     245  15.985     255  17.585
   255.5  18.685     256  18.945     270  19.005     300  18.375     320  18.555
     340  19.125     360  20.185     400  21.335     410  21.295     419  21.855
#Mann= 3 , 0 , 0
       0     .22       0     190     .15       0     256     .22       0
Bank Sta=190,256
XS Rating Curve= 0 ,0
Vertical n Elevations= 5
      50      60      75     120     420
Vertical n for Station=0
     .22     .22     .22     .22     .22
Vertical n for Station=190
     .15    .128    .105     .09    .075
Vertical n for Station=256
     .22     .22     .22     .22     .22
Vertical n Flow=-1
Exp/Cntr=0.3,0.1

Type RM Length L Ch R = 1 ,126.88  ,7053.478,7053.478,7053.478
BEGIN DESCRIPTION:
ROK2
END DESCRIPTION:
Node Name=ROK2
XS GIS Cut Line= 2
454544.9803048793179351.14227002 454484.226104883179114.52637002
#Sta/Elev= 30
    -100  22.173     -10  20.943       0  21.223      10  20.383      19  20.833
    23.5  18.893      30  18.163      40  19.693      50  19.783      90  19.153
      96  18.063     103  19.173     150  19.153     210  18.493     240  17.233
     280  17.243     310  18.013     363  17.453     371  14.563     375  14.403
     385  14.553     410  16.613     430  15.163     450  17.023     520  17.263
     540  18.533     560  18.923     570  17.643     580  19.883     587  20.703
#Mann= 3 , 0 , 0
    -100     .22       0     363     .15       0     450     .22       0
Bank Sta=363,450
XS Rating Curve= 0 ,0
Vertical n Elevations= 5
      50      60      75     120     420
Vertical n for Station=-100
     .22     .22     .22     .22     .22
Vertical n for Station=363
     .15    .128    .105     .09    .075
Vertical n for Station=450
     .22     .22     .22     .22     .22
Vertical n Flow=-1
Exp/Cntr=0.3,0.1

Type RM Length L Ch R = 1 ,56.34   ,3817.881,3817.881,3817.881
BEGIN DESCRIPTION:
ROK1
END DESCRIPTION:
Node Name=ROK1
XS GIS Cut Line= 2
455779.6287048793178130.27437002455392.2779048793178035.02417002
#Sta/Elev= 30
     500   18.97    2500   15.97    2600   15.17    2800   14.67    2819   14.47
    2840   13.47    2857   13.47    2861   14.57    3000   14.97    3003   13.77
    3045   13.17    3050   12.67    3065   13.37    3080   12.77    3100   13.77
    3103   13.47    3105   11.27    3110   10.47    3124   11.07    3132   13.37
    3135   13.47    3160   12.57    3182   13.37    3185   15.57    3234   14.27
    3245   13.57    3271   13.77    3273   14.17    3685   13.67    6400   18.97
#Mann= 3 , 0 , 0
     500     .22       0    3100     .16       0    3135     .22       0
Bank Sta=3100,3135
XS Rating Curve= 0 ,0
Vertical n Elevations= 5
      50      60      75     120     420
Vertical n for Station=500
     .22     .22     .22     .22     .22
Vertical n for Station=3100
     .16    .136    .112    .096     .08
Vertical n for Station=3135
     .22     .22     .22     .22     .22
Vertical n Flow=-1
Exp/Cntr=0.3,0.1

Type RM Length L Ch R = 1 ,18.17   ,1816.503,1816.503,1816.503
BEGIN DESCRIPTION:
WK16
END DESCRIPTION:
Node Name=WK16
XS GIS Cut Line= 2
 456154.279404883176999.97207002455735.1786048793176961.87207002
#Sta/Elev= 23
       0   18.98    3000   16.98    4800   15.98    7000   12.08    7025   11.98
    7050   11.78    7075   12.28    7095   11.98    7100   11.28    7105    8.58
    7110    7.68    7125   10.18    7130    8.58    7135    7.78    7140    9.88
    7150   10.38    7165   12.08    7185   11.78    7210   11.68    7235   11.18
    7260   11.28    7285   11.28   11800   18.98
#Mann= 3 , 0 , 0
       0     .22       0    7075     .17       0    7165     .22       0
Bank Sta=7075,7165
XS Rating Curve= 0 ,0
Vertical n Elevations= 5
      50      60      75     120     420
Vertical n for Station=0
     .22     .22     .22     .22     .22
Vertical n for Station=7075
     .17    .145    .119    .102    .085
Vertical n for Station=7165
     .22     .22     .22     .22     .22
Vertical n Flow=-1
Exp/Cntr=0.3,0.1