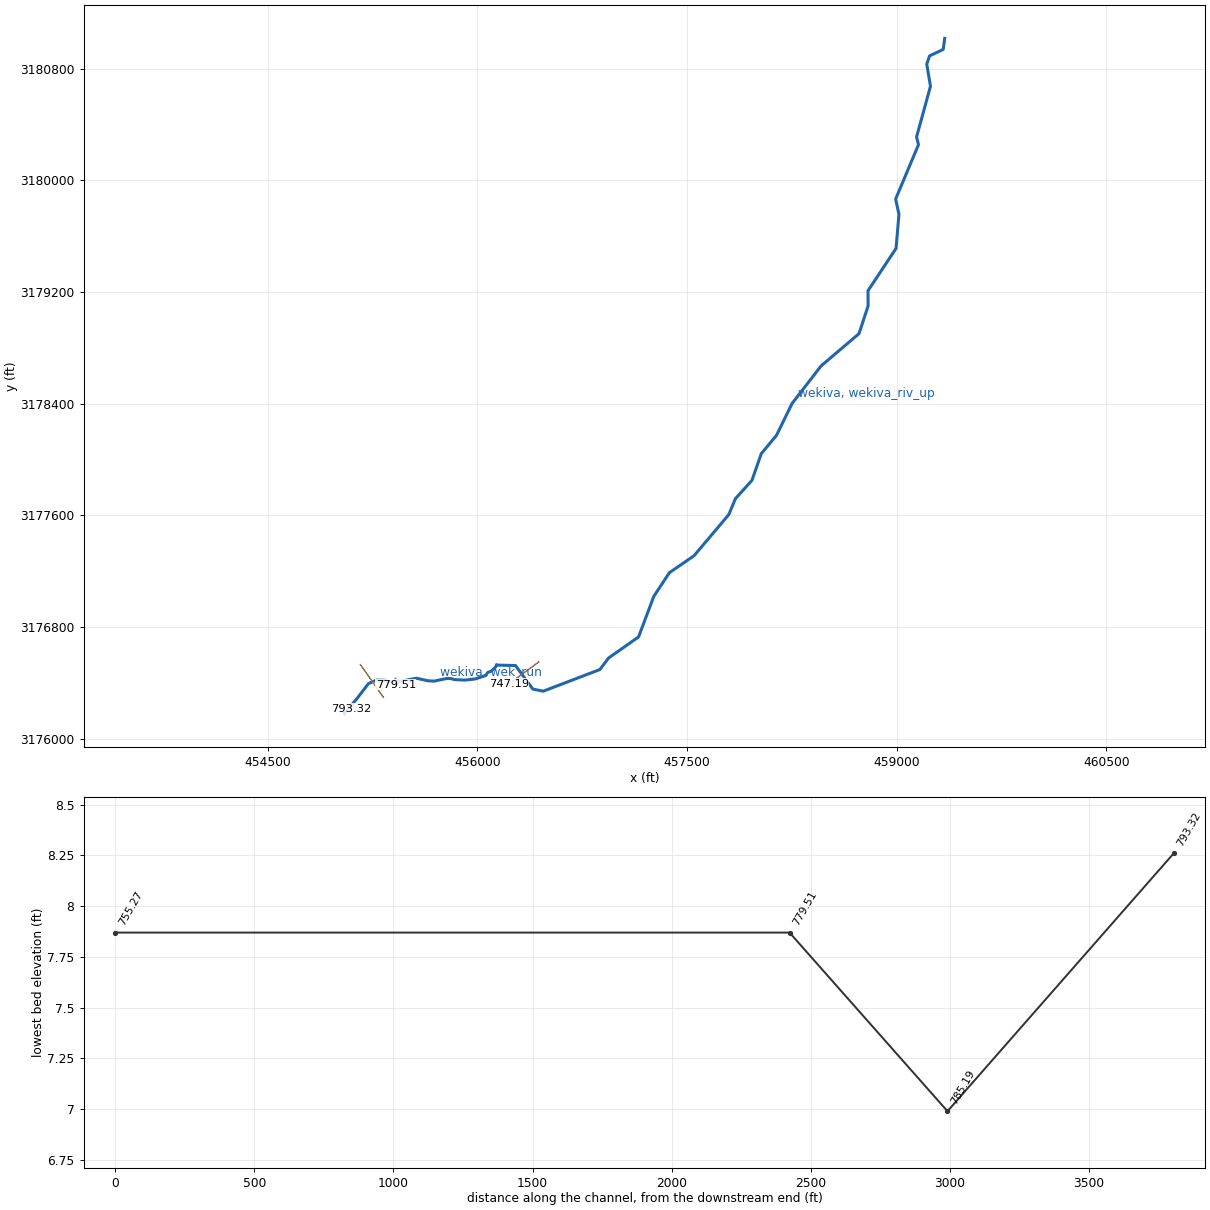
HEC-RAS study wekiva_ras.prj: wekiva_ras

--- wekiva_ras.g06 (geometry) --- (continued)

River Reach=wekiva          ,wek_run
Reach XY= 30
455048.2208048793176180.16957002 455135.652104883176281.35967002
 455161.290704883176314.97967002 455186.929404883176348.59957002
 455221.114204883176393.42617002 455279.169004883176418.60717002
 455347.296904883176417.28807002 455354.239904883176411.66767002
 455361.182804883176406.04717002 455400.360904883176407.28697002
 455413.420304883176407.70017002455488.1398048793176417.28807002
455564.8629048793176432.29287002455606.0147048793176422.97217002
455647.1665048793176413.65137002 455691.231104883176411.45757002
455719.5225048793176417.37937002 455733.668104883176420.34037002
 455779.433904883176429.91987002455792.4830048793176430.21637002
 455805.532004883176430.51277002 455839.885204883176422.07207002
455912.5910048793176418.70157002455983.9726048793176426.74377002
 456062.051204883176452.13507002 456073.688804883176473.08307002
456100.9846048793176483.66277002 456127.857104883176509.68897002
 456133.653204883176518.05757002456138.8371248563176526.33636962

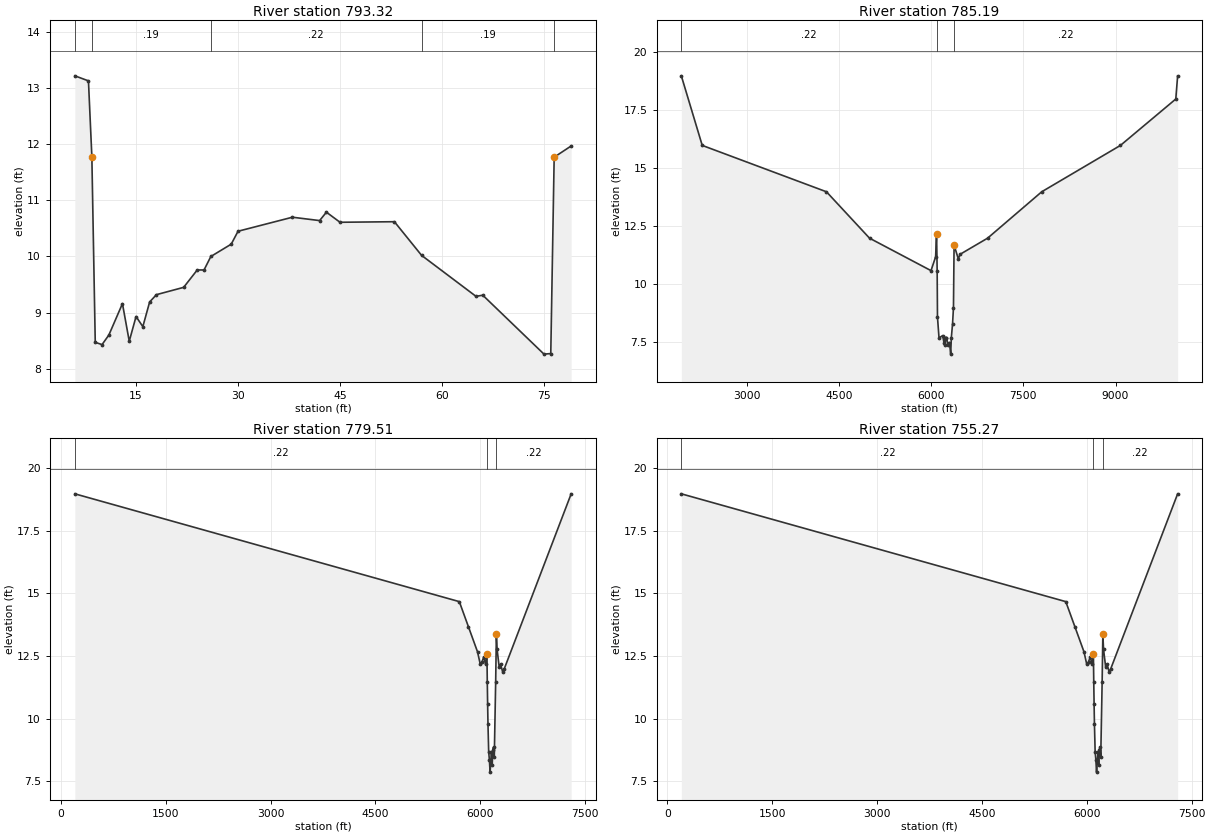
Type RM Length L Ch R = 1 ,793.32  ,813.0906,813.0906,813.0906
BEGIN DESCRIPTION:
WekSpr6
WekSpr6
END DESCRIPTION:
Node Name=WekSpr6
XS GIS Cut Line= 2
     455071.1753     3176243.645     455098.0644     3176211.408
#Sta/Elev= 30
       6   13.22       8   13.13     8.5   11.78       9    8.47      10    8.43
      11     8.6      13    9.16      14    8.49      15    8.93      16    8.75
      17    9.19      18    9.32      22    9.45      24    9.76      25    9.76
      26      10      29   10.22      30   10.45      38    10.7      42   10.64
      43   10.79      45   10.61      53   10.62      57   10.02      65    9.29
      66    9.31      75    8.26      76    8.27    76.5   11.77      79   11.97
#Mann= 5 ,-1 , 0
       6     .22       0     8.5     .19       0      26     .22       0
      57     .19       0    76.5     .22       0
Bank Sta=8.5,76.5
XS Rating Curve= 0 ,0
Exp/Cntr=0.3,0.1

Type RM Length L Ch R = 1 ,785.19  ,567.8806,567.8806,567.8806
BEGIN DESCRIPTION:
WEK13
END DESCRIPTION:
Node Name=WEK13
XS GIS Cut Line= 2
 455163.677404883176530.07117002455328.7778048793176295.12067002
#Sta/Elev= 30
    1940   18.99    2280   15.99    4300   13.99    5000   11.99    6000   10.59
    6075   11.19    6090   12.19    6100   10.59    6105    8.59    6130    7.69
    6190    7.79    6210    7.49    6220    7.69    6230    7.39    6240    7.69
    6250    7.69    6280    7.39    6300    7.49    6320    6.99    6330    7.69
    6350    8.29    6365    8.99    6375   11.69    6445   11.09    6470   11.29
    6920   11.99    7800   13.99    9080   15.99    9980   17.99   10010   18.99
#Mann= 3 , 0 , 0
    1940     .22       0    6090     .19       0    6375     .22       0
Bank Sta=6090,6375
XS Rating Curve= 0 ,0
Vertical n Elevations= 5
      50      60      80     100     500
Vertical n for Station=1940
     .22     .22     .22     .22     .22
Vertical n for Station=6090
     .19    .152    .143    .124    .095
Vertical n for Station=6375
     .22     .22     .22     .22     .22
Vertical n Flow=-1
Exp/Cntr=0.3,0.1

Type RM Length L Ch R = 1 ,779.51  ,2424,2424,2424
BEGIN DESCRIPTION:
WK17
END DESCRIPTION:
Node Name=WK17
XS GIS Cut Line= 2
      455414.687     3176429.959      455415.957     3176385.507
#Sta/Elev= 28
     200   18.97    5700   14.67    5830   13.67    5960   12.67    6000   12.17
    6025   12.27    6050   12.47    6075   12.17    6095   12.57    6100   11.47
    6105   10.57    6110    9.77    6120    8.67    6130    8.37    6140    7.87
    6160    8.67    6170    8.17    6180    8.77    6190    8.87    6200    8.47
    6220   11.47    6230   13.37    6240   12.77    6270   12.07    6290   12.17
    6320   11.87    6340   11.97    7300   18.97
#Mann= 3 , 0 , 0
     200     .22       0    6095     .19       0    6230     .22       0
Bank Sta=6095,6230
XS Rating Curve= 0 ,0
Vertical n Elevations= 5
      50      60      80     100     500
Vertical n for Station=200
     .22     .22     .22     .22     .22
Vertical n for Station=6095
     .19    .152    .143    .124    .095
Vertical n for Station=6230
     .22     .22     .22     .22     .22
Vertical n Flow=-1
Exp/Cntr=0.3,0.1

Type RM Length L Ch R = 1 ,755.27  ,807.9,807.9,807.9
BEGIN DESCRIPTION:
WK17-COPY
END DESCRIPTION:
XS GIS Cut Line= 2
      455414.687     3176429.959      455415.957     3176385.507
#Sta/Elev= 28
     200   18.97    5700   14.67    5830   13.67    5960   12.67    6000   12.17
    6025   12.27    6050   12.47    6075   12.17    6095   12.57    6100   11.47
    6105   10.57    6110    9.77    6120    8.67    6130    8.37    6140    7.87
    6160    8.67    6170    8.17    6180    8.77    6190    8.87    6200    8.47
    6220   11.47    6230   13.37    6240   12.77    6270   12.07    6290   12.17
    6320   11.87    6340   11.97    7300   18.97
#Mann= 3 , 0 , 0
     200     .22       0    6095     .19       0    6230     .22       0
Bank Sta=6095,6230
XS Rating Curve= 0 ,0
Vertical n Elevations= 5
      50      60      80     100     500
Vertical n for Station=200
     .22     .22     .22     .22     .22
Vertical n for Station=6095
     .19    .152    .143    .124    .095
Vertical n for Station=6230
     .22     .22     .22     .22     .22
Vertical n Flow=-1
Exp/Cntr=0.3,0.1

River Reach=wekiva          ,wekiva_riv_up
Reach XY= 30
456138.8371248563176526.33636962 456273.222804883176523.01937002
 456397.217404883176354.37827002456471.5181048793176339.12477002
456876.9030048793176494.45407002456939.6671048793176577.53467002
 457153.375704883176727.96127002 457262.428904883177018.57457002
 457373.727804883177188.27367002457550.1979048793177310.15237002
457798.8880048793177604.91717002 457846.496804883177719.31067002
 457964.527104883177850.23497002 458031.311704883178041.66227002
 458140.415304883178173.57847002458251.4611048793178401.48007002
458459.1300048793178670.82637002 458730.236004883178901.92767002
 458795.466704883179100.95897002458794.6732048793179209.66587002
 458995.423904883179513.56897002 459016.054404883179757.96107002
458992.2500048793179866.66797002459155.8558048793180256.81797002
459141.9699048793180311.96497002 459241.551704883180675.77587002
 459214.913104883180833.89037002459235.2039048793180893.18957002
459332.6042048793180939.68187002 459343.436962483181018.99032073

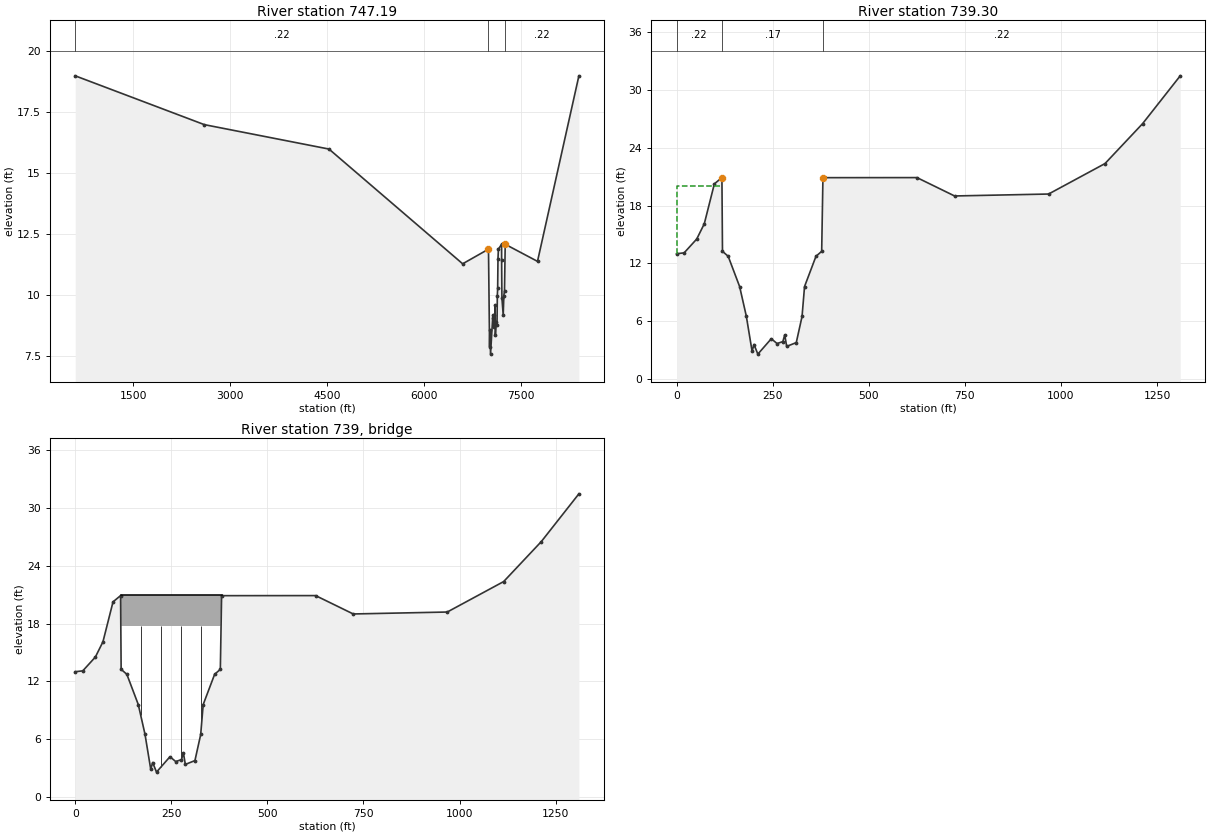
Type RM Length L Ch R = 1 ,747.19  ,799,799,799
BEGIN DESCRIPTION:
WEK12
END DESCRIPTION:
Node Name=WEK12
XS GIS Cut Line= 2
456440.0300048793176549.12117002 456224.129604883176390.37087002
#Sta/Elev= 30
     600   18.97    2600   16.97    4530   15.97    6600   11.27    7000   11.87
    7017    7.87    7022    8.57    7032    7.57    7067    9.17    7077    9.07
    7082    8.67    7092    9.17    7097    8.87    7102    9.57    7107    8.37
    7117    8.87    7132    8.77    7137    9.97    7142   10.27    7147   11.48
  7153.5   11.87    7203   12.07  7203.5   11.41    7208    9.87    7228    9.17
    7238    9.97    7248   10.17    7259   12.07    7759   11.37    8400   18.97
#Mann= 3 , 0 , 0
     600     .22       0    7000     .19       0    7259     .22       0
Bank Sta=7000,7259
XS Rating Curve= 0 ,0
Vertical n Elevations= 5
      90     120     200     300    1000
Vertical n for Station=600
     .22     .22     .22     .22     .22
Vertical n for Station=7000
     .19    .152    .143    .124    .095
Vertical n for Station=7259
     .22     .22     .22     .22     .22
Vertical n Flow=-1
Exp/Cntr=0.3,0.1

Type RM Length L Ch R = 1 ,739.30  ,50,50,50
BEGIN DESCRIPTION:
interpolation of WEK12 amd WK15
END DESCRIPTION:
#Sta/Elev= 30
       0      13  19.669   13.09  52.451  14.527   72.12  16.109  98.345  20.257
  118.01  20.907 119.465   13.25 134.331   12.73 164.063    9.59 181.465    6.52
 196.465    2.87 201.465    3.57 211.465    2.57 246.465    4.17 261.465    3.67
 276.465    3.87 281.465    4.57 286.465    3.37 311.465    3.77 326.465    6.48
 332.965    9.59 362.697   12.73 377.563   13.25  380.83  20.901 625.468  20.908
 723.322      19 967.956  19.2011114.737  22.3661212.591  26.5151310.444   31.48
#Mann= 3 , 0 , 0
       0     .22       0  118.01     .17       0  380.83     .22       0
#XS Ineff= 1 ,-1
       0  118.01      20
Permanent Ineff=
       F
Bank Sta=118.01,380.83
XS Rating Curve= 0 ,0
Vertical n Elevations= 5
      90     120     200     300    1000
Vertical n for Station=0
     .22     .22     .22     .22     .22
Vertical n for Station=118.01
     .17    .136    .128    .111    .085
Vertical n for Station=380.83
     .22     .22     .22     .22     .22
Vertical n Flow=-1
Exp/Cntr=0.3,0.1

Type RM Length L Ch R = 3 ,739     ,,,
Bridge Culvert--1,0,-1,-1, 0
Deck Dist Width WeirC Skew NumUp NumDn MinLoCord MaxHiCord MaxSubmerge Is_Ogee
10,30,2.6,0, 2, 2, , , 0.98, 0, 0,0,,
     118   380.9
      21      21
   17.75   17.75
     118   380.9
      21      21
   17.75   17.75
Pier Skew, UpSta & Num, DnSta & Num=  ,170.5, 2 ,170.5, 2 , 0 , 0 , 0 ,,
       1       1
       0      21
       1       1
       0      21
Pier Skew, UpSta & Num, DnSta & Num=  ,223, 2 ,223, 2 , 0 , 0 , 0 ,,
       1       1
       0      21
       1       1
       0      21
Pier Skew, UpSta & Num, DnSta & Num=  ,275.5, 2 ,275.5, 2 , 0 , 0 , 0 ,,
       1       1
       0      21
       1       1
       0      21
Pier Skew, UpSta & Num, DnSta & Num=  ,328, 2 ,328, 2 , 0 , 0 , 0 ,,
       1       1
       0      21
       1       1
       0      21
BR Coef=-1 , 0 , 0 ,, 0 ,,,0.8,-1,,0,
WSPro=,,,, 1 ,,,, 0 ,,,, 0 ,,,,-1 ,-1 ,-1 , 0 , 0 , 0 , 0 , 0
BC Design=,, 0 ,, 0 ,,,,,,
BC Use User HTab Curves=0
BC User HTab FreeFlow(D)= 0