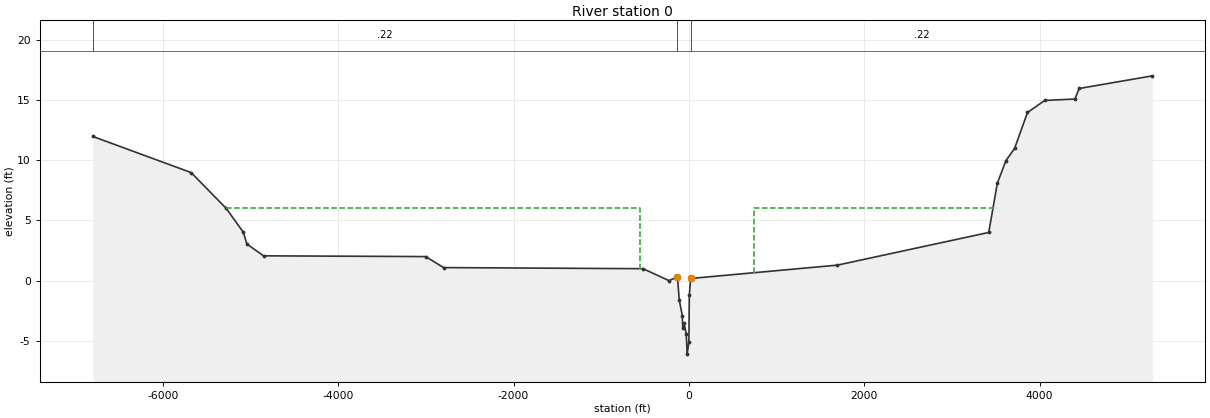
HEC-RAS study wekiva_ras.prj: wekiva_ras

--- wekiva_ras.g06 (geometry) --- (continued)

Type RM Length L Ch R = 1 ,0       ,7.0538,7.0538,7.0538
BEGIN DESCRIPTION:
LoWek
END DESCRIPTION:
Node Name=LoWek
XS GIS Cut Line= 2
  463445.2442725 3193619.5738227  463552.4459684 3193623.8064514
#Sta/Elev= 30
   -6800 11.9701 -5678.3  8.9714-5278.16       6-5081.38  4.0045-5042.02  3.0388
-4851.79  2.0607-3001.98  1.9983-2798.63  1.0848-522.446   .9926-227.263   .0021
    -130    .312    -110  -1.598     -75  -2.898     -70  -3.898     -55  -3.548
     -30  -4.398     -20  -6.098       0  -5.098       5   -1.22      20     .18
1694.704  1.28913420.403       43518.692  8.08733616.982  9.96843715.271 10.9703
3862.706 13.96154059.285 14.95594403.298 15.07464452.443 15.94895287.904      17
#Mann= 3 , 0 , 0
   -6800     .22       0    -130      .2       0      20     .22       0
#XS Ineff= 2 ,-1
 -5284.8  -561.8       6  743.56 3518.69       6
Permanent Ineff=
       F       F
Bank Sta=-130,20
XS Rating Curve= 0 ,0
Vertical n Elevations= 5
     140     200     400     700    2000
Vertical n for Station=-6800
     .22     .22     .22     .22     .22
Vertical n for Station=-130
      .2     .16     .13    .115      .1
Vertical n for Station=20
     .22     .22     .22     .22     .22
Vertical n Flow=-1
Exp/Cntr=0.3,0.1
Stream Node=LtWekiva        ,LtWekiva        , 0 , 0 ,Upstream end
Stream Node=LtWekiva        ,LtWekiva        , 0 , 1 ,Downstream end
Stream Node=ROK             ,ROK             , 0 , 0 ,Upstream end
Stream Node=ROK             ,ROK             , 0 , 1 ,Downstream end
Stream Node=wekiva          ,wek_run         , 0 , 0 ,Upstream end
Stream Node=wekiva          ,wek_run         , 0 , 1 ,Downstream end
Stream Node=wekiva          ,wekiva_riv_up   , 0 , 0 ,Upstream end
Stream Node=wekiva          ,wekiva_riv_up   , 0 , 1 ,Downstream end
Stream Node=wekiva          ,wekiva_riv_down , 0 , 0 ,Upstream end
Stream Node=wekiva          ,wekiva_riv_down , 0 , 1 ,Downstream end
LCMann Table=0

Chan Stop Cuts=-1
Use User Specified Reach Order=0
Composite Channel Slope=5