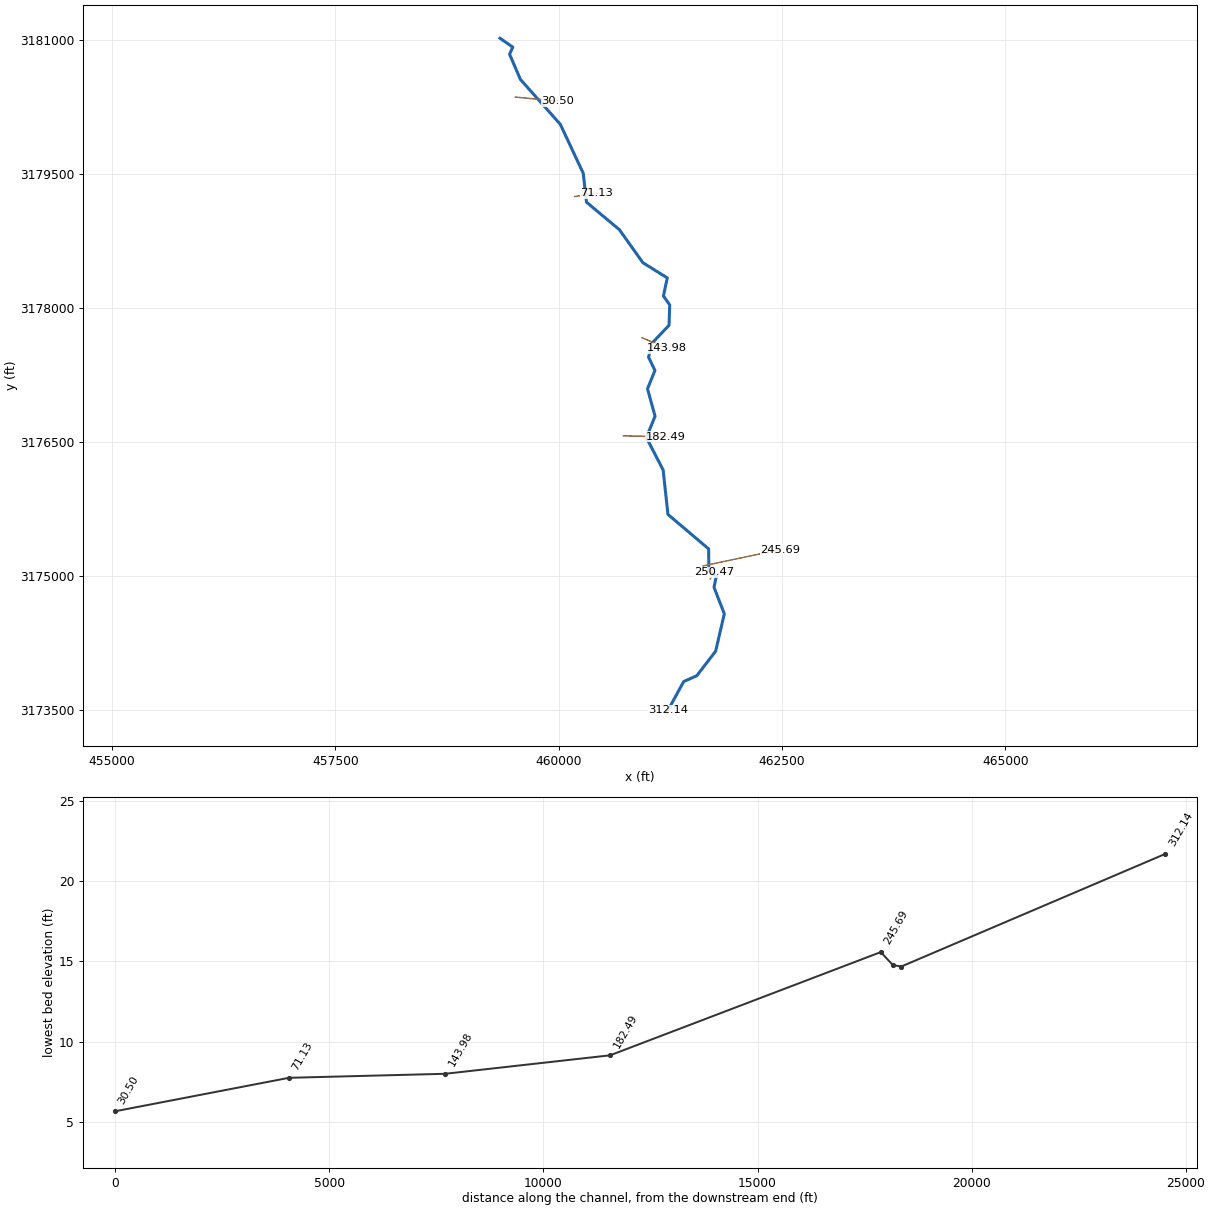
--- wekiva_ras.prj (project) ---

Proj Title=wekiva_ras
Current Plan=p01
Default Exp/Contr=0.3,0.1
English Units
Geom File=g01
Flow File=f03
Unsteady File=u02
Plan File=p03
Plan File=p01
Y Axis Title=Elevation
X Axis Title(PF)=Main Channel Distance
X Axis Title(XS)=Station
BEGIN DESCRIPTION:
END DESCRIPTION:
DSS File=dss
DSS Export Rating Curves= 0
DSS Export Rating Curve Sorted= 0
DSS Export Volume Flow Curves= 0
DXF OffsetX= 0
DXF OffsetY= 0
DXF ScaleX= 1
DXF ScaleY= 10
Specific Locations Profile Table=stations                             , 8
LtWekiva        ,LtWekiva        ,312.14
LtWekiva        ,LtWekiva        ,248.51
ROK             ,ROK             ,480.77
ROK             ,ROK             ,126.88
wekiva          ,wek_run         ,793.32
wekiva          ,wekiva_riv_up   ,739.30
wekiva          ,wekiva_riv_down ,405.81
wekiva          ,wekiva_riv_down ,318.86

--- wekiva_ras.p01 (plan) ---

Plan Title=unsteady_2009
Program Version=5.03
Short Identifier=U2009
Simulation Date=20JAN2009,2400,20JUL2009,2300
Geom File=g01
Flow File=u02
Subcritical Flow
K Sum by GR= 0
Std Step Tol= 0.01
Critical Tol= 0.01
Num of Std Step Trials= 20
Max Error Tol= 0.3
Flow Tol Ratio= 0.001
Split Flow NTrial= 30
Split Flow Tol= 0.02
Split Flow Ratio= 0.02
Log Output Level= 0
Friction Slope Method= 1
Unsteady Friction Slope Method= 2
Unsteady Bridges Friction Slope Method= 1
Parabolic Critical Depth
Global Vel Dist= 0 , 0 , 0
Global Log Level= 0
CheckData=True
Encroach Param=-1 ,0,0, 0
Computation Interval=30MIN
Output Interval=1DAY
Instantaneous Interval=1DAY
Mapping Interval=1DAY
Run HTab= 1
Run UNet= 1
Run Sediment= 0
Run PostProcess= 1
Run WQNet= 0
Run RASMapper= 0
UNET Theta= 1
UNET Theta Warmup= 1
UNET ZTol= 0.02
UNET ZSATol= 0.02
UNET MxIter= 20
UNET Max Iter WO Improvement= 0
UNET MaxInSteps= 0
UNET DtIC= 0
UNET DtMin= 0
UNET MaxCRTS= 20
UNET WFStab= 2
UNET SFStab= 1
UNET WFX= 1
UNET SFX= 1
UNET DSS MLevel= 4
UNET Pardiso=0
UNET DZMax Abort= 100
UNET Use Existing IB Tables=-1
UNET Froude Reduction=True
UNET Froude Limit= 0.8
UNET Froude Power= 4
UNET Time Slicing=0,0, 5
UNET D1 Cores= 0
UNET D2 Coriolis=0
UNET D2 Cores= 0
UNET D2 Theta= 1
UNET D2 Theta Warmup= 1
UNET D2 Z Tol= 0.01
UNET D2 Volume Tol= 0.01
UNET D2 Max Iterations= 20
UNET D2 Equation= 0
UNET D2 RampUpFraction=0.1
UNET D2 TimeSlices= 1
UNET D2 BCVolumeCheck=0
UNET D1D2 MaxIter= 0
UNET D1D2 ZTol=0.01
UNET D1D2 QTol=0.1
UNET D1D2 MinQTol=1
DSS File=dss
Write IC File= 0
Write IC File at Fixed DateTime=0
Write IC File at Sim End=0
Echo Input=False
Echo Parameters=False
Echo Output=False
Write Detailed= 0
HDF Write Warmup=0
HDF Write Time Slices=0
HDF Flush=0
HDF Face Node Velocities=0
HDF Compression= 1
HDF Chunk Size= 1
HDF Spatial Parts= 1
HDF Use Max Rows=0
HDF Fixed Rows= 1
Calibration Method= 0
Calibration Iterations= 20
Calibration Max Change=0.05
Calibration Tolerance=0.2
Calibration Maximum=1.5
Calibration Minimum=0.5
Calibration Optimization Method= 1
WQ AD Non Conservative
WQ ULTIMATE=-1
WQ Max Comp Step=1HOUR
WQ Output Interval=15MIN
WQ Output Selected Increments= 0
WQ Output face flow=0
WQ Output face velocity=0
WQ Output face area=0
WQ Output face dispersion=0
WQ Output cell volume=0
WQ Output cell surface area=0
WQ Output cell continuity=0
WQ Output cumulative cell continuity=0
WQ Output face conc=0
WQ Output face dconc_dx=0
WQ Output face courant=0
WQ Output face peclet=0
WQ Output face adv mass=0
WQ Output face disp mass=0
WQ Output cell mass=0
WQ Output cell source sink temp=0
WQ Output nsm pathways=0
WQ Output nsm derived pathways=0
WQ Output MaxMinRange=-1
WQ Daily Max Min Mean=-1
WQ Daily Range=0
WQ Daily Time=0
WQ Create Restart=0
WQ Fixed Restart=0
WQ System Summary=0
WQ Write To DSS=0
WQ Use Fixed Temperature=0
Sorting and Armoring Iterations= 10
XS Update Threshold= 0.02
Bed Roughness Predictor= 0
Hydraulics Update Threshold= 0.02
Energy Slope Method= 1
Volume Change Method= 1
Sediment Retention Method= 0
XS Weighting Method= 0
Number of US Weighted Cross Sections= 1
Number of DS Weighted Cross Sections= 1
Upstream XS Weight=0
Main XS Weight=1
Downstream XS Weight=0
Number of DS XS's Weighted with US Boundary= 1
Upstream Boundary Weight= 1
Weight of XSs Associated with US Boundary= 0
Number of US XS's Weighted with DS Boundary= 1
Downstream Boundary Weight= 0.5
Weight of XSs Associated with DS Boundary= 0.5
Percentile Method= 0
Sediment Output Level= 4
Mass or Volume Output= 0
Output Increment Type= 1
Profile and TS Output Increment= 1
XS Output Flag= 0
XS Output Increment= 10
Write Gradation File= 0
Read Gradation Hotstart= 0
Write HDF5 File= 1
Write DSS Sediment File= 0
SV Curve= 0
Specific Gage Flag= 0

--- wekiva_ras.p03 (plan) ---

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Plan Title=Plan 03
Short Identifier=Plan 03
Simulation Date=01JUN2008,2400,31OCT2008,2300
Geom File=g01
Flow File=u01
Computation Interval=1HOUR

--- wekiva_ras.f03 (steady flow) ---

Flow Title=Flow 03
Program Version=5.03
Number of Profiles= 14
Profile Names=PF 1,PF 2,PF 3,PF 4,PF 5,PF 6,PF 7,PF 8,PF 9,PF 10,PF 11,PF 12,PF 13,PF 14
River Rch & RM=LtWekiva,LtWekiva        ,312.14
     .87    44.8     279     269     536     340     269     295    64.8    80.3
    20.5    14.1    5.33      .4
River Rch & RM=LtWekiva,LtWekiva        ,245.69
   29.12   99.89  320.24  327.25  576.71  382.65  327.25  345.13  112.27  113.58
   57.32   47.52   35.97   29.47
River Rch & RM=LtWekiva,LtWekiva        ,182.49
   29.34  118.51  326.64  333.11     640  398.61  333.11  354.77  113.77  114.81
   58.05   47.94   36.21   29.67
River Rch & RM=LtWekiva,LtWekiva        ,30.50
   29.09  140.12  319.54  448.57  1020.7  433.21  448.57  384.36  140.02  216.28
   62.67   51.63   34.72   30.07
River Rch & RM=ROK,ROK             ,480.77
   46.81   50.62   58.99    59.1    72.3    56.8    59.1   59.07   58.21   56.78
   56.06   48.82   48.07   45.98
River Rch & RM=ROK,ROK             ,350.27
   46.81   53.87   66.43   65.06  118.02   69.39   65.06   65.39   61.15   60.37
   58.17   49.14   48.14   45.98
River Rch & RM=ROK,ROK             ,215.81
   48.06   60.87   72.93   72.45  244.78   79.49   72.45   73.43   68.89   71.45
   67.01   50.91   50.04   47.05
River Rch & RM=ROK,ROK             ,18.17
   52.63  118.28  135.41   184.5  421.87  173.02   184.5  162.67  119.14   84.39
    72.6   58.73   56.24   54.45
River Rch & RM=wekiva,wek_run         ,793.32
   50.49   59.48   58.93   59.35      58    57.3   59.35   59.98   54.97   65.09
    63.3   54.43   52.19   50.23
River Rch & RM=wekiva,wekiva_riv_up   ,747.19
  103.56   187.4  196.33  246.07  529.08  237.32  246.07  227.83  176.25  151.98
  137.87  113.83  108.94  105.06
River Rch & RM=wekiva,wekiva_riv_up   ,579.74
  109.22  260.39  254.11  363.38  546.77  348.55  363.38  311.47  274.16  196.47
  136.52  120.89  116.29   114.1
River Rch & RM=wekiva,wekiva_riv_down ,544.57
  138.31   400.5  573.65  811.95 1567.47  781.77  811.95  695.84  414.18  412.75
   199.2  172.52  151.01  144.17
River Rch & RM=wekiva,wekiva_riv_down ,477.90
  134.46  381.67     644  897.74 1712.97   900.7  897.74  771.58  456.61  451.02
  210.91  180.44  147.97  139.01
River Rch & RM=wekiva,wekiva_riv_down ,386.11
  149.45  398.62  662.25  915.94 1732.87  919.32  915.94  789.81  473.88  469.05
  226.53  196.41  163.38  153.51
River Rch & RM=wekiva,wekiva_riv_down ,333.01
     150     407     665     927    1740     922     927     797     479     467
     225     196     164     155
River Rch & RM=wekiva,wekiva_riv_down ,143.23
  164.13  395.45  662.21  992.42 1896.43   896.8  992.42     837  552.92   520.6
   259.2  235.86  178.61  169.47
River Rch & RM=wekiva,wekiva_riv_down ,25.630*
   192.3  496.71  976.34 1309.67 3142.04 1327.24 1309.67 1149.23  674.13  799.64
  336.48  291.63  213.14  196.75
Boundary for River Rch & Prof#=LtWekiva,LtWekiva        , 1
Up Type= 0
Dn Type= 0
Boundary for River Rch & Prof#=LtWekiva,LtWekiva        , 2
Up Type= 0
Dn Type= 0
Boundary for River Rch & Prof#=LtWekiva,LtWekiva        , 3
Up Type= 0
Dn Type= 0
Boundary for River Rch & Prof#=LtWekiva,LtWekiva        , 4
Up Type= 0
Dn Type= 0
Boundary for River Rch & Prof#=LtWekiva,LtWekiva        , 5
Up Type= 0
Dn Type= 0
Boundary for River Rch & Prof#=LtWekiva,LtWekiva        , 6
Up Type= 0
Dn Type= 0
Boundary for River Rch & Prof#=LtWekiva,LtWekiva        , 7
Up Type= 0
Dn Type= 0
Boundary for River Rch & Prof#=LtWekiva,LtWekiva        , 8
Up Type= 0
Dn Type= 0
Boundary for River Rch & Prof#=LtWekiva,LtWekiva        , 9
Up Type= 0
Dn Type= 0
Boundary for River Rch & Prof#=LtWekiva,LtWekiva        , 10
Up Type= 0
Dn Type= 0
Boundary for River Rch & Prof#=LtWekiva,LtWekiva        , 11
Up Type= 0
Dn Type= 0
Boundary for River Rch & Prof#=LtWekiva,LtWekiva        , 12
Up Type= 0
Dn Type= 0
Boundary for River Rch & Prof#=LtWekiva,LtWekiva        , 13
Up Type= 0
Dn Type= 0
Boundary for River Rch & Prof#=LtWekiva,LtWekiva        , 14
Up Type= 0
Dn Type= 0
Boundary for River Rch & Prof#=ROK,ROK             , 1
Up Type= 0
Dn Type= 0
Boundary for River Rch & Prof#=ROK,ROK             , 2
Up Type= 0
Dn Type= 0
Boundary for River Rch & Prof#=ROK,ROK             , 3
Up Type= 0
Dn Type= 0
Boundary for River Rch & Prof#=ROK,ROK             , 4
Up Type= 0
Dn Type= 0
Boundary for River Rch & Prof#=ROK,ROK             , 5
Up Type= 0
Dn Type= 0
Boundary for River Rch & Prof#=ROK,ROK             , 6
Up Type= 0
Dn Type= 0
Boundary for River Rch & Prof#=ROK,ROK             , 7
Up Type= 0
Dn Type= 0
Boundary for River Rch & Prof#=ROK,ROK             , 8
Up Type= 0
Dn Type= 0
Boundary for River Rch & Prof#=ROK,ROK             , 9
Up Type= 0
Dn Type= 0
Boundary for River Rch & Prof#=ROK,ROK             , 10
Up Type= 0
Dn Type= 0
Boundary for River Rch & Prof#=ROK,ROK             , 11
Up Type= 0
Dn Type= 0
Boundary for River Rch & Prof#=ROK,ROK             , 12
Up Type= 0
Dn Type= 0
Boundary for River Rch & Prof#=ROK,ROK             , 13
Up Type= 0
Dn Type= 0
Boundary for River Rch & Prof#=ROK,ROK             , 14
Up Type= 0
Dn Type= 0
Boundary for River Rch & Prof#=wekiva,wek_run         , 1
Up Type= 0
Dn Type= 0
Boundary for River Rch & Prof#=wekiva,wek_run         , 2
Up Type= 0
Dn Type= 0
Boundary for River Rch & Prof#=wekiva,wek_run         , 3
Up Type= 0
Dn Type= 0
Boundary for River Rch & Prof#=wekiva,wek_run         , 4
Up Type= 0
Dn Type= 0
Boundary for River Rch & Prof#=wekiva,wek_run         , 5
Up Type= 0
Dn Type= 0
Boundary for River Rch & Prof#=wekiva,wek_run         , 6
Up Type= 0
Dn Type= 0
Boundary for River Rch & Prof#=wekiva,wek_run         , 7
Up Type= 0
Dn Type= 0
Boundary for River Rch & Prof#=wekiva,wek_run         , 8
Up Type= 0
Dn Type= 0
Boundary for River Rch & Prof#=wekiva,wek_run         , 9
Up Type= 0
Dn Type= 0
Boundary for River Rch & Prof#=wekiva,wek_run         , 10
Up Type= 0
Dn Type= 0
Boundary for River Rch & Prof#=wekiva,wek_run         , 11
Up Type= 0
Dn Type= 0
Boundary for River Rch & Prof#=wekiva,wek_run         , 12
Up Type= 0
Dn Type= 0
Boundary for River Rch & Prof#=wekiva,wek_run         , 13
Up Type= 0
Dn Type= 0
Boundary for River Rch & Prof#=wekiva,wek_run         , 14
Up Type= 0
Dn Type= 0
Boundary for River Rch & Prof#=wekiva,wekiva_riv_up   , 1
Up Type= 0
Dn Type= 0
Boundary for River Rch & Prof#=wekiva,wekiva_riv_up   , 2
Up Type= 0
Dn Type= 0
Boundary for River Rch & Prof#=wekiva,wekiva_riv_up   , 3
Up Type= 0
Dn Type= 0
Boundary for River Rch & Prof#=wekiva,wekiva_riv_up   , 4
Up Type= 0
Dn Type= 0
Boundary for River Rch & Prof#=wekiva,wekiva_riv_up   , 5
Up Type= 0
Dn Type= 0
Boundary for River Rch & Prof#=wekiva,wekiva_riv_up   , 6
Up Type= 0
Dn Type= 0
Boundary for River Rch & Prof#=wekiva,wekiva_riv_up   , 7
Up Type= 0
Dn Type= 0
Boundary for River Rch & Prof#=wekiva,wekiva_riv_up   , 8
Up Type= 0
Dn Type= 0
Boundary for River Rch & Prof#=wekiva,wekiva_riv_up   , 9
Up Type= 0
Dn Type= 0
Boundary for River Rch & Prof#=wekiva,wekiva_riv_up   , 10
Up Type= 0
Dn Type= 0
Boundary for River Rch & Prof#=wekiva,wekiva_riv_up   , 11
Up Type= 0
Dn Type= 0
Boundary for River Rch & Prof#=wekiva,wekiva_riv_up   , 12
Up Type= 0
Dn Type= 0
Boundary for River Rch & Prof#=wekiva,wekiva_riv_up   , 13
Up Type= 0
Dn Type= 0
Boundary for River Rch & Prof#=wekiva,wekiva_riv_up   , 14
Up Type= 0
Dn Type= 0
Boundary for River Rch & Prof#=wekiva,wekiva_riv_down , 1
Up Type= 0
Dn Type= 1
Dn Known WS=-0.03
Boundary for River Rch & Prof#=wekiva,wekiva_riv_down , 2
Up Type= 0
Dn Type= 1
Dn Known WS=1.31
Boundary for River Rch & Prof#=wekiva,wekiva_riv_down , 3
Up Type= 0
Dn Type= 1
Dn Known WS=3.17
Boundary for River Rch & Prof#=wekiva,wekiva_riv_down , 4
Up Type= 0
Dn Type= 1
Dn Known WS=3.49
Boundary for River Rch & Prof#=wekiva,wekiva_riv_down , 5
Up Type= 0
Dn Type= 1
Dn Known WS=4.51
Boundary for River Rch & Prof#=wekiva,wekiva_riv_down , 6
Up Type= 0
Dn Type= 1
Dn Known WS=2.22
Boundary for River Rch & Prof#=wekiva,wekiva_riv_down , 7
Up Type= 0
Dn Type= 1
Dn Known WS=3.49
Boundary for River Rch & Prof#=wekiva,wekiva_riv_down , 8
Up Type= 0
Dn Type= 1
Dn Known WS=3.33
Boundary for River Rch & Prof#=wekiva,wekiva_riv_down , 9
Up Type= 0
Dn Type= 1
Dn Known WS=2.93
Boundary for River Rch & Prof#=wekiva,wekiva_riv_down , 10
Up Type= 0
Dn Type= 1
Dn Known WS=1.89
Boundary for River Rch & Prof#=wekiva,wekiva_riv_down , 11
Up Type= 0
Dn Type= 1
Dn Known WS=1.55
Boundary for River Rch & Prof#=wekiva,wekiva_riv_down , 12
Up Type= 0
Dn Type= 1
Dn Known WS=0.91
Boundary for River Rch & Prof#=wekiva,wekiva_riv_down , 13
Up Type= 0
Dn Type= 1
Dn Known WS=0.01
Boundary for River Rch & Prof#=wekiva,wekiva_riv_down , 14
Up Type= 0
Dn Type= 1
Dn Known WS=-0.14
DSS Import GetInterval= 0
DSS Import GetPeak= 0
DSS Import FillOption= 0

--- wekiva_ras.u02 (unsteady flow) ---

Flow Title=unsteady_BC_2009
Program Version=5.03
Use Restart= 0
Boundary Location=LtWekiva        ,LtWekiva        ,312.14  ,        ,                ,                ,                ,
Interval=1DAY
Flow Hydrograph= 182
    5.98    4.97    5.18    5.01    4.97    4.84    4.89    4.63    4.57    7.13
    18.1    11.7    11.2    14.3      14    12.9    11.9      11    10.3    9.75
    9.23    8.71    8.48    8.23    8.07    7.82    7.72    7.78    7.38    6.98
    10.6    8.01    7.48    7.32    6.98    6.81    6.71    6.44    6.69    6.68
    6.82    6.59    6.47    6.32     6.2     6.1     6.2     6.3     6.2     6.4
     6.3     6.5     6.6    6.68    6.83    7.02    7.17    6.99     7.1    7.15
    6.88    7.08    8.84    7.28    7.19    7.52    7.45    7.26    7.83    7.32
    10.1    9.07    8.22    9.13     7.8    7.43    7.36    6.47    5.99    5.28
    5.54    5.03    4.91    4.84     8.3    5.06     4.8    4.96    4.36    4.12
    4.04       4    3.43    3.29    3.14    2.86    2.32    2.11    1.95    1.58
    1.22     1.3    1.08     .75     .81      .8     .87     .58     .37     .32
      .2     .37      .3      .3     .17     .45     .25     .55    38.8     125
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Use DSS=False
Use Fixed Start Time=True
Fixed Start Date/Time=20JAN2009,2400
Is Critical Boundary=False
Boundary Location=ROK             ,ROK             ,480.77  ,        ,                ,                ,                ,
Interval=1DAY
Flow Hydrograph= 182
    55.8    55.6    55.5    55.4    55.4    55.4    55.4    55.6    55.9    56.1
    56.3      56    55.9    56.4    56.4    56.2    56.2    56.2    56.2    56.3
    56.3    56.4    56.4    56.4    56.2    56.1    55.9    55.8    55.7    55.9
    55.9    55.7    55.5    55.2    55.2    55.3    55.3    55.3    55.4    55.5
    55.4    55.1      55    55.1    55.1      55      55    54.8    54.6    54.4
    54.2      54      54    53.8    53.6    53.4    53.5    53.1    53.1      53
    52.8    52.6    52.8    52.8    52.8    52.5    52.3    52.3    52.4    52.3
    52.4    53.3    54.2    53.9    53.7    53.5    53.8    53.9    53.9    53.8
    53.6    53.3    53.3      53    53.4    53.3    53.2    53.1      53    52.8
    52.7    52.6    52.5    52.1      52    51.6    51.3    51.2    51.1    51.1
    51.1    50.8    50.6    50.4    50.1    50.1    50.1    49.8    49.6    49.5
    49.2    48.9    49.2    49.2    49.3    49.3    49.4    49.7      51      53
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Use DSS=False
Use Fixed Start Time=False
Fixed Start Date/Time=01JUN2008,2400
Is Critical Boundary=False
Boundary Location=wekiva          ,wek_run         ,793.32  ,        ,                ,                ,                ,
Interval=1DAY
Flow Hydrograph= 182
    67.3    66.8    66.4    66.4    66.5    66.4    66.3    66.4    66.6    66.5
    66.9    67.1    66.9    67.5    67.4    67.3    66.8    66.8      67      67
    67.1    67.4    67.3    66.9      67    67.1    66.8    66.9    66.7    66.8
      67    66.9    66.5    66.1    65.8    65.9    65.5    65.2    65.2    65.2
    64.8    64.8    64.4    64.1    63.8    63.7    63.6      63    62.9    62.8
    62.4    61.9    62.1    61.6    61.2    61.2    61.2    60.8    60.3    60.3
    59.9    59.6    59.8      60    59.8    59.4    59.5    59.3    58.9      59
    59.2    59.3    59.3    59.2    58.8    58.3    58.4    58.2    57.8    57.3
    57.2    57.1    56.7    56.9    57.3    57.5    57.1      57    56.9    56.7
    56.7      57    56.7    56.2    56.1    55.9    55.6    55.6    55.8    55.5
      55    54.9    54.8    54.5    54.4    54.4    54.2    53.9    53.8    53.6
    53.3    53.2    53.3    53.9      54    54.5    54.5    54.3    54.8    55.2
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Use DSS=False
Use Fixed Start Time=False
Fixed Start Date/Time=01JUN2008,2400
Is Critical Boundary=False
Boundary Location=wekiva          ,wekiva_riv_down ,0       ,        ,                ,                ,                ,
Interval=1HOUR
Stage Hydrograph= 4369
    -.46    -.54    -.54    -.51     -.6    -.66    -.61    -.56    -.53    -.56
    -.55    -.61    -.63    -.62    -.59     -.6     -.6    -.62    -.57    -.52
    -.53    -.54    -.52    -.53    -.52    -.51    -.51    -.51     -.5    -.52
    -.53    -.52    -.53    -.52    -.52    -.53    -.49    -.51    -.51    -.52
    -.51    -.52    -.52    -.51    -.51     -.5     -.5     -.5    -.49    -.49
    -.51    -.49    -.51    -.51    -.51    -.53    -.52    -.52    -.51    -.51
    -.51    -.52    -.51    -.51    -.52    -.53    -.52    -.51    -.52    -.51
    -.53    -.49    -.51    -.52    -.51    -.51    -.52    -.52    -.52    -.53
    -.53    -.52    -.53    -.53    -.52    -.52    -.52    -.53    -.54    -.54
    -.54    -.54    -.54    -.55    -.54    -.53    -.53    -.54    -.54    -.56
    -.55    -.55    -.56    -.56    -.57    -.57    -.56    -.57     -.6    -.58
    -.58    -.59    -.56    -.57    -.56    -.58    -.59    -.57    -.59     -.6
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Use DSS=False
Use Fixed Start Time=True
Fixed Start Date/Time=20JAN2009,0000
Is Critical Boundary=False
Boundary Location=LtWekiva        ,LtWekiva        ,250.47  ,        ,                ,                ,                ,
Interval=1DAY
Lateral Inflow Hydrograph= 182
   43.32   43.06   42.45   41.68   42.71   42.57   40.85   42.26   42.33   43.02
   46.11   43.72   43.67   44.85   43.92   44.32    43.9   43.55   43.42   43.11
   41.84    42.6   42.49   42.28   42.56   42.35   42.44   41.74   42.21    42.1
   42.79   42.36   42.16   42.05   41.79   41.78   41.78   41.68   41.77   41.57
   41.68   41.46   41.58   41.47   41.07   41.19   41.18    41.3   41.41   41.31
   40.81   40.31    40.8   40.92   40.81   41.15   41.38   41.05   40.34   40.67
   40.35   40.48   41.08   41.06   40.85   40.37   41.05   40.75   41.12   40.68
   40.52   40.69   41.19   41.22   40.98   40.97   40.66   40.77   40.74   40.11
    40.6   40.26   40.17   39.94   41.36    40.3   39.99   39.88   40.07   39.96
   40.54    40.5   40.36   39.66   40.17   40.19   40.07   40.48   40.58   40.17
   39.75   40.08   39.56   39.43   37.82   37.65   37.72   37.61    39.3   38.99
   38.77    38.6   39.21   39.56   38.79   39.55   39.13   38.69   43.47   68.99
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Use DSS=False
Use Fixed Start Time=True
Fixed Start Date/Time=20JAN2009,2400
Is Critical Boundary=False
Boundary Location=LtWekiva        ,LtWekiva        ,182.49  ,        ,                ,                ,                ,
Interval=1DAY
Lateral Inflow Hydrograph= 182
    1.61    1.61    1.61     1.6    1.59    1.57    1.56    1.55    1.54     4.8
    9.24    3.38    2.43    4.39    3.59    2.51    2.23    2.04    1.88    1.76
    1.68    1.64     1.6    1.58    1.55    1.52    1.51     1.5    1.48    1.47
    2.45    1.75    1.54     1.5    1.47    1.45    1.44    1.42    1.41    1.39
    1.38    1.36    1.37    1.36    1.35    1.33    1.32    1.31    1.29    1.28
    1.27    1.26    1.25    1.24    1.23    1.22    1.21    1.21    1.21     1.2
    1.19    1.19    1.53    1.26    1.19    1.18    1.17    1.15    1.54    1.24
    1.24    2.08    1.59    1.22    1.17    1.14    1.13    1.11    1.12     1.1
    1.08    1.06    1.06    1.05    2.77    1.45    1.13    1.09    1.07    1.05
    1.78    1.24    1.07    1.04    1.01     .99     .97     .98     .97     .96
     .95     .94     .92     .91     .91     .91      .9     .89     .89     .88
     .87     .87     .86    2.26    1.31     .89     .86    1.15    14.9   56.15
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Use DSS=False
Use Fixed Start Time=False
Is Critical Boundary=False
Boundary Location=LtWekiva        ,LtWekiva        ,143.98  ,30.50   ,                ,                ,                ,
Interval=1DAY
Uniform Lateral Inflow Hydrograph= 182
     3.7     3.7    3.68    3.65    3.63    3.61    3.58    3.56    3.55    9.69
   14.46    6.38    5.61   10.01     7.3    6.59    5.82    5.15     4.6    4.17
    3.91    3.82    3.74    3.68    3.61    3.56    3.51     3.5    3.45    3.43
    5.12    3.44    3.44    3.38    3.34    3.32    3.31    3.29    3.27    3.24
    3.22    3.19    3.21    3.18    3.17    3.14    3.11     3.1    3.07    3.05
    3.04    3.02    3.01    2.99    2.97    2.95    2.93    2.93    2.92     2.9
    2.87    2.88    3.41    2.85    2.82    2.79    2.79    2.76    3.39    2.76
    2.92    4.46    2.71    2.68    2.65    2.63    2.63     2.6    2.64     2.6
    2.56    2.54    2.54    2.54     5.4    2.54     2.5    2.48    2.47    2.45
    3.75    2.45    2.42     2.4    2.37    2.35    2.34    2.36    2.34    2.33
    2.32    2.29    2.26    2.24    2.24    2.23    2.21     2.2    2.19    2.17
    2.15    2.14    2.13    4.78    2.14    2.13    2.12    3.02   26.87  145.08
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Use DSS=False
Use Fixed Start Time=False
Is Critical Boundary=False
Boundary Location=ROK             ,ROK             ,350.27  ,        ,                ,                ,                ,
Interval=1DAY
Lateral Inflow Hydrograph= 182
     .55     .53     .53     .52     .49     .46     .42     .39     .36     .77
     2.7    2.47    2.06    2.09    2.37    2.04     1.8    1.62    1.47    1.33
    1.21    1.11    1.02     .95     .89     .82     .77     .77     .74     .71
     .88    1.01      .9     .81     .72     .65     .61     .58     .54     .49
     .48     .44      .4     .39     .37     .34      .3     .25     .21     .17
     .13      .1     .08     .06     .05     .03     .02     .01     .01     .02
     .01     .01     .17      .2     .14     .07     .03     .01      .1     .16
     .13     .33     .46     .31     .16     .05       0       0       0       0
       0       0       0       0     .05     .09     .04       0       0       0
       0       0       0       0       0       0       0       0       0       0
       0       0       0       0       0       0       0       0       0       0
       0       0       0       0       0       0       0       0     .18    6.03
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Use DSS=False
Use Fixed Start Time=False
Is Critical Boundary=False
Boundary Location=ROK             ,ROK             ,18.17   ,        ,                ,                ,                ,
Interval=1DAY
Lateral Inflow Hydrograph= 182
    6.37    6.25    6.18    6.08    5.96    5.81    5.65     5.5    5.36    6.28
   12.05    13.4   13.52   14.17   15.61    15.3   14.84    14.3   13.69   13.02
   12.36   11.72   11.13   10.58   10.06    9.56    9.13    8.83    8.52    8.21
    8.43    8.83    8.61    8.37    8.05    7.74    7.49    7.25    7.01    6.76
    6.57    6.35    6.12    5.97     5.8    5.62    5.42     5.2    4.99    4.79
    4.58    4.39    4.22    4.08    3.93    3.79    3.65    3.56    3.52    3.47
    3.38    3.35    3.76    3.91    3.84    3.69    3.53    3.38    3.62    3.85
    3.83    4.33    4.93     4.8    4.53    4.18    3.92     3.7    3.52    3.41
     3.2    2.93    2.72    2.59    3.53    4.37    4.26    4.02    3.76    3.49
    3.58    3.98    3.78    3.53    3.22    2.88    2.57    2.37    2.25    2.13
    2.04    1.93    1.77    1.58    1.42    1.31    1.21    1.11    1.01     .91
     .81     .71     .64    1.32    2.36    2.41    2.36    2.33    7.24   27.93
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Use DSS=False
Use Fixed Start Time=False
Is Critical Boundary=False
Boundary Location=ROK             ,ROK             ,350.27  ,215.81  ,                ,                ,                ,
Interval=1DAY
Uniform Lateral Inflow Hydrograph= 182
   12.64   12.67   12.63   12.52   12.43   12.34   12.24    12.2   12.13   12.72
   13.32   12.71   12.63   13.02   12.73    12.7   12.66   12.61   12.47   12.38
   12.29   12.23   12.16   12.11      12   11.91   11.89   11.96    11.8   11.79
   11.87   11.66   11.74   11.57   11.46   11.47   11.44   11.36   11.28   11.19
   11.12   10.95   11.14   10.99   10.95   10.84   10.73   10.67   10.59   10.51
   10.44   10.39   10.35   10.29   10.19   10.15   10.08   10.11   10.09    9.99
    9.89    9.83    9.94    9.88    9.75    9.61    9.62    9.51    9.48    9.57
    9.46    9.45    9.35    9.23    9.11    9.05    9.06    8.95     9.2    9.02
    8.81    8.71    8.76    8.77    9.02    8.86    8.61    8.56     8.5    8.44
    8.49    8.45    8.37    8.26    8.12    8.05    7.99    8.16    8.05    8.02
    7.98    7.85    7.72    7.62    7.63    7.62     7.5    7.47    7.41    7.32
    7.27    7.21    7.17    7.61    7.31    7.26    7.22    7.19    9.33   15.92
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Use DSS=False
Use Fixed Start Time=False
Is Critical Boundary=False
Boundary Location=wekiva          ,wekiva_riv_up   ,711.81  ,579.74  ,                ,                ,                ,
Interval=1DAY
Uniform Lateral Inflow Hydrograph= 182
    4.29    4.29    4.27    4.24     4.2    4.18    4.15    4.13     4.1    8.82
    19.8   13.37   10.74    14.7   15.52   13.33   10.89     8.8    7.09    5.74
    4.83    4.38    4.25    4.19    4.13    4.08    4.06    4.05    3.99    3.96
    5.23    3.92    3.92    3.88    3.85    3.84    3.83     3.8    3.78    3.75
    3.73    3.68    3.71    3.67    3.65    3.62    3.59    3.57    3.55    3.52
     3.5    3.48    3.47    3.44    3.42     3.4    3.38    3.38    3.36    3.34
    3.31    3.31    3.72    3.28    3.25    3.22    3.21    3.18    3.66    3.18
    3.29    4.46    3.12    3.09    3.06    3.04    3.03    3.01    3.05    3.01
    2.96    2.93    2.94    2.93    5.12    2.94    2.88    2.87    2.85    2.83
    3.82    2.82     2.8    2.77    2.74    2.72     2.7    2.73    2.71    2.69
    2.68    2.65    2.62    2.59    2.59    2.58    2.56    2.54    2.53     2.5
    2.49    2.47    2.46     4.5    2.47    2.46    2.45    3.13    25.2  247.53
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Use DSS=False
Use Fixed Start Time=False
Is Critical Boundary=False
Boundary Location=wekiva          ,wekiva_riv_down ,508.92  ,370.65  ,                ,                ,                ,
Interval=1DAY
Uniform Lateral Inflow Hydrograph= 182
    8.53    8.53    8.49    8.42    8.36     8.3    8.24     8.2    8.15   12.93
    17.5   11.26   10.52   13.98    12.1   11.46   10.75   10.11    9.53    9.05
    8.66     8.4    8.22    8.11    8.01    7.96    7.93    7.95    7.86    7.84
     9.1    7.76    7.78    7.69    7.62    7.61    7.58    7.53    7.48    7.42
    7.37    7.28    7.34    7.26    7.23    7.16     7.1    7.05       7    6.95
    6.91    6.87    6.84     6.8    6.74    6.71    6.67    6.66    6.63    6.58
    6.52     6.5    6.92    6.47     6.4    6.34    6.33    6.27    6.73    6.26
    6.35     7.5    6.14    6.07    6.02    5.98    5.97    5.92       6    5.92
    5.83    5.78    5.79    5.78    7.99    5.78    5.68    5.64    5.61    5.58
    6.56    5.56    5.51    5.46    5.39    5.35    5.32    5.38    5.32     5.3
    5.27    5.21    5.15    5.11     5.1    5.08    5.03    5.01    4.98    4.93
     4.9    4.87    4.84    6.95    4.87    4.84    4.81    5.48   24.51  115.81
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Use DSS=False
Use Fixed Start Time=False
Is Critical Boundary=False
Boundary Location=wekiva          ,wekiva_riv_down ,386.11  ,        ,                ,                ,                ,
Interval=1DAY
Lateral Inflow Hydrograph= 182
   13.54   13.48   13.44   13.44   13.42   13.37   13.32   13.34   13.33   13.31
   13.45   13.49    13.5   13.58   13.59   13.57    13.5   13.51   13.48   13.45
   13.43   13.44    13.4   13.35   13.32   13.32   13.27   13.24   13.24   13.23
   13.21   13.21   13.21   13.17   13.15   13.16   13.11   13.08   13.09   13.07
   13.05   13.04   13.03   13.01   12.96   12.93   12.91   12.87   12.88   12.88
   12.84   12.77   12.78   12.74   12.68   12.67   12.67   12.64    12.6   12.58
   12.54   12.49   12.54   12.58   12.55    12.5   12.54   12.51   12.47    12.5
   12.62   12.68    12.7   12.69   12.66   12.62    12.6   12.58   12.54   12.49
   12.45    12.4   12.37   12.38   12.45   12.49   12.45   12.41   12.39   12.35
   12.37   12.39   12.34   12.24   12.22   12.16   12.11   12.08   12.09   12.05
   11.97   11.95   11.94   11.87   11.84   11.84   11.79   11.71   11.69   11.63
   11.56   11.55    11.6   11.72   11.71   11.79   11.76   11.72   11.92   12.37
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Use DSS=False
Use Fixed Start Time=False
Is Critical Boundary=False
Boundary Location=wekiva          ,wekiva_riv_down ,370.65  ,        ,                ,                ,                ,
Interval=1DAY
Lateral Inflow Hydrograph= 182
     .57     .55     .53     .52      .5     .49     .47     .45     .43     .46
     .65     .68     .67     .69     .74     .73     .73     .72     .71      .7
     .68     .67     .66     .64     .63     .61     .59     .58     .57     .55
     .56     .57     .55     .54     .52     .51     .49     .48     .47     .45
     .44     .42     .41      .4     .38     .37     .35     .34     .32      .3
     .29     .27     .26     .24     .23     .21      .2     .18     .17     .16
     .15     .14     .15     .15     .14     .12     .11      .1      .1     .11
      .1     .11     .13     .12     .11     .09     .08     .07     .06     .05
     .04     .03     .01       0     .03     .05     .04     .03     .02     .01
     .01     .02     .01       0       0       0       0       0       0       0
       0       0       0       0       0       0       0       0       0       0
       0       0       0       0       0       0       0       0     .02     .58
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Use DSS=False
Use Fixed Start Time=False
Is Critical Boundary=False
Boundary Location=wekiva          ,wekiva_riv_down ,344.64  ,322.22  ,                ,                ,                ,
Interval=1DAY
Uniform Lateral Inflow Hydrograph= 182
    2.32    2.32    2.31    2.29    2.28    2.26    2.24    2.23    2.22    3.52
    4.76    3.07    2.86    3.81    3.29    3.12    2.93    2.75     2.6    2.46
    2.36    2.29    2.24    2.21    2.18    2.17    2.16    2.16    2.14    2.13
    2.48    2.11    2.12    2.09    2.08    2.07    2.06    2.05    2.04    2.02
    2.01    1.98       2    1.98    1.97    1.95    1.93    1.92    1.91    1.89
    1.88    1.87    1.86    1.85    1.84    1.83    1.81    1.81    1.81    1.79
    1.78    1.77    1.88    1.76    1.74    1.73    1.72    1.71    1.83     1.7
    1.73    2.04    1.67    1.65    1.64    1.63    1.63    1.61    1.63    1.61
    1.59    1.57    1.58    1.57    2.18    1.57    1.55    1.54    1.53    1.52
    1.79    1.51     1.5    1.49    1.47    1.46    1.45    1.46    1.45    1.44
    1.44    1.42     1.4    1.39    1.39    1.38    1.37    1.36    1.35    1.34
    1.33    1.33    1.32    1.89    1.33    1.32    1.31    1.49    6.67   31.53
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Use DSS=False
Use Fixed Start Time=False
Is Critical Boundary=False
Boundary Location=wekiva          ,wekiva_riv_down ,143.23  ,        ,                ,                ,                ,
Interval=1DAY
Lateral Inflow Hydrograph= 182
     .71     .68     .67     .65     .62      .6     .58     .55     .53      .7
    1.81    1.89     1.8    1.89    2.14    2.03    1.94    1.85    1.76    1.67
    1.58    1.49    1.41    1.33    1.26    1.18    1.12    1.06    1.01     .95
     .99    1.04     .98     .93     .87     .82     .77     .73     .68     .64
      .6     .56     .52     .49     .46     .43     .39     .36     .33      .3
     .27     .24     .22      .2     .18     .15     .14     .12     .11     .09
     .08     .07      .1      .1     .09     .07     .06     .05     .07     .08
     .07     .13      .2     .18     .15     .12      .1     .08     .06     .04
     .03     .01       0       0     .11     .19     .15     .12      .1     .07
     .09     .14     .11     .09     .06     .04     .02     .01       0       0
       0       0       0       0       0       0       0       0       0       0
       0       0       0       0       0       0       0       0     .79    5.36
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Use DSS=False
Use Fixed Start Time=False
Is Critical Boundary=False
Boundary Location=wekiva          ,wekiva_riv_down ,276.66  ,25.630* ,                ,                ,                ,
Interval=1DAY
Uniform Lateral Inflow Hydrograph= 182
    3.83    3.83    3.81    3.78    3.76    3.73    3.71    3.69    3.67    3.93
    5.97    5.55    4.99     5.3    5.85    5.41    4.95    4.56    4.23    3.97
    3.78    3.69    3.65    3.64    3.61    3.58    3.57    3.57    3.53    3.52
    3.56    3.48    3.48    3.45    3.42    3.41     3.4    3.38    3.36    3.33
    3.31    3.28     3.3    3.27    3.25    3.23     3.2    3.18    3.16    3.14
    3.12    3.11     3.1    3.08    3.06    3.04    3.02    3.02    3.01    2.99
    2.96    2.95    2.97    2.94    2.91    2.88    2.88    2.85    2.86    2.85
    2.83    2.86    2.79    2.76    2.74    2.72    2.71    2.69    2.73    2.69
    2.65    2.63    2.63    2.63    2.73    2.63    2.58    2.56    2.55    2.53
    2.57    2.52     2.5    2.48    2.45    2.43    2.42    2.44    2.42    2.41
     2.4    2.37    2.34    2.32    2.32    2.31    2.28    2.28    2.26    2.24
    2.23    2.21     2.2    2.33    2.21     2.2    2.19     2.2    4.13   47.73
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Use DSS=False
Use Fixed Start Time=False
Is Critical Boundary=False
Boundary Location=wekiva          ,wekiva_riv_down ,25.630* ,        ,                ,                ,                ,
Interval=1DAY
Lateral Inflow Hydrograph= 182
   87.81   87.78   88.48   88.88   88.62   87.88   86.71   85.25   84.16   85.56
   96.46   99.77  100.77  102.23   106.2  107.46  107.89  107.04  104.93  101.87
   98.61   95.73   93.49   91.81   90.39   88.96   87.74   87.22   86.69    85.9
   86.19   86.41   85.49   84.89   83.53   82.42   82.07   81.82   81.27   80.51
   79.85   78.87   78.13   78.51   78.26   77.72   76.76   75.76   74.93   74.19
   73.48   72.87   72.44   72.15   71.71   71.13   70.67   70.52    70.8   70.84
   70.31   69.66   70.18   70.83   70.64   69.66    68.7   68.19   68.26   68.91
   69.17   69.97   71.06   70.39   69.22   68.11   67.48   67.17    67.3   67.88
   67.13   66.02   65.27   65.02   66.42   68.43   68.07   66.62    65.5   64.78
   64.68   65.35   64.88    64.1   63.22    62.4   61.76   61.47   61.49   61.35
   61.15   60.83   60.25   59.58    59.1   58.89   58.67   58.32   57.96   57.58
   57.18    56.8   56.78   58.15   59.95    59.1    58.3    57.8   63.56  114.56
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Use DSS=False
Use Fixed Start Time=False
Is Critical Boundary=False
Boundary Location=wekiva          ,wekiva_riv_up   ,747.19  ,        ,                ,                ,                ,
Interval=1DAY
Lateral Inflow Hydrograph= 182
     .61      .6     .58     .57     .55     .54     .53     .51      .5    3.28
    4.71    1.21    1.17    3.01     1.4    1.35    1.31    1.26    1.22    1.18
    1.14    1.11    1.07    1.04       1     .97     .94     .91     .88     .86
    1.62      .9     .88     .85     .82      .8     .77     .75     .73     .71
     .69     .66     .65     .63     .61      .6     .58     .56     .55     .53
     .52      .5     .49     .48     .46     .45     .44     .43     .42     .41
      .4      .4     .64     .39     .38     .37     .36     .35     .64     .36
     .43    1.14     .38     .37     .36     .35     .34     .33     .33     .32
     .31      .3     .29     .29    1.57     .32     .31      .3      .3     .29
     .87      .3     .29     .29     .28     .27     .26     .26     .26     .25
     .25     .24     .24     .23     .23     .22     .22     .22     .21     .21
     .21     .21     .21    1.38     .22     .22     .21     .62   10.74   21.46
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Use DSS=False
Use Fixed Start Time=False
Is Critical Boundary=False
Observed RC=SR464,LtWekiva        ,LtWekiva        ,312.14  ,0
Observed RC Data= 99
    22.3    5.98   22.24    4.97   22.24    4.89   22.22    4.57   22.76    18.1
   22.56    11.2   22.68      14   22.61    11.9   22.56    10.3   22.53    9.23
    22.5    8.48   22.49    7.82    22.5    7.72   22.51    7.78   22.48    6.98
   22.62    10.6   22.54    8.01   22.52    7.48    22.5    6.81   22.51    6.69
   22.51    6.68   22.52    6.59   22.52     6.2   22.55     6.2   22.57     6.6
   22.58    6.68   22.59    6.83    22.6    7.02   22.61    7.17   22.61    6.99
   22.63    7.15   22.62    6.88   22.63    7.08   22.72    8.84   22.67    7.52
   22.67    7.45    22.7    7.83   22.68    7.32    22.8    10.1   22.77    9.07
   22.74    8.22   22.73     7.8   22.67    6.47   22.63    5.54   22.61    4.91
   22.77     8.3   22.63    5.06   22.63    4.96    22.6    4.36   22.59    4.04
   22.56    3.43   22.55    3.29   22.55    3.14   22.49    2.32   22.48    2.11
   22.46    1.95   22.43    1.58    22.4     1.3   22.37    1.08   22.33     .81
   22.33      .8   22.29     .58   22.26     .37   22.22      .2   22.25     .37
   22.24      .3   22.21     .17   22.28     .45   22.25     .55   23.32    38.8
   24.72     125   25.64     207   26.42     298   26.67     340   26.49     322
   26.16     286   26.16     286   26.29     300    26.1     279   25.85     253
   25.63     231   25.18     189   24.73     151    23.5    65.1   24.02    97.8
   24.62     142   23.56    68.5   23.03    41.2   23.21    50.6   22.98      39
   22.69    27.1   22.74    28.8   24.06     100   24.73     151   23.61    71.4
   23.28    53.1   22.99    39.3   23.16    47.4    23.3    54.3
Observed RC Point Data= 182
            22.3            5.98
           22.24            4.97
           22.25            5.18
           22.24            5.01
           22.24            4.97
           22.23            4.84
           22.24            4.89
           22.22            4.63
           22.22            4.57
           22.34            7.13
           22.76            18.1
           22.57            11.7
           22.56            11.2
           22.67            14.3
           22.68             14.
           22.64            12.9
           22.61            11.9
           22.58             11.
           22.56            10.3
           22.54            9.75
           22.53            9.23
           22.51            8.71
            22.5            8.48
            22.5            8.23
            22.5            8.07
           22.49            7.82
            22.5            7.72
           22.51            7.78
           22.49            7.38
           22.48            6.98
           22.62            10.6
           22.54            8.01
           22.52            7.48
           22.52            7.32
            22.5            6.98
            22.5            6.81
            22.5            6.71
           22.49            6.44
           22.51            6.69
           22.51            6.68
           22.52            6.82
           22.52            6.59
           22.51            6.47
           22.51            6.32
           22.52             6.2
           22.53             6.1
           22.54             6.2
           22.55             6.3
           22.55             6.2
           22.55             6.4
           22.56             6.3
           22.57             6.5
           22.57             6.6
           22.58            6.68
           22.59            6.83
            22.6            7.02
           22.61            7.17
           22.61            6.99
           22.62             7.1
           22.63            7.15
           22.62            6.88
           22.63            7.08
           22.72            8.84
           22.65            7.28
           22.65            7.19
           22.67            7.52
           22.67            7.45
           22.67            7.26
            22.7            7.83
           22.68            7.32
            22.8            10.1
           22.77            9.07
           22.74            8.22
           22.78            9.13
           22.73             7.8
           22.71            7.43
           22.71            7.36
           22.67            6.47
           22.65            5.99
           22.62            5.28
           22.63            5.54
           22.61            5.03
           22.61            4.91
           22.61            4.84
           22.77             8.3
           22.63            5.06
           22.62             4.8
           22.63            4.96
            22.6            4.36
           22.59            4.12
           22.59            4.04
           22.59              4.
           22.56            3.43
           22.55            3.29
           22.55            3.14
           22.53            2.86
           22.49            2.32
           22.48            2.11
           22.46            1.95
           22.43            1.58
           22.39            1.22
            22.4             1.3
           22.37            1.08
           22.33            0.75
           22.33            0.81
           22.33             0.8
           22.33            0.87
           22.29            0.58
           22.26            0.37
           22.25            0.32
           22.22             0.2
           22.25            0.37
           22.25             0.3
           22.24             0.3
           22.21            0.17
           22.28            0.45
           22.24            0.25
           22.25            0.55
           23.32            38.8
           24.72            125.
           25.64            207.
           26.42            298.
           26.67            340.
           26.49            322.
           26.16            286.
           26.16            286.
           26.29            300.
            26.1            279.
           25.85            253.
           25.63            231.
           25.18            189.
           24.73            151.
           24.39            124.
           24.04            99.9
            23.5            65.1
           23.63            76.1
           23.74            79.5
           24.02            97.8
           24.36            122.
           24.75            152.
           24.62            142.
           24.13            105.
           23.88            88.2
           23.56            68.5
            23.3            54.4
           23.12            45.1
           23.03            41.2
           22.99            39.4
           23.16            47.1
           23.21            50.6
           22.98             39.
           22.88            34.5
           22.78            30.3
           22.69            27.1
           22.84            34.6
           22.78            30.5
           22.74            28.8
           23.45            68.8
            24.1            103.
           24.06            100.
           23.85            86.6
           24.16            110.
           24.77            154.
            24.9            165.
           24.73            151.
           24.29            117.
           23.87            87.5
           23.61            71.4
           23.55            67.9
           23.36            57.3
           23.28            53.1
           23.25            51.7
           23.21            49.8
           23.06            42.7
           22.98            38.9
           22.93            36.9
            22.8            31.5
           22.99            39.3
           23.11            45.2
           23.16            47.4
            23.3            54.3
           23.39            59.2

--- wekiva_ras.g01 (geometry) ---

Geom Title=wekiva_ras_2018_ft_10
Program Version=5.03

Junct Name=Junc_LtWek
Junct Desc=, 0 , 0 ,-1 ,0
Up River,Reach=LtWekiva        ,LtWekiva
Up River,Reach=wekiva          ,wekiva_riv_up
Dn River,Reach=wekiva          ,wekiva_riv_down
Junc L&A=0,0
Junc L&A=0,0

Junct Name=Junc_Rok
Junct Desc=, 0 , 0 ,-1 ,0
Up River,Reach=ROK             ,ROK
Up River,Reach=wekiva          ,wek_run
Dn River,Reach=wekiva          ,wekiva_riv_up
Junc L&A=0,
Junc L&A=0,

River Reach=LtWekiva        ,LtWekiva
Reach XY= 30
 461210.722404883173468.02397002461399.0711048793173813.90187002
 461544.923404883173878.29017002 461756.951404883174153.97287002
 461853.759004883174572.90287002461738.7675048793174868.43627002
 461763.894404883174995.06247002 461680.720004883175051.39747002
461678.4189048793175299.57177002461223.1042048793175685.60017002
 461168.883004883176184.43507002 460980.871804883176547.67637002
 461078.951904883176785.36127002460994.0494048793177093.09957002
 461077.364904883177299.00777002461005.9516048793177446.19837002
 461043.245204883177602.24967002 461235.178304883177804.45507002
 461242.721704883178033.17637002461172.4933048793178132.16257002
 461215.341304883178335.29367002 460941.987104883178505.89197002
460679.7417048793178874.86057002460311.0410048793179183.65647002
 460274.997604883179507.23687002 460017.978804883180055.95667002
459571.6459048793180558.36217002 459450.507804883180840.31237002
459486.1704048793180920.25557002 459343.436962483181018.99032073

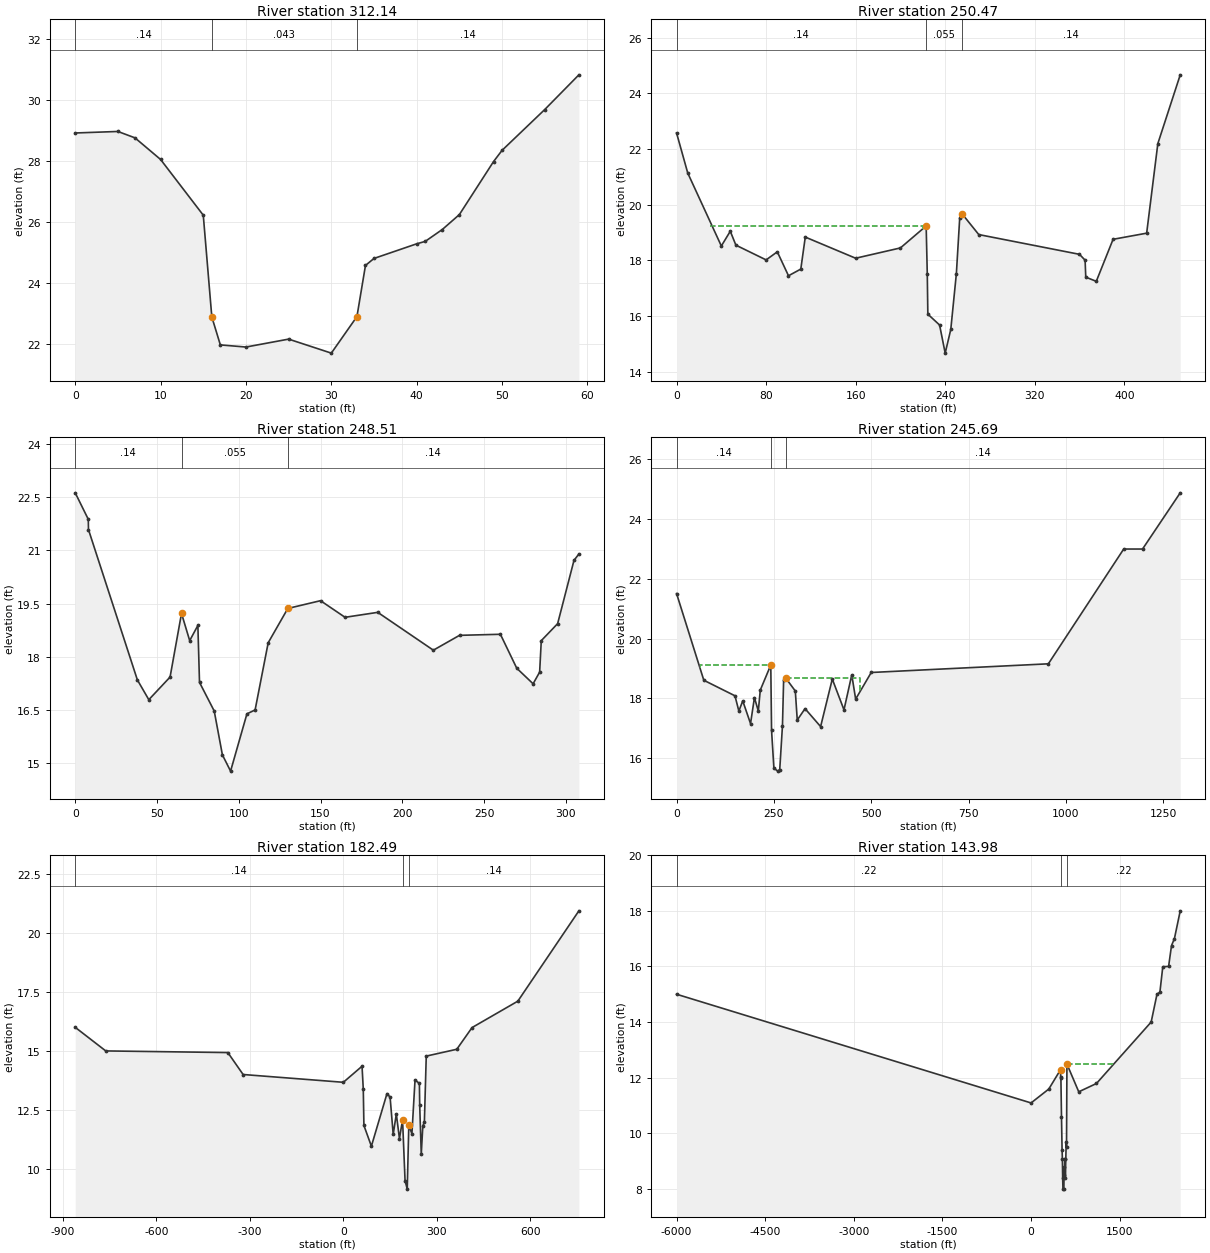
Type RM Length L Ch R = 1 ,312.14  ,6167.191,6167.191,6167.191
BEGIN DESCRIPTION:
TheSprings
END DESCRIPTION:
Node Name=TheSprings
XS GIS Cut Line= 2
461204.5570048793173492.65727002461225.0887048793173489.69387002
#Sta/Elev= 21
       0   28.92       5   28.97       7   28.76      10   28.05      15   26.22
      16   22.88      17   21.96      20   21.89      25   22.15      30   21.69
      33   22.89      34   24.57      35    24.8      40   25.28      41   25.36
      43   25.75      45   26.24      49   27.98      50   28.35      55   29.69
      59   30.83
#Mann= 3 , 0 , 0
       0     .14       0      16    .043       0      33     .14       0
Bank Sta=16,33
XS Rating Curve= 0 ,0
Exp/Cntr=0.3,0.1

Type RM Length L Ch R = 1 ,250.47  ,195.8661,195.8661,195.8661
BEGIN DESCRIPTION:
MFL_SLB_south
END DESCRIPTION:
Node Name=MFL_SLB_south
XS GIS Cut Line= 2
 461695.722804883174963.91247002461744.7818048793175039.17377002
#Sta/Elev= 30
       0   22.58      10   21.14      40   18.52      48   19.05      53   18.55
      80   18.02      90   18.31     100   17.45     111   17.69     115   18.84
     160   18.08     200   18.45     223   19.24     224   17.51   224.5   16.07
     235   15.68     240   14.67     245   15.52     250   17.53     253   19.54
     255   19.68     270   18.93     360   18.22     365   18.01   365.6    17.4
     375   17.25     390   18.76     420   18.98     430    22.2     450   24.67
#Mann= 3 , 0 , 0
       0     .14       0     223    .055       0     255     .14       0
#XS Ineff= 2 ,-1
      30     220   19.24     255     425   19.68
Permanent Ineff=
       F       F
Bank Sta=223,255
XS Rating Curve= 0 ,0
Exp/Cntr=0.3,0.1

Type RM Length L Ch R = 1 ,248.51  ,282.3819,282.3819,282.3819
BEGIN DESCRIPTION:
MFL_SLB_bridge
END DESCRIPTION:
Node Name=MFL_SLB_bridge
XS GIS Cut Line= 2
461657.0487048793175034.72957002461736.0472048793175081.44547002
#Sta/Elev= 30
       0   22.63       8   21.88     8.1   21.59      38   17.34      45   16.78
      58   17.42      65   19.22      70   18.45      75   18.88      76   17.27
      85   16.46      90   15.22      95   14.76     105   16.38     110   16.49
     118   18.39     130   19.36     150   19.58     165   19.11     185   19.25
     219   18.18     235    18.6     260   18.63     270   17.67     280   17.23
     284   17.56     285   18.45     295   18.93     305   20.72     308    20.9
#Mann= 3 , 0 , 0
       0     .14       0      65    .055       0     130     .14       0
#XS Ineff= 2 ,-1
      20      65   19.22     130     300   19.36
Permanent Ineff=
       F       F
Bank Sta=65,130
XS Rating Curve= 0 ,0
Exp/Cntr=0.3,0.1

Type RM Length L Ch R = 1 ,245.69  ,6319.948,6319.948,6319.948
BEGIN DESCRIPTION:
MFL_SLB_north
END DESCRIPTION:
Node Name=MFL_SLB_north
XS GIS Cut Line= 3
461616.7210048793175109.23877002 461714.682104883175129.98127002
462481.3654001193175292.32048682
#Sta/Elev= 30
       0   21.51      70   18.61     150   18.09     160   17.58     170   17.92
     190   17.16     200   18.03     210   17.58     215   18.28     242   19.12
     244   16.93     250   15.67     260   15.57     265   15.62     272   17.09
     275   18.62     280   18.69     305   18.25     310   17.28     330   17.66
     370   17.06     400   18.65     430   17.62     450   18.79     460   17.98
     500   18.87  954.95   19.16 1148.51      23  1196.9      23 1293.68   24.88
#Mann= 3 , 0 , 0
       0     .14       0     242    .055       0     280     .14       0
#XS Ineff= 2 ,-1
      60     242   19.12     280     470   18.69
Permanent Ineff=
       F       F
Bank Sta=242,280
XS Rating Curve= 0 ,0
Exp/Cntr=0.3,0.1

Type RM Length L Ch R = 1 ,182.49  ,3850.361,3850.361,3850.361
BEGIN DESCRIPTION:
MFL_Sabol
MFL_Sabol
END DESCRIPTION:
Node Name=MFL_Sabol
XS GIS Cut Line= 2
 460724.291904883176565.62067002 461198.426104883176557.15397002
#Sta/Elev= 30
 -860.09      16 -762.17      15 -370.47   14.93 -321.51      14       0   13.67
      60   14.35      64   13.38      66   11.84      90   10.96     140   13.19
     150   13.04     160   11.46     170   12.33     180   11.28     190   12.08
     198     9.5     205    9.14     210   11.84     220   11.49     230   13.77
     244   13.62     245   12.69     250   10.62     255   11.82     260   11.99
     266   14.78  363.96   15.07  412.92   15.99  559.81   17.11  755.66   20.94
#Mann= 3 , 0 , 0
 -860.09     .14       0     190    .055       0     210     .14       0
#XS Ineff= 1 ,-1
      64     120   12.08
Permanent Ineff=
       F
Bank Sta=190,210
XS Rating Curve= 0 ,0
Exp/Cntr=0.3,0.1

Type RM Length L Ch R = 1 ,143.98  ,3642.73,3642.73,3642.73
BEGIN DESCRIPTION:
LW2
END DESCRIPTION:
Node Name=LW2
XS GIS Cut Line= 2
 460933.299004883177665.03007002461212.6995048793177544.37987002
#Sta/Elev= 30
   -6000      15       0   11.09     300   11.59     500   12.29   501.5   12.01
     505   11.99     515   10.59     525    9.39     530    9.09     535    8.39
     540    7.99     555    7.99     560    8.79     565    8.49     570    9.09
     575    9.09     580    8.39     595    9.69     600    9.49     607   12.49
     807   11.49    1107   11.79 2032.79      14 2131.16      15 2180.35   15.07
 2229.53   15.99 2327.91      16 2377.09   16.75 2426.28      17 2524.65      18
#Mann= 3 , 0 , 0
   -6000     .22       0     500      .2       0     607     .22       0
#XS Ineff= 2 ,-1
   -2000     500   12.29     607    1400   12.49
Permanent Ineff=
       F       F
Bank Sta=500,607
XS Rating Curve= 0 ,0
Exp/Cntr=0.3,0.1

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
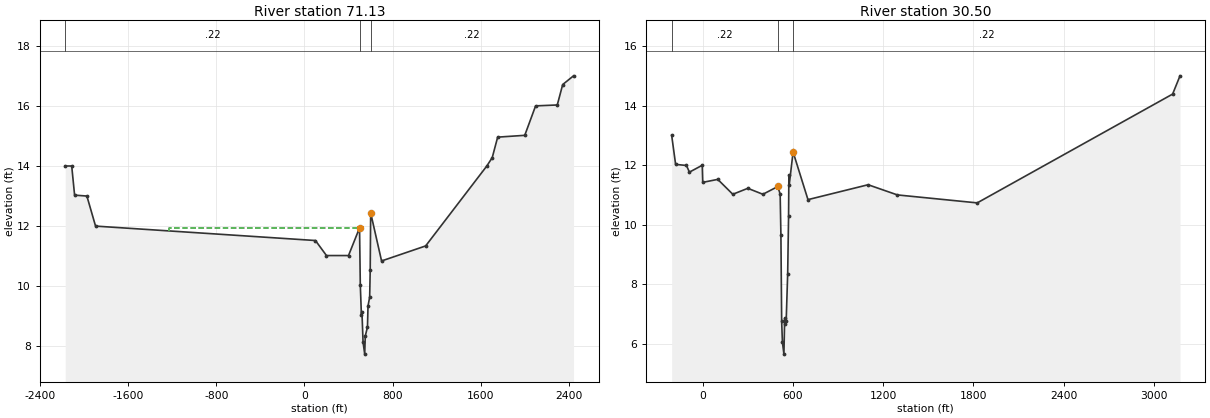
Type RM Length L Ch R = 1 ,71.13   ,4063.156,4063.156,4063.156
BEGIN DESCRIPTION:
LW1
END DESCRIPTION:
Node Name=LW1
XS GIS Cut Line= 2
460177.6475048793179246.18327002 460425.298004883179284.28337002
#Sta/Elev= 30
-2170.99      14-2111.97      14-2085.74   13.03-1974.28      13-1895.59      12
     100   11.52     200   11.02     400   11.02     500   11.94     507   10.04
     517    9.04     522    9.14     532    8.14     547    7.74     552    8.34
     572    8.64     577    9.34     592    9.64     597   10.54     601   12.44
     700   10.84    1100   11.34 1655.21      14 1704.39   14.28 1753.57   14.96
 1999.47   15.02 2097.82      16 2294.54   16.03 2343.73   16.71 2442.08      17
#Mann= 3 , 0 , 0
-2170.99     .22       0     500      .2       0     601     .22       0
#XS Ineff= 2 ,-1
-1226.79     500   11.94     601    1350   12.44
Permanent Ineff=
       F       F
Bank Sta=500,601
XS Rating Curve= 0 ,0
Exp/Cntr=0.3,0.1

Type RM Length L Ch R = 1 ,30.50   ,5,5,5
BEGIN DESCRIPTION:
WK18
END DESCRIPTION:
Node Name=WK18
XS GIS Cut Line= 2
 459515.919704883180360.70577002 459987.937304883180315.19737002
#Sta/Elev= 30
 -206.62      13 -180.39 12.0255-108.269 11.9891-88.6005  11.765 -3.3673 11.9961
       0  11.422     100  11.522     200  11.022     300  11.222     400  11.022
     500  11.283     515  11.023     520   9.653     525   6.753     530   6.053
     540   5.653     545   6.853     550   6.653     555   6.753     565   8.353
     571  10.293     573  11.663     575  11.323     601  12.442     700  10.842
    1100  11.3421294.801      111825.869 10.7326 3125.62 14.38723174.641      15
#Mann= 3 , 0 , 0
 -206.62     .22       0     500      .2       0     601     .22       0
#XS Ineff= 2 ,-1
     100     500   11.28     601    2450   12.44
Permanent Ineff=
       F       F
Bank Sta=500,601
XS Rating Curve= 0 ,0
Exp/Cntr=0.3,0.1