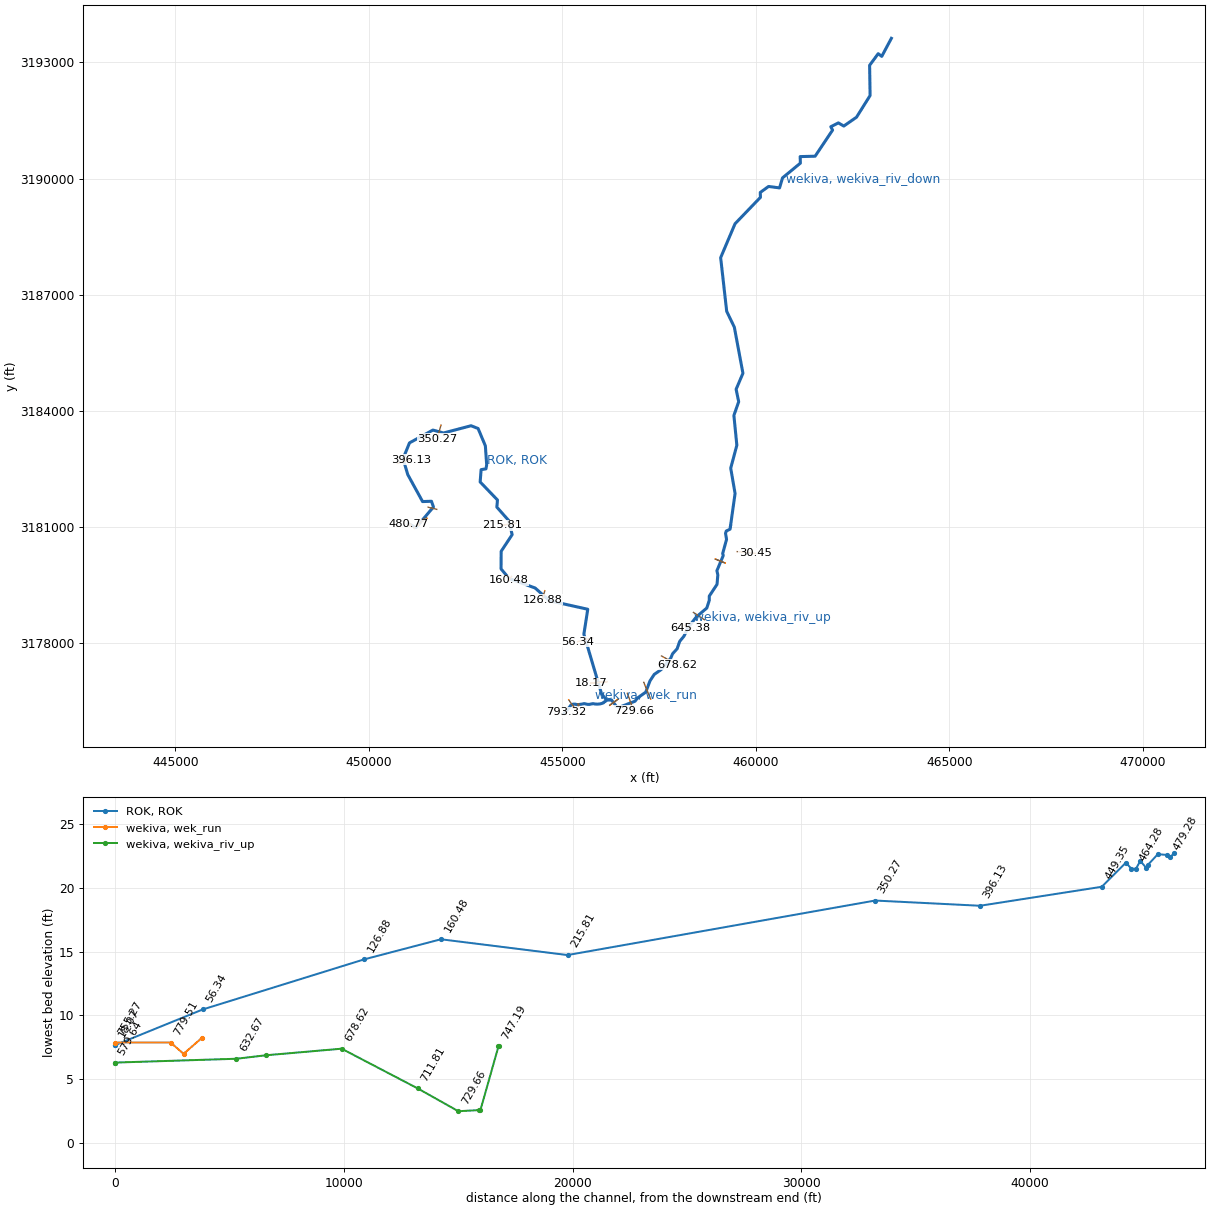
HEC-RAS study wekiva_ras.prj: wekiva_ras

--- wekiva_ras.g01 (geometry) --- (continued)

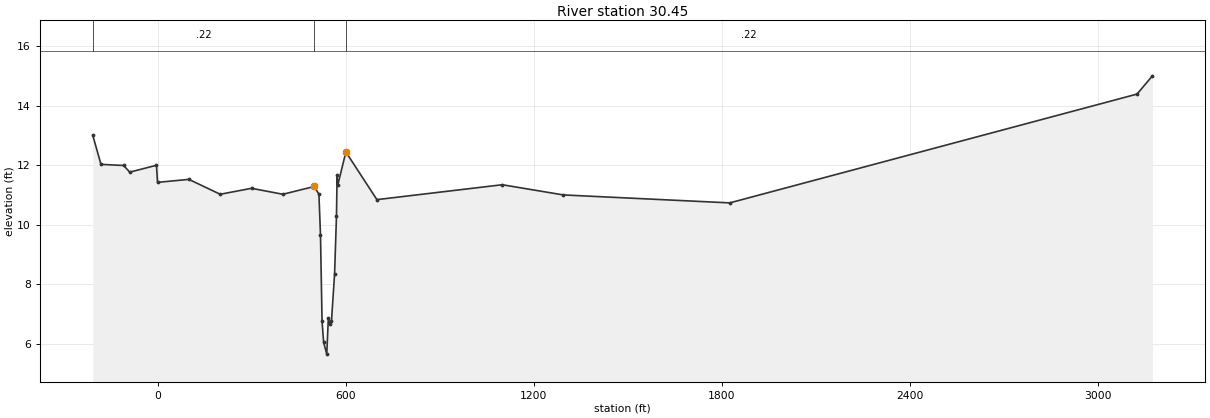
Type RM Length L Ch R = 1 ,30.45   ,3044.836,3044.836,3044.836
BEGIN DESCRIPTION:
WK18
END DESCRIPTION:
XS GIS Cut Line= 2
 459515.919704883180360.70577002 459987.937304883180315.19737002
#Sta/Elev= 30
 -206.62      13 -180.39 12.0255-108.269 11.9891-88.6005  11.765 -3.3673 11.9961
       0  11.422     100  11.522     200  11.022     300  11.222     400  11.022
     500  11.283     515  11.023     520   9.653     525   6.753     530   6.053
     540   5.653     545   6.853     550   6.653     555   6.753     565   8.353
     571  10.293     573  11.663     575  11.323     601  12.442     700  10.842
    1100  11.3421294.801      111825.869 10.7326 3125.62 14.38723174.641      15
#Mann= 3 , 0 , 0
 -206.62     .22       0     500      .2       0     601     .22       0
#XS Ineff= 2 ,-1
     100     500   11.28     601    2450   12.44
Permanent Ineff=
       F       F
Bank Sta=500,601
XS Rating Curve= 0 ,0
Exp/Cntr=0.3,0.1

River Reach=ROK             ,ROK
Reach XY= 30
 451023.213404883181083.14707002 451213.005804883180978.54017002
451667.4719048793181512.95497002451616.6891048793181661.33587002
 451386.579704883181653.40107002 451004.122004883182350.07717002
450881.9259048793182761.10017002451048.6541048793183170.39177002
 451654.178504883183501.00377002451927.1358048793183425.22637002
452639.4171048793183613.01687002 452821.763304883183541.14077002
453009.2232048793183092.49347002453042.9461048793182603.84157002
 453025.092804883182498.70537002452899.4583048793182478.53767002
 452874.331504883182160.48417002453321.9868048793181694.31427002
453306.1172048793181509.16877002 453613.921704883181161.35967002
 453701.204604883180798.34217002453417.2045048793180367.87887002
453414.5596048793179912.94997002 453624.832004883179664.78887002
 454294.638804883179419.86777002 454666.170704883179090.68087002
455655.0262048793178870.54787002 455554.633404883178225.81147002
 456011.347704883176686.76737002456138.8371248563176526.33636962

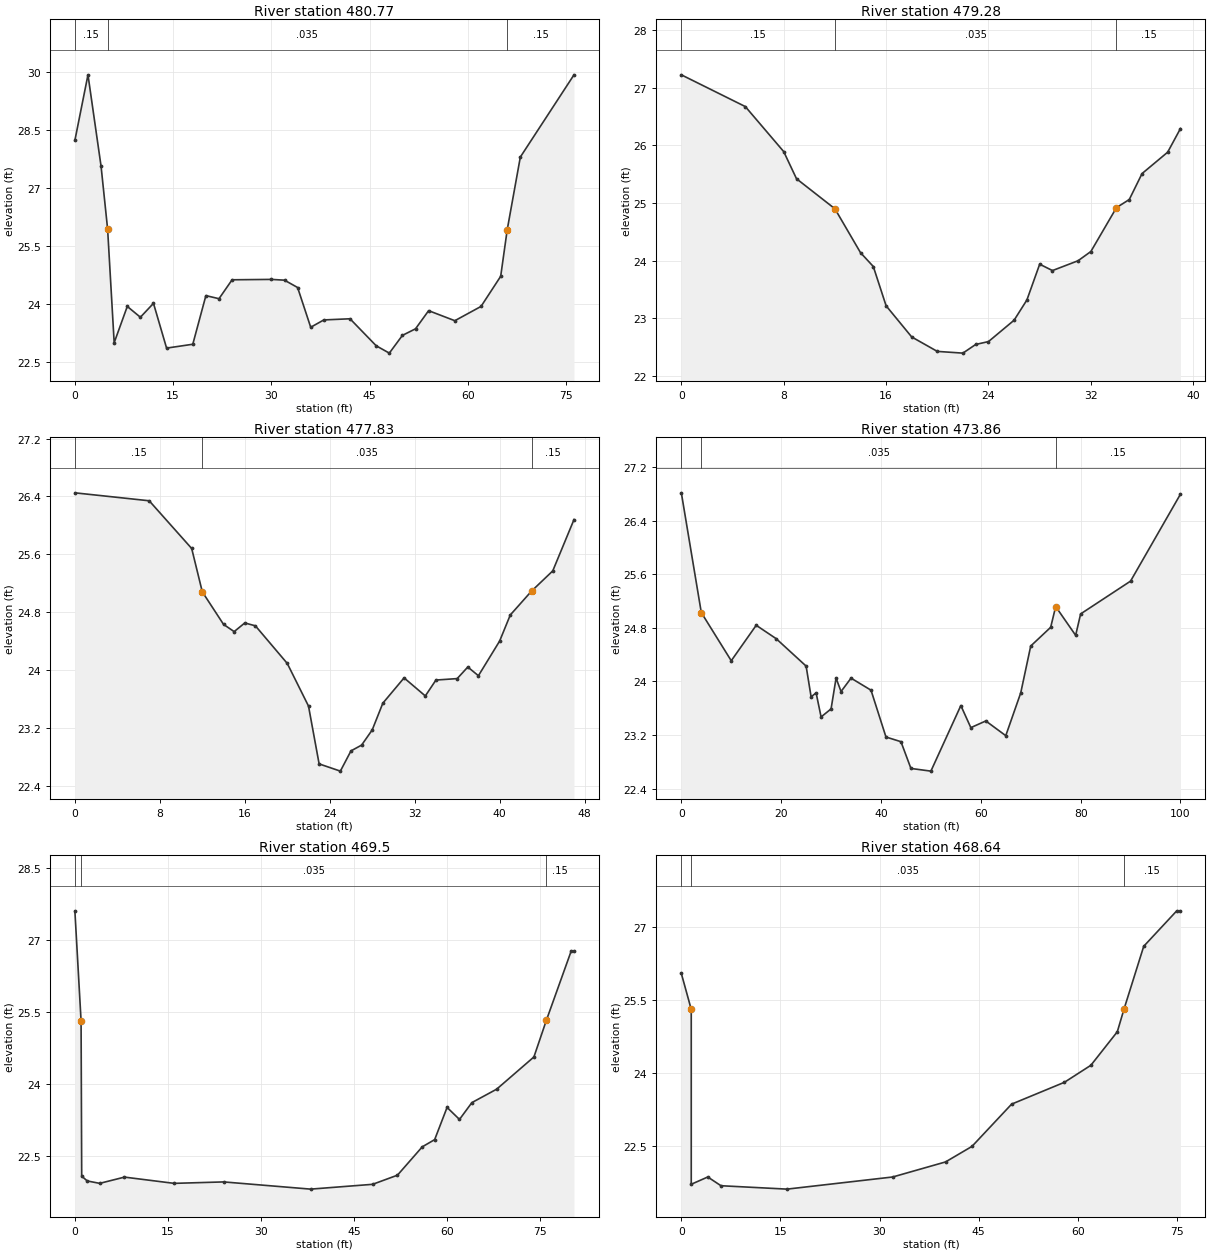
Type RM Length L Ch R = 1 ,480.77  ,149.0814,149.0814,149.0814
BEGIN DESCRIPTION:
RokSpr02
END DESCRIPTION:
Node Name=RokSpr02
XS GIS Cut Line= 2
451026.6781048793181095.07657002451022.5373048793181071.37427002
#Sta/Elev= 30
       0   28.23       2   29.93       4   27.56       5   25.93       6   22.99
       8   23.93      10   23.65      12   24.01      14   22.85      18   22.95
      20   24.21      22   24.13      24   24.62      30   24.63      32   24.61
      34   24.42      36   23.39      38   23.58      42   23.61      46   22.91
      48   22.72      50   23.18      52   23.35      54   23.82      58   23.56
      62   23.93      65   24.71      66   25.92      68    27.8   76.19   29.93
#Mann= 3 , 0 , 0
       0     .15       0       5    .035       0      66     .15       0
Bank Sta=5,66
XS Rating Curve= 0 ,0
Exp/Cntr=0.3,0.1

Type RM Length L Ch R = 1 ,479.28  ,145.1115,145.1115,145.1115
BEGIN DESCRIPTION:
RokSpr03
END DESCRIPTION:
Node Name=RokSpr03
XS GIS Cut Line= 2
451082.3677048793181066.28987002451051.4643048793181054.43647002
#Sta/Elev= 24
       0   27.22       5   26.67       8   25.89       9   25.42      12    24.9
      14   24.14      15    23.9      16   23.22      18   22.68      20   22.43
      22    22.4      23   22.55      24    22.6      26   22.97      27   23.32
      28   23.94      29   23.83      31      24      32   24.16      34   24.92
      35   25.06      36   25.51      38   25.88      39   26.29
#Mann= 3 , 0 , 0
       0     .15       0      12    .035       0      34     .15       0
Bank Sta=12,34
XS Rating Curve= 0 ,0
Exp/Cntr=0.3,0.1

Type RM Length L Ch R = 1 ,477.83  ,396.8176,396.8176,396.8176
BEGIN DESCRIPTION:
RokSpr04
END DESCRIPTION:
Node Name=RokSpr04
XS GIS Cut Line= 2
 451097.184404883181024.59137002 451068.609404883181013.79637002
#Sta/Elev= 27
       0   26.45       7   26.34      11   25.68      12   25.08      14   24.63
      15   24.53      16   24.65      17   24.61      20   24.09      22    23.5
      23    22.7      25    22.6      26   22.88      27   22.96      28   23.17
      29   23.54      31   23.89      33   23.64      34   23.86      36   23.88
      37   24.04      38   23.92      40    24.4      41   24.76      43   25.09
      45   25.37      47   26.08
#Mann= 3 , 0 , 0
       0     .15       0      12    .035       0      43     .15       0
Bank Sta=12,43
XS Rating Curve= 0 ,0
Exp/Cntr=0.3,0.1

Type RM Length L Ch R = 1 ,473.86  ,436.3189,436.3189,436.3189
BEGIN DESCRIPTION:
RokSpr05
END DESCRIPTION:
Node Name=RokSpr05
XS GIS Cut Line= 2
451175.4950048793180987.69237002451172.3109048793180957.39027002
#Sta/Elev= 30
       0   26.82       4   25.03      10   24.31      15   24.84      19   24.64
      25   24.23      26   23.77      27   23.83      28   23.47      30   23.59
      31   24.05      32   23.85      34   24.05      38   23.87      41   23.17
      44    23.1      46    22.7      50   22.66      56   23.64      58   23.31
      61   23.41      65   23.19      68   23.83      70   24.53      74   24.81
      75   25.12      79   24.69      80   25.01      90    25.5     100    26.8
#Mann= 3 , 0 , 0
       0     .15       0       4    .035       0      75     .15       0
Bank Sta=4,75
XS Rating Curve= 0 ,0
Exp/Cntr=0.3,0.1

Type RM Length L Ch R = 1 ,469.5   ,86.1877,86.1877,86.1877
BEGIN DESCRIPTION:
RokSpr08
END DESCRIPTION:
Node Name=RokSpr08
XS GIS Cut Line= 2
 451256.572004883181058.88917002451286.3376048793181034.67977002
#Sta/Elev= 21
       0   27.61       1   25.32     1.1   22.09       2   21.99       4   21.94
       8   22.07      16   21.94      24   21.97      38   21.82      48   21.92
      52   22.11      56    22.7      58   22.85      60   23.52      62   23.27
      64   23.62      68    23.9      74   24.57      76   25.33      80   26.77
   80.46   26.77
#Mann= 3 , 0 , 0
       0     .15       0       1    .035       0      76     .15       0
Bank Sta=1,76
XS Rating Curve= 0 ,0
Exp/Cntr=0.3,0.1

Type RM Length L Ch R = 1 ,468.64  ,242.6181,242.6181,242.6181
BEGIN DESCRIPTION:
RokSpr09
END DESCRIPTION:
Node Name=RokSpr09
XS GIS Cut Line= 2
 451276.415704883181079.12987002 451298.510204883181052.33677002
#Sta/Elev= 17
       0   26.05     1.5   25.31     1.5   21.71       4   21.86       6   21.68
      16   21.61      32   21.86      40   22.17      44   22.49      50   23.36
      58   23.81      62   24.16      66   24.85      67   25.31      70   26.61
      75   27.34   75.56   27.34
#Mann= 3 , 0 , 0
       0     .15       0     1.5    .035       0      67     .15       0
Bank Sta=1.5,67
XS Rating Curve= 0 ,0
Exp/Cntr=0.3,0.1

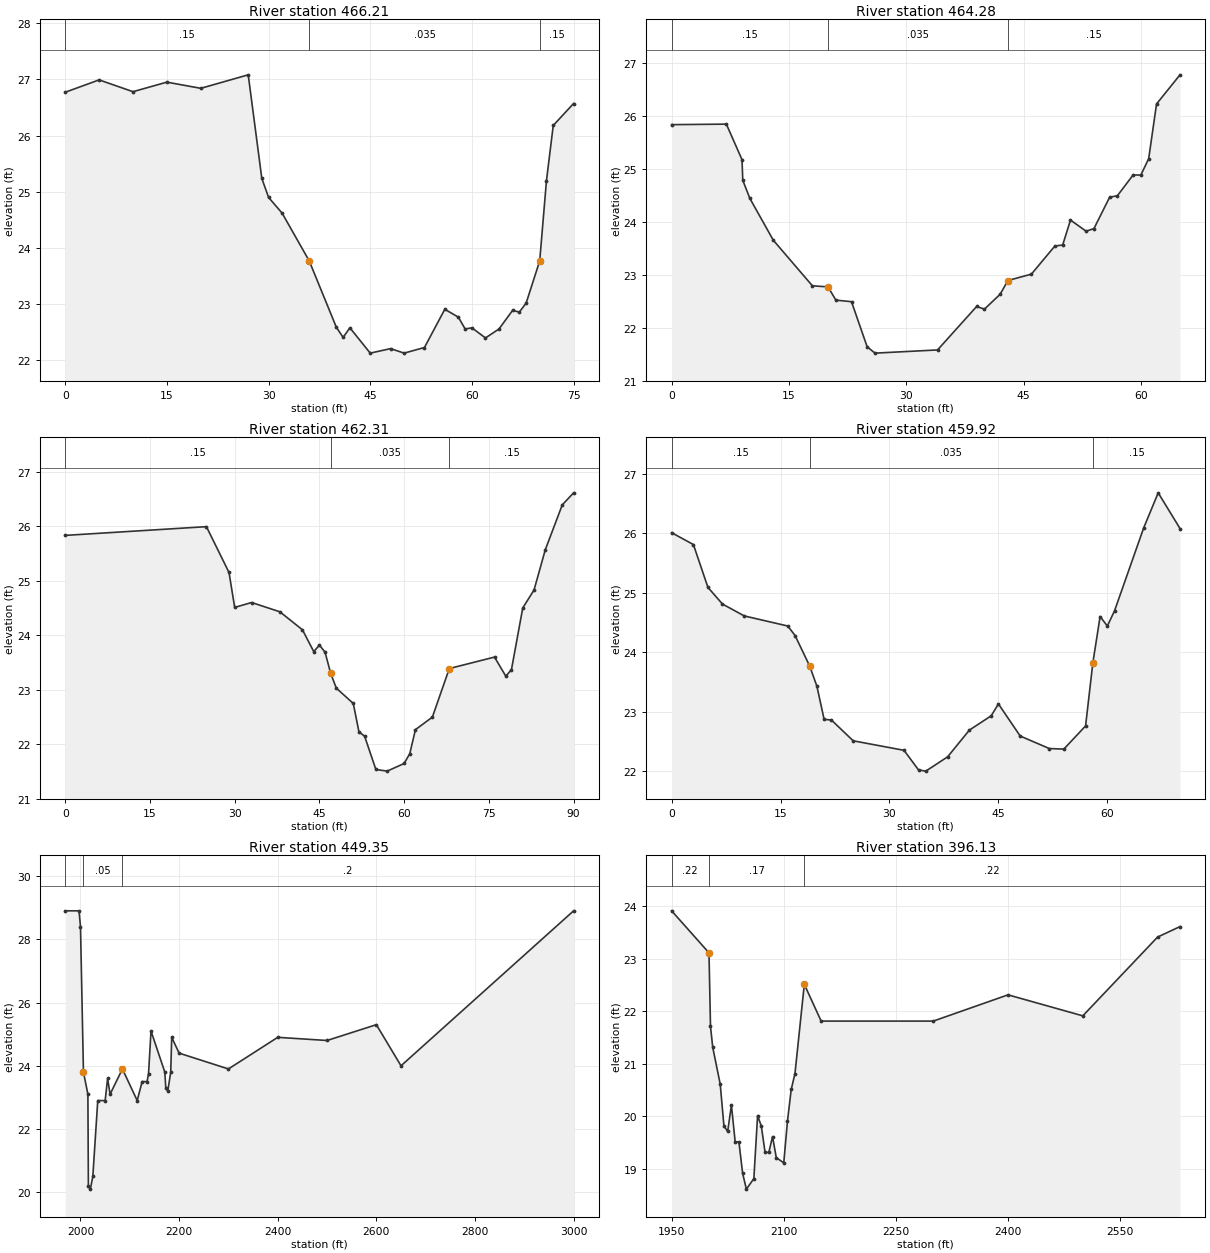
Type RM Length L Ch R = 1 ,466.21  ,193.2415,193.2415,193.2415
BEGIN DESCRIPTION:
RokSpr11
END DESCRIPTION:
Node Name=RokSpr11
XS GIS Cut Line= 2
451331.5027048793181121.98737002 451349.007504883181107.29797002
#Sta/Elev= 30
       0   26.77       5   26.99      10   26.78      15   26.95      20   26.84
      27   27.08      29   25.24      30    24.9      32   24.62      36   23.77
      40   22.59      41   22.41      42   22.58      45   22.13      48   22.21
      50   22.13      53   22.23      56   22.91      58   22.77      59   22.56
      60   22.58      62    22.4      64   22.56      66   22.89      67   22.86
      68   23.02      70   23.77      71    25.2      72   26.18      75   26.57
#Mann= 3 , 0 , 0
       0     .15       0      36    .035       0      70     .15       0
Bank Sta=36,70
XS Rating Curve= 0 ,0
Exp/Cntr=0.3,0.1

Type RM Length L Ch R = 1 ,464.28  ,196.4567,196.4567,196.4567
BEGIN DESCRIPTION:
RokSpr12
END DESCRIPTION:
Node Name=RokSpr12
XS GIS Cut Line= 2
 451376.887304883181161.36027002 451390.891104883181147.35337002
#Sta/Elev= 30
       0   25.83       7   25.84       9   25.17     9.1   24.78      10   24.44
      13   23.65      18   22.79      20   22.77      21   22.52      23   22.49
      25   21.64      26   21.52      34   21.58      39    22.4      40   22.35
      42   22.63      43   22.89      46   23.01      49   23.54      50   23.56
      51   24.03      53   23.82      54   23.87      56   24.46      57   24.49
      59   24.88      60   24.88      61   25.19      62   26.22      65   26.77
#Mann= 3 , 0 , 0
       0     .15       0      20    .035       0      43     .15       0
Bank Sta=20,43
XS Rating Curve= 0 ,0
Exp/Cntr=0.3,0.1

Type RM Length L Ch R = 1 ,462.31  ,239.5341,239.5341,239.5341
BEGIN DESCRIPTION:
RokSpr13
END DESCRIPTION:
Node Name=RokSpr13
XS GIS Cut Line= 2
451422.9117048793181205.33417002 451436.623104883181181.58607002
#Sta/Elev= 30
       0   25.83      25   25.99      29   25.15      30   24.51      33    24.6
      38   24.43      42    24.1      44    23.7      45   23.82      46   23.69
      47    23.3      48   23.03      51   22.75      52   22.23      53   22.15
      55   21.54      57   21.51      60   21.65      61   21.83      62   22.27
      65    22.5      68   23.39      76    23.6      78   23.25      79   23.37
      81    24.5      83   24.83      85   25.57      88   26.39      90   26.61
#Mann= 3 , 0 , 0
       0     .15       0      47    .035       0      68     .15       0
Bank Sta=47,68
XS Rating Curve= 0 ,0
Exp/Cntr=0.3,0.1

Type RM Length L Ch R = 1 ,459.92  ,1057.185,1057.185,1057.185
BEGIN DESCRIPTION:
RokSpr14
END DESCRIPTION:
Node Name=RokSpr14
XS GIS Cut Line= 2
451484.9297048793181229.40207002 451504.259604883181220.38617002
#Sta/Elev= 30
       0   26.01       3   25.81       5   25.09       7   24.81      10   24.61
      16   24.44      17   24.28      19   23.77      20   23.43      21   22.87
      22   22.86      25   22.51      32   22.35      34   22.02      35      22
      38   22.24      41   22.69      44   22.93      45   23.13      48   22.59
      52   22.38      54   22.37      57   22.76      58   23.82      59    24.6
      60   24.44      61    24.7      65   26.09      67   26.68      70   26.08
#Mann= 3 , 0 , 0
       0     .15       0      19    .035       0      58     .15       0
Bank Sta=19,58
XS Rating Curve= 0 ,0
Exp/Cntr=0.3,0.1

Type RM Length L Ch R = 1 ,449.35  ,5321.588,5321.588,5321.588
BEGIN DESCRIPTION:
ROK7
END DESCRIPTION:
Node Name=ROK7
XS GIS Cut Line= 2
 451531.470204883181508.48117002 451753.720604883181451.33097002
#Sta/Elev= 30
    1969    28.9    1997    28.9    2000    28.4    2006    23.8    2015    23.1
    2016    20.2    2020    20.1    2025    20.5    2035    22.9    2050    22.9
    2055    23.6    2060    23.1    2085    23.9    2115    22.9    2125    23.5
    2135    23.5    2138   23.75    2143    25.1    2171    23.8    2173    23.3
    2177    23.2    2183    23.8    2185    24.9    2200    24.4    2300    23.9
    2400    24.9    2500    24.8    2600    25.3    2650      24    3000    28.9
#Mann= 3 , 0 , 0
    1969      .2       0    2006     .05       0    2085      .2       0
Bank Sta=2006,2085
XS Rating Curve= 0 ,0
Exp/Cntr=0.3,0.1

Type RM Length L Ch R = 1 ,396.13  ,4586.122,4586.122,4586.122
BEGIN DESCRIPTION:
ROK6
END DESCRIPTION:
Node Name=ROK6
XS GIS Cut Line= 2
450737.7186048793182638.78337002451099.6693048793182740.38357002
#Sta/Elev= 30
    1950   23.91    2000   23.11    2002   21.71    2005   21.31    2015   20.61
    2020   19.81    2025   19.71    2030   20.21    2035   19.51    2040   19.51
    2045   18.91    2050   18.61    2060   18.81    2065   20.01    2070   19.81
    2075   19.31    2080   19.31    2085   19.61    2090   19.21    2100   19.11
    2105   19.91    2110   20.51    2115   20.81  2127.5   22.51    2150   21.81
    2300   21.81    2400   22.31    2500   21.91    2600   23.41    2630   23.61
#Mann= 3 , 0 , 0
    1950     .22       0    2000     .17       0  2127.5     .22       0
Bank Sta=2000,2127.5
XS Rating Curve= 0 ,0
Exp/Cntr=0.3,0.1

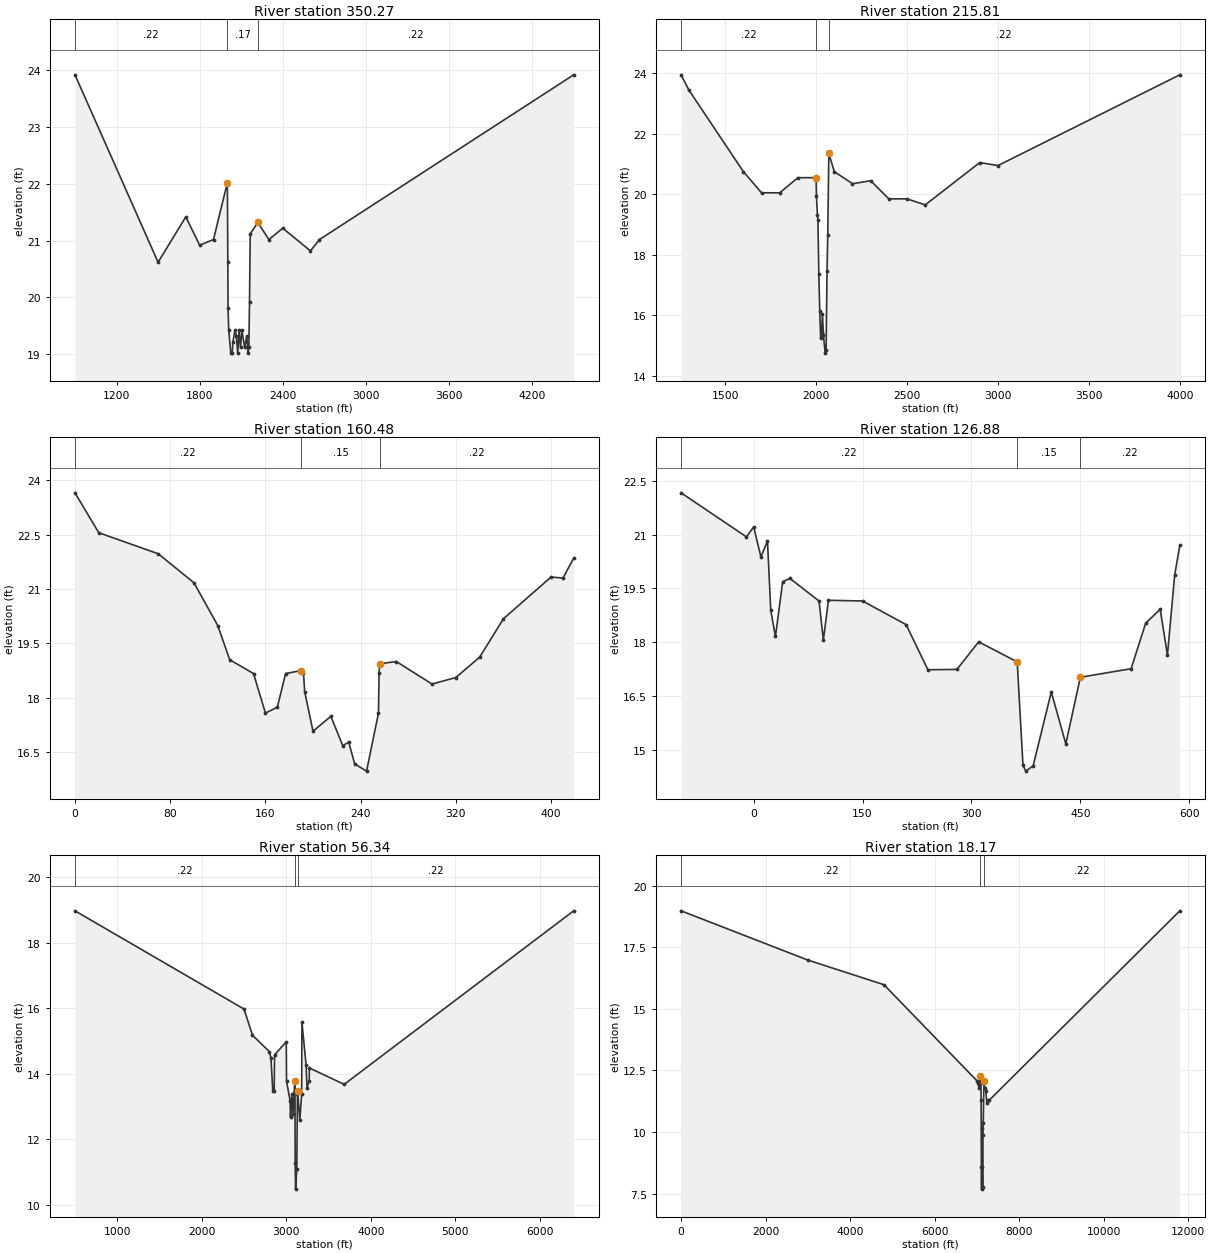
Type RM Length L Ch R = 1 ,350.27  ,13446.29,13446.29,13446.29
BEGIN DESCRIPTION:
ROK5
END DESCRIPTION:
Node Name=ROK5
XS GIS Cut Line= 2
 451861.670804883183629.38537002 451766.420704883183273.78467002
#Sta/Elev= 30
     900   23.92    1500   20.62    1700   21.42    1800   20.92    1900   21.02
    2000   22.02  2003.5   20.63    2005   19.82    2010   19.42    2025   19.02
    2035   19.02    2040   19.22    2055   19.42    2065   19.32    2075   19.02
    2085   19.42    2095   19.12    2105   19.42    2125   19.12    2140   19.32
    2150   19.02    2155   19.12    2160   19.92    2165   21.12    2220   21.32
    2300   21.02    2400   21.22    2600   20.82    2665   21.02    4500   23.92
#Mann= 3 , 0 , 0
     900     .22       0    2000     .17       0    2220     .22       0
Bank Sta=2000,2220
XS Rating Curve= 0 ,0
Exp/Cntr=0.3,0.1

Type RM Length L Ch R = 1 ,215.81  ,5532.677,5532.677,5532.677
BEGIN DESCRIPTION:
ROK4
END DESCRIPTION:
Node Name=ROK4
XS GIS Cut Line= 2
 453798.424704883181095.73027002453442.8240048793181038.58017002
#Sta/Elev= 30
  1257.5   23.94    1300   23.44    1600   20.74    1700   20.04    1800   20.04
    1900   20.54    2000   20.54    2002   19.94    2007   19.32    2010   19.14
    2015   17.34    2020   16.14    2025   15.24    2030   15.44    2035   16.04
    2040   15.34    2050   14.74    2055   14.84    2060   17.44    2064   18.64
    2070   21.34    2100   20.74    2200   20.34    2300   20.44    2400   19.84
    2500   19.84    2600   19.64    2900   21.04    3000   20.94    4000   23.94
#Mann= 3 , 0 , 0
  1257.5     .22       0    2000     .15       0    2070     .22       0
Bank Sta=2000,2070
XS Rating Curve= 0 ,0
Exp/Cntr=0.3,0.1

Type RM Length L Ch R = 1 ,160.48  ,3360.203,3360.203,3360.203
BEGIN DESCRIPTION:
ROK3
END DESCRIPTION:
Node Name=ROK3
XS GIS Cut Line= 2
 453683.837304883179720.61477002 453618.766804883179618.24147002
#Sta/Elev= 30
       0   23.65      20   22.55      70   21.97     100   21.17     120   19.99
     130   19.05     150   18.67     160   17.58     170   17.74     177   18.67
     190   18.75     192   18.68     193   18.17     200   17.08     215   17.49
     225   16.68     230   16.78     235   16.18     245   15.98     255   17.58
   255.5   18.68     256   18.94     270      19     300   18.38     320   18.56
     340   19.12     360   20.18     400   21.33     410    21.3     419   21.85
#Mann= 3 , 0 , 0
       0     .22       0     190     .15       0     256     .22       0
Bank Sta=190,256
XS Rating Curve= 0 ,0
Exp/Cntr=0.3,0.1

Type RM Length L Ch R = 1 ,126.88  ,7053.478,7053.478,7053.478
BEGIN DESCRIPTION:
ROK2
END DESCRIPTION:
Node Name=ROK2
XS GIS Cut Line= 2
454544.9803048793179351.14227002 454484.226104883179114.52637002
#Sta/Elev= 30
    -100   22.17     -10   20.94       0   21.22      10   20.38      19   20.83
    23.5   18.89      30   18.16      40   19.69      50   19.78      90   19.15
      96   18.06     103   19.17     150   19.15     210   18.49     240   17.23
     280   17.24     310   18.01     363   17.45     371   14.56     375    14.4
     385   14.55     410   16.61     430   15.16     450   17.02     520   17.26
     540   18.53     560   18.92     570   17.64     580   19.88     587    20.7
#Mann= 3 , 0 , 0
    -100     .22       0     363     .15       0     450     .22       0
Bank Sta=363,450
XS Rating Curve= 0 ,0
Exp/Cntr=0.3,0.1

Type RM Length L Ch R = 1 ,56.34   ,3817.881,3817.881,3817.881
BEGIN DESCRIPTION:
ROK1
END DESCRIPTION:
Node Name=ROK1
XS GIS Cut Line= 2
455779.6287048793178130.27437002455392.2779048793178035.02417002
#Sta/Elev= 30
     500   18.97    2500   15.97    2600   15.17    2800   14.67    2819   14.47
    2840   13.47    2857   13.47    2861   14.57    3000   14.97    3003   13.77
    3045   13.17    3050   12.67    3065   13.37    3080   12.77    3100   13.77
    3103   13.47    3105   11.27    3110   10.47    3124   11.07    3132   13.37
    3135   13.47    3160   12.57    3182   13.37    3185   15.57    3234   14.27
    3245   13.57    3271   13.77    3273   14.17    3685   13.67    6400   18.97
#Mann= 3 , 0 , 0
     500     .22       0    3100     .16       0    3135     .22       0
Bank Sta=3100,3135
XS Rating Curve= 0 ,0
Exp/Cntr=0.3,0.1

Type RM Length L Ch R = 1 ,18.17   ,10,10,10
BEGIN DESCRIPTION:
WK16
END DESCRIPTION:
Node Name=WK16
XS GIS Cut Line= 2
 456154.279404883176999.97207002455735.1786048793176961.87207002
#Sta/Elev= 23
       0   18.98    3000   16.98    4800   15.98    7000   12.08    7025   11.98
    7050   11.78    7075   12.28    7095   11.98    7100   11.28    7105    8.58
    7110    7.68    7125   10.18    7130    8.58    7135    7.78    7140    9.88
    7150   10.38    7165   12.08    7185   11.78    7210   11.68    7235   11.18
    7260   11.28    7285   11.28   11800   18.98
#Mann= 3 , 0 , 0
       0     .22       0    7075     .17       0    7165     .22       0
Bank Sta=7075,7165
XS Rating Curve= 0 ,0
Exp/Cntr=0.3,0.1

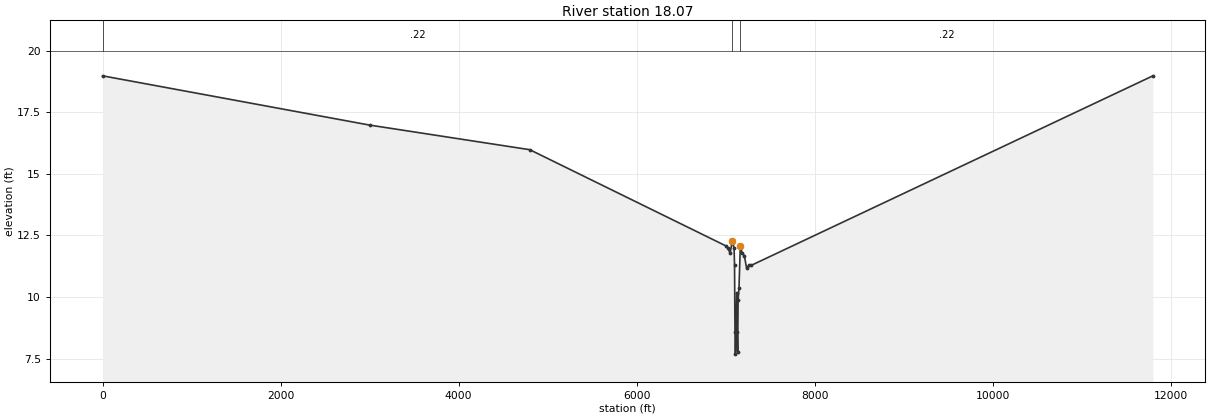
Type RM Length L Ch R = 1 ,18.07   ,1806.503,1806.503,1806.503
BEGIN DESCRIPTION:
WK16
END DESCRIPTION:
XS GIS Cut Line= 2
 456154.279404883176999.97207002455735.1786048793176961.87207002
#Sta/Elev= 23
       0   18.98    3000   16.98    4800   15.98    7000   12.08    7025   11.98
    7050   11.78    7075   12.28    7095   11.98    7100   11.28    7105    8.58
    7110    7.68    7125   10.18    7130    8.58    7135    7.78    7140    9.88
    7150   10.38    7165   12.08    7185   11.78    7210   11.68    7235   11.18
    7260   11.28    7285   11.28   11800   18.98
#Mann= 3 , 0 , 0
       0     .22       0    7075     .17       0    7165     .22       0
Bank Sta=7075,7165
XS Rating Curve= 0 ,0
Exp/Cntr=0.3,0.1

River Reach=wekiva          ,wek_run
Reach XY= 30
455048.2208048793176180.16957002 455135.652104883176281.35967002
 455161.290704883176314.97967002 455186.929404883176348.59957002
 455221.114204883176393.42617002 455279.169004883176418.60717002
 455347.296904883176417.28807002 455354.239904883176411.66767002
 455361.182804883176406.04717002 455400.360904883176407.28697002
 455413.420304883176407.70017002455488.1398048793176417.28807002
455564.8629048793176432.29287002455606.0147048793176422.97217002
455647.1665048793176413.65137002 455691.231104883176411.45757002
455719.5225048793176417.37937002 455733.668104883176420.34037002
 455779.433904883176429.91987002455792.4830048793176430.21637002
 455805.532004883176430.51277002 455839.885204883176422.07207002
455912.5910048793176418.70157002455983.9726048793176426.74377002
 456062.051204883176452.13507002 456073.688804883176473.08307002
456100.9846048793176483.66277002 456127.857104883176509.68897002
 456133.653204883176518.05757002456138.8371248563176526.33636962

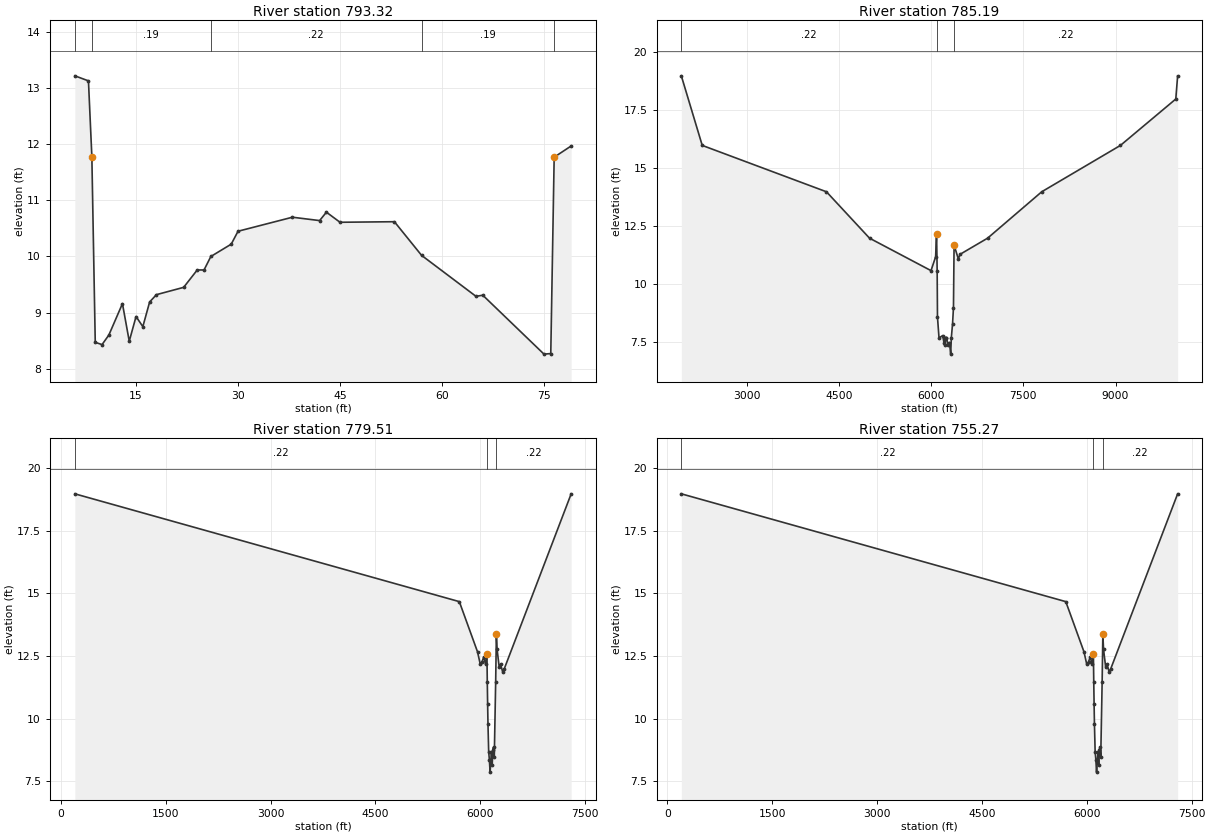
Type RM Length L Ch R = 1 ,793.32  ,813.0906,813.0906,813.0906
BEGIN DESCRIPTION:
WekSpr6
WekSpr6
END DESCRIPTION:
Node Name=WekSpr6
XS GIS Cut Line= 2
     455071.1753     3176243.645     455098.0644     3176211.408
#Sta/Elev= 30
       6   13.22       8   13.13     8.5   11.78       9    8.47      10    8.43
      11     8.6      13    9.16      14    8.49      15    8.93      16    8.75
      17    9.19      18    9.32      22    9.45      24    9.76      25    9.76
      26      10      29   10.22      30   10.45      38    10.7      42   10.64
      43   10.79      45   10.61      53   10.62      57   10.02      65    9.29
      66    9.31      75    8.26      76    8.27    76.5   11.77      79   11.97
#Mann= 5 ,-1 , 0
       6     .22       0     8.5     .19       0      26     .22       0
      57     .19       0    76.5     .22       0
Bank Sta=8.5,76.5
XS Rating Curve= 0 ,0
Exp/Cntr=0.3,0.1

Type RM Length L Ch R = 1 ,785.19  ,567.8806,567.8806,567.8806
BEGIN DESCRIPTION:
WEK13
END DESCRIPTION:
Node Name=WEK13
XS GIS Cut Line= 2
 455163.677404883176530.07117002455328.7778048793176295.12067002
#Sta/Elev= 30
    1940   18.99    2280   15.99    4300   13.99    5000   11.99    6000   10.59
    6075   11.19    6090   12.19    6100   10.59    6105    8.59    6130    7.69
    6190    7.79    6210    7.49    6220    7.69    6230    7.39    6240    7.69
    6250    7.69    6280    7.39    6300    7.49    6320    6.99    6330    7.69
    6350    8.29    6365    8.99    6375   11.69    6445   11.09    6470   11.29
    6920   11.99    7800   13.99    9080   15.99    9980   17.99   10010   18.99
#Mann= 3 , 0 , 0
    1940     .22       0    6090     .19       0    6375     .22       0
Bank Sta=6090,6375
XS Rating Curve= 0 ,0
Exp/Cntr=0.3,0.1

Type RM Length L Ch R = 1 ,779.51  ,2424,2424,2424
BEGIN DESCRIPTION:
WK17
END DESCRIPTION:
Node Name=WK17
XS GIS Cut Line= 2
      455414.687     3176429.959      455415.957     3176385.507
#Sta/Elev= 27
     200   18.97    5700   14.67    5960   12.67    6000   12.17    6025   12.27
    6050   12.47    6075   12.17    6095   12.57    6100   11.47    6105   10.57
    6110    9.77    6120    8.67    6130    8.37    6140    7.87    6160    8.67
    6170    8.17    6180    8.77    6190    8.87    6200    8.47    6220   11.47
    6230   13.37    6240   12.77    6270   12.07    6290   12.17    6320   11.87
    6340   11.97    7300   18.97
#Mann= 3 , 0 , 0
     200     .22       0    6095     .19       0    6230     .22       0
Bank Sta=6095,6230
XS Rating Curve= 0 ,0
Exp/Cntr=0.3,0.1

Type RM Length L Ch R = 1 ,755.27  ,807.9,807.9,807.9
BEGIN DESCRIPTION:
WK17-copy
END DESCRIPTION:
XS GIS Cut Line= 2
      455414.687     3176429.959      455415.957     3176385.507
#Sta/Elev= 27
     200   18.97    5700   14.67    5960   12.67    6000   12.17    6025   12.27
    6050   12.47    6075   12.17    6095   12.57    6100   11.47    6105   10.57
    6110    9.77    6120    8.67    6130    8.37    6140    7.87    6160    8.67
    6170    8.17    6180    8.77    6190    8.87    6200    8.47    6220   11.47
    6230   13.37    6240   12.77    6270   12.07    6290   12.17    6320   11.87
    6340   11.97    7300   18.97
#Mann= 3 , 0 , 0
     200     .22       0    6095     .19       0    6230     .22       0
Bank Sta=6095,6230
XS Rating Curve= 0 ,0
Exp/Cntr=0.3,0.1

River Reach=wekiva          ,wekiva_riv_up
Reach XY= 30
456138.8371248563176526.33636962 456273.222804883176523.01937002
 456397.217404883176354.37827002456471.5181048793176339.12477002
456876.9030048793176494.45407002456939.6671048793176577.53467002
 457153.375704883176727.96127002 457262.428904883177018.57457002
 457373.727804883177188.27367002457550.1979048793177310.15237002
457798.8880048793177604.91717002 457846.496804883177719.31067002
 457964.527104883177850.23497002 458031.311704883178041.66227002
 458140.415304883178173.57847002458251.4611048793178401.48007002
458459.1300048793178670.82637002 458730.236004883178901.92767002
 458795.466704883179100.95897002458794.6732048793179209.66587002
 458995.423904883179513.56897002 459016.054404883179757.96107002
458992.2500048793179866.66797002459155.8558048793180256.81797002
459141.9699048793180311.96497002 459241.551704883180675.77587002
 459214.913104883180833.89037002459235.2039048793180893.18957002
459332.6042048793180939.68187002 459343.436962483181018.99032073

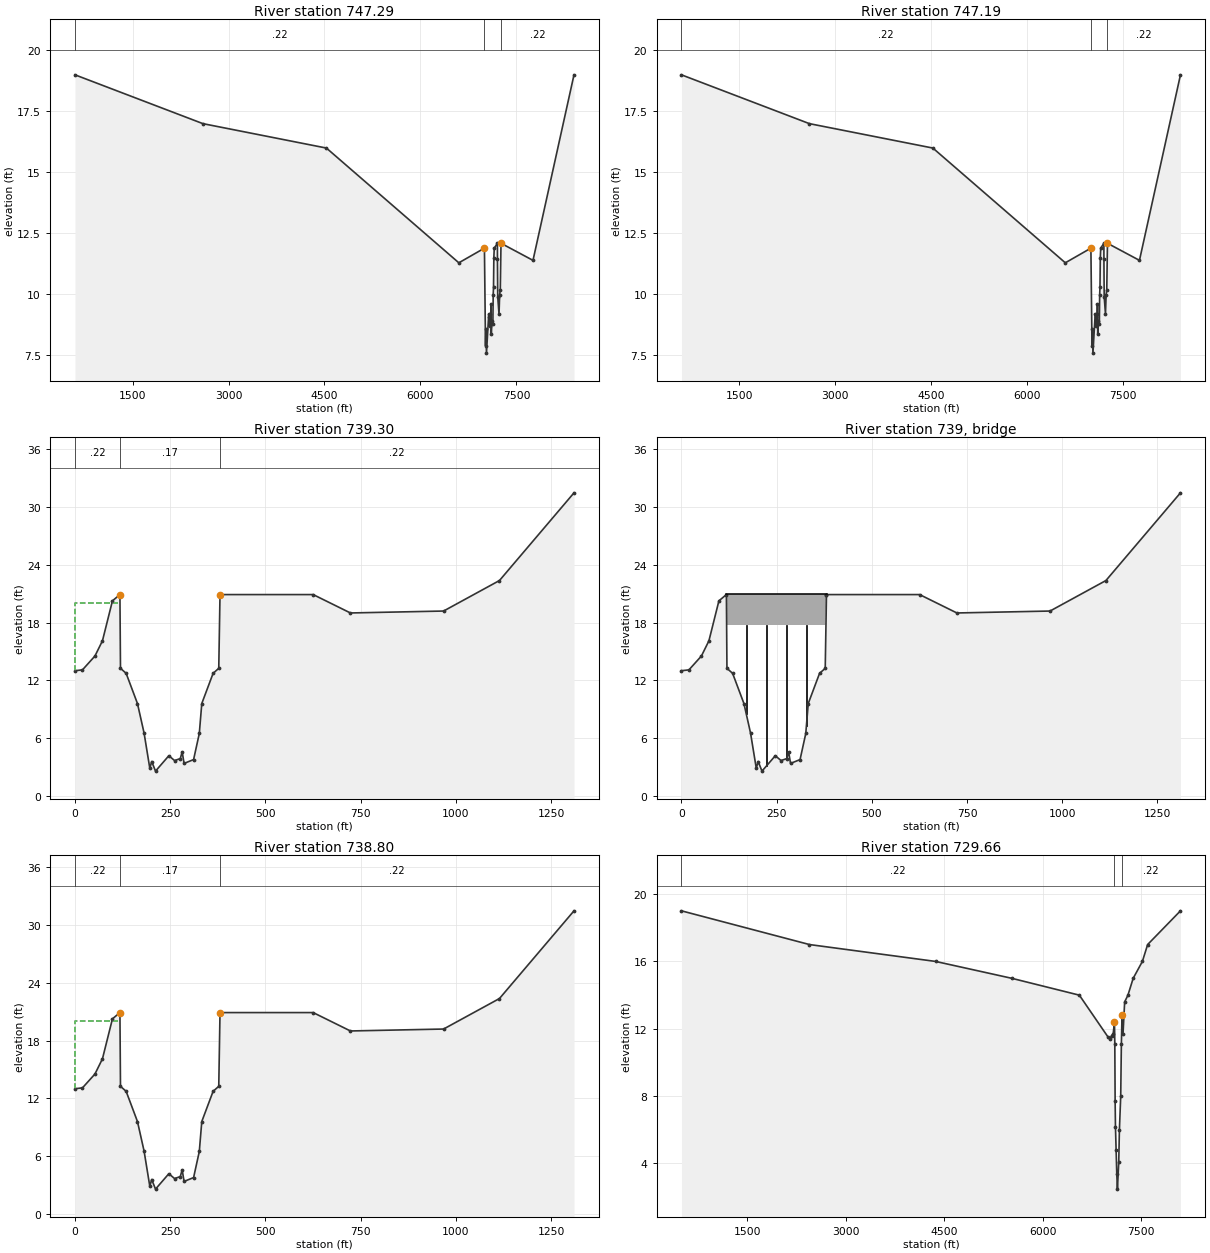
Type RM Length L Ch R = 1 ,747.29  ,10,10,10
BEGIN DESCRIPTION:
WEK12
END DESCRIPTION:
XS GIS Cut Line= 2
456440.0300048793176549.12117002 456224.129604883176390.37087002
#Sta/Elev= 30
     600   18.97    2600   16.97    4530   15.97    6600   11.27    7000   11.87
    7017    7.87    7022    8.57    7032    7.57    7067    9.17    7077    9.07
    7082    8.67    7092    9.17    7097    8.87    7102    9.57    7107    8.37
    7117    8.87    7132    8.77    7137    9.97    7142   10.27    7147   11.48
  7153.5   11.87    7203   12.07  7203.5   11.41    7208    9.87    7228    9.17
    7238    9.97    7248   10.17    7259   12.07    7759   11.37    8400   18.97
#Mann= 3 , 0 , 0
     600     .22       0    7000     .19       0    7259     .22       0
Bank Sta=7000,7259
XS Rating Curve= 0 ,0
Exp/Cntr=0.3,0.1

Type RM Length L Ch R = 1 ,747.19  ,789,789,789
BEGIN DESCRIPTION:
WEK12
END DESCRIPTION:
Node Name=WEK12
XS GIS Cut Line= 2
456440.0300048793176549.12117002 456224.129604883176390.37087002
#Sta/Elev= 30
     600   18.97    2600   16.97    4530   15.97    6600   11.27    7000   11.87
    7017    7.87    7022    8.57    7032    7.57    7067    9.17    7077    9.07
    7082    8.67    7092    9.17    7097    8.87    7102    9.57    7107    8.37
    7117    8.87    7132    8.77    7137    9.97    7142   10.27    7147   11.48
  7153.5   11.87    7203   12.07  7203.5   11.41    7208    9.87    7228    9.17
    7238    9.97    7248   10.17    7259   12.07    7759   11.37    8400   18.97
#Mann= 3 , 0 , 0
     600     .22       0    7000     .19       0    7259     .22       0
Bank Sta=7000,7259
XS Rating Curve= 0 ,0
Exp/Cntr=0.3,0.1

Type RM Length L Ch R = 1 ,739.30  ,50,50,50
BEGIN DESCRIPTION:
interpolation of WEK12 amd WK15
END DESCRIPTION:
#Sta/Elev= 30
       0      13   19.67   13.09   52.45   14.53   72.12   16.11   98.35   20.26
  118.01   20.91  119.46   13.25  134.33   12.73  164.06    9.59  181.46    6.52
  196.46    2.87  201.46    3.57  211.46    2.57  246.46    4.17  261.46    3.67
  276.46    3.87  281.46    4.57  286.46    3.37  311.46    3.77  326.46    6.48
  332.96    9.59   362.7   12.73  377.56   13.25  380.83    20.9  380.83   20.91
  625.47   20.91  723.32      19  967.96    19.2 1114.74   22.37 1310.44   31.48
#Mann= 3 , 0 , 0
       0     .22       0  118.01     .17       0  380.83     .22       0
#XS Ineff= 1 ,-1
       0  118.01      20
Permanent Ineff=
       F
Bank Sta=118.01,380.83
XS Rating Curve= 0 ,0
Exp/Cntr=0.3,0.1

Type RM Length L Ch R = 3 ,739     ,,,
Bridge Culvert--1,0,-1,-1, 0
Deck Dist Width WeirC Skew NumUp NumDn MinLoCord MaxHiCord MaxSubmerge Is_Ogee
10,30,2.6,0, 2, 2, , , 0.98, 0, 0,0,,
     118   380.9
      21      21
   17.75   17.75
     118   380.9
      21      21
   17.75   17.75
Pier Skew, UpSta & Num, DnSta & Num=  ,170.5, 2 ,170.5, 2 , 0 , 0 , 0 ,,
       1       1
       0      21
       1       1
       0      21
Pier Skew, UpSta & Num, DnSta & Num=  ,223, 2 ,223, 2 , 0 , 0 , 0 ,,
       1       1
       0      21
       1       1
       0      21
Pier Skew, UpSta & Num, DnSta & Num=  ,275.5, 2 ,275.5, 2 , 0 , 0 , 0 ,,
       1       1
       0      21
       1       1
       0      21
Pier Skew, UpSta & Num, DnSta & Num=  ,328, 2 ,328, 2 , 0 , 0 , 0 ,,
       1       1
       0      21
       1       1
       0      21
BR Coef=-1 , 0 , 0 ,, 0 ,,,0.8,-1,,0,
WSPro=,,,, 1 ,,,, 0 ,,,, 0 ,,,,-1 ,-1 ,-1 , 0 , 0 , 0 , 0 , 0
BC Design=,, 0 ,, 0 ,,,,,,
BC HTab HWMax=15
BC Use User HTab Curves=0
BC User HTab FreeFlow(D)= 0

Type RM Length L Ch R = 1 ,738.80  ,914,914,914
BEGIN DESCRIPTION:
interpolation of WEK12 amd WK15
END DESCRIPTION:
#Sta/Elev= 30
       0      13   19.67   13.09   52.45   14.53   72.12   16.11   98.35   20.26
  118.01   20.91  119.46   13.25  134.33   12.73  164.06    9.59  181.46    6.52
  196.46    2.87  201.46    3.57  211.46    2.57  246.46    4.17  261.46    3.67
  276.46    3.87  281.46    4.57  286.46    3.37  311.46    3.77  326.46    6.48
  332.96    9.59   362.7   12.73  377.56   13.25  380.83    20.9  380.83   20.91
  625.47   20.91  723.32      19  967.96    19.2 1114.74   22.37 1310.44   31.48
#Mann= 3 , 0 , 0
       0     .22       0  118.01     .17       0  380.83     .22       0
#XS Ineff= 1 ,-1
       0  118.01      20
Permanent Ineff=
       F
Bank Sta=118.01,380.83
XS Rating Curve= 0 ,0
Exp/Cntr=0.3,0.1

Type RM Length L Ch R = 1 ,729.66  ,1785.368,1785.368,1785.368
BEGIN DESCRIPTION:
WK15
END DESCRIPTION:
Node Name=WK15
XS GIS Cut Line= 2
 456677.599504883176700.20887002 456838.889904883176250.62797002
#Sta/Elev= 28
     500   18.98    2450   16.98    4370   15.98    5530   14.98    6560   13.98
    7000   11.48    7025   11.38    7050   11.58    7075   11.68    7095   12.38
    7100   11.08    7105    7.68    7110    6.18    7120    4.78    7130    3.38
    7140    2.48    7160    4.08    7170    5.98    7190    7.98    7200   11.08
    7210   12.78    7225   11.68    7250   13.58    7300   13.98    7380   14.98
    7520   15.98    7600   16.98    8100   18.98
#Mann= 3 , 0 , 0
     500     .22       0    7095     .17       0    7210     .22       0
Bank Sta=7095,7210
XS Rating Curve= 0 ,0
Exp/Cntr=0.3,0.1

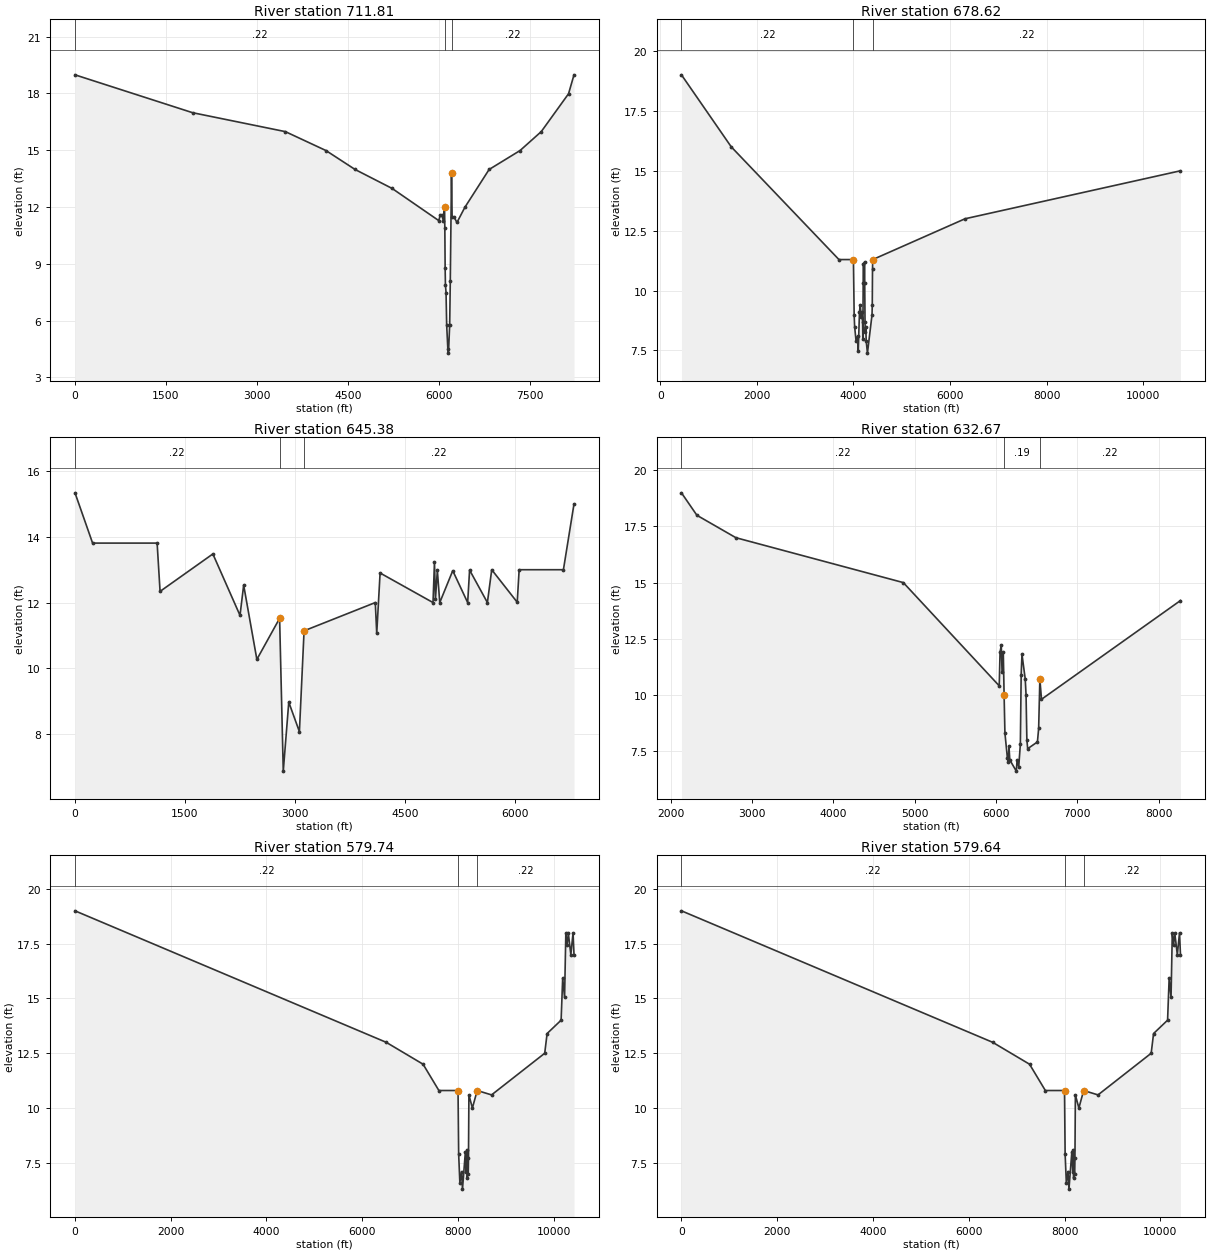
Type RM Length L Ch R = 1 ,711.81  ,3318.996,3318.996,3318.996
BEGIN DESCRIPTION:
WK14
END DESCRIPTION:
Node Name=WK14
XS GIS Cut Line= 2
457102.1360048793176981.74307002 457281.206304883176548.67217002
#Sta/Elev= 30
       1   18.98    1940   16.98    3470   15.98    4140   14.98    4620   13.98
    5230   12.98    6000   11.28    6025   11.58    6050   11.58    6075   11.28
    6095   11.98    6100   10.88    6105    8.78    6110    7.88    6120    7.48
    6130    5.78    6150    4.48    6160    4.28    6180    5.78    6190    8.08
    6210   13.78    6220   11.48    6250   11.48    6300   11.18    6430   11.98
    6830   13.98    7340   14.98    7690   15.98    8140   17.98    8230   18.98
#Mann= 3 , 0 , 0
       1     .22       0    6095     .18       0    6210     .22       0
Bank Sta=6095,6210
XS Rating Curve= 0 ,0
Exp/Cntr=0.3,0.1

Type RM Length L Ch R = 1 ,678.62  ,3324.147,3324.147,3324.147
BEGIN DESCRIPTION:
WEK11
END DESCRIPTION:
Node Name=WEK11
XS GIS Cut Line= 2
457559.9719048793177663.64977002 457967.642704883177438.85927002
#Sta/Elev= 30
     440   18.99    1470   15.99    3700   11.29    4000   11.29    4015    8.99
    4025    8.49    4055    7.89    4085    8.09    4100    7.49    4125    9.09
    4140    9.39    4165    8.89    4175    9.09    4190    8.69    4195    7.99
    4202   10.32    4203   11.09    4233   11.19  4233.5   10.32    4240    8.69
    4245    8.29    4255    8.49    4265    7.89    4290    7.39    4385    8.99
    4390    9.39    4395   10.89    4400   11.29    6310   12.99   10770   14.99
#Mann= 3 , 0 , 0
     440     .22       0    4000     .18       0    4400     .22       0
Bank Sta=4000,4400
XS Rating Curve= 0 ,0
Exp/Cntr=0.3,0.1

Type RM Length L Ch R = 1 ,645.38  ,1271.129,1271.129,1271.129
BEGIN DESCRIPTION:
MFL_Swamp
END DESCRIPTION:
Node Name=MFL_Swamp
XS GIS Cut Line= 2
 458158.511704883178457.50277002458316.381727685 3178386.7275856
#Sta/Elev= 30
       0   15.34     240   13.81    1120   13.81    1160   12.34    1880   13.48
    2250   11.61    2300   12.53    2480   10.27    2790   11.52    2840    6.87
    2915    8.97    3060    8.07 3123.69   11.14 4094.68      12 4114.36   11.06
 4160.28    12.9 4881.96      12 4901.64   13.23 4914.76    12.1    4941   12.98
 4973.81      12 5150.95   12.97 5354.33      12 5380.57   12.99 5623.32      12
 5682.36      13 6030.08   12.01 6056.32      13  6659.9      13 6804.24      15
#Mann= 3 , 0 , 0
       0     .22       0    2790     .19       0 3123.69     .22       0
Bank Sta=2790,3123.69
XS Rating Curve= 0 ,0
Exp/Cntr=0.3,0.1

Type RM Length L Ch R = 1 ,632.67  ,5292.979,5292.979,5292.979
BEGIN DESCRIPTION:
WK12
END DESCRIPTION:
Node Name=WK12
XS GIS Cut Line= 2
 458386.943904883178788.98237002458672.6945048793178598.48197002
#Sta/Elev= 30
    2130      19    2320      18    2800      17    4860      15    6040    10.4
    6050    11.9    6065    12.2    6075      11    6090    11.9    6100      10
    6110     8.3    6140     7.2    6150       7    6160     7.7    6170     7.1
    6250     6.6    6260     7.1    6280     6.8    6300     7.8    6310    10.9
    6320    11.8    6360    10.7    6370      10    6380       8    6390     7.6
    6510     7.9    6525     8.5    6540    10.7    6560     9.8    8270    14.2
#Mann= 3 , 0 , 0
    2130     .22       0    6100     .19       0    6540     .22       0
Bank Sta=6100,6540
XS Rating Curve= 0 ,0
Exp/Cntr=0.3,0.1

Type RM Length L Ch R = 1 ,579.74  ,10,10,10
BEGIN DESCRIPTION:
WEK10
END DESCRIPTION:
Node Name=WEK10
XS GIS Cut Line= 2
 458952.095004883180166.93507002 459206.095504883180065.33487002
#Sta/Elev= 30
       1      19    6500      13    7270      12    7600    10.8    8000    10.8
    8013     7.9    8038     6.6    8073     7.1    8093     6.3    8153       8
    8173     7.1    8183     8.1    8188     6.8    8213       7    8218     7.7
    8227    10.6    8300      10    8400    10.8    8700    10.6    9810    12.5
    9860    13.410152.57   14.0110185.37   15.9310224.74   15.0510250.98   17.98
10277.23   17.4410303.47   17.9710355.96      1710401.89      1810421.57      17
#Mann= 3 , 0 , 0
       1     .22       0    8000     .19       0    8400     .22       0
Bank Sta=8000,8400
XS Rating Curve= 0 ,0
Exp/Cntr=0.3,0.1

Type RM Length L Ch R = 1 ,579.64  ,3507.093,3507.093,3507.093
BEGIN DESCRIPTION:
WEK10
END DESCRIPTION:
XS GIS Cut Line= 2
 458952.095004883180166.93507002 459206.095504883180065.33487002
#Sta/Elev= 30
       1      19    6500      13    7270      12    7600    10.8    8000    10.8
    8013     7.9    8038     6.6    8073     7.1    8093     6.3    8153       8
    8173     7.1    8183     8.1    8188     6.8    8213       7    8218     7.7
    8227    10.6    8300      10    8400    10.8    8700    10.6    9810    12.5
    9860    13.410152.57   14.0110185.37   15.9310224.74   15.0510250.98   17.98
10277.23   17.4410303.47   17.9710355.96      1710401.89      1810421.57      17
#Mann= 3 , 0 , 0
       1     .22       0    8000     .19       0    8400     .22       0
Bank Sta=8000,8400
XS Rating Curve= 0 ,0
Exp/Cntr=0.3,0.1

River Reach=wekiva          ,wekiva_riv_down
Reach XY= 30
 459343.436962483181018.99032073459461.8250048793181863.19517002
 459349.197004883182515.39367002 459507.275004883183107.96967002
 459431.118504883183879.39167002459555.5362048793184233.60147002
 459488.652604883184554.61977002459664.7192048793184968.68207002
459442.9677048793186158.69157002459244.9149048793186570.03217002
459089.1644048793187956.20287002459460.6590048793188831.89917002
460117.0263048793189514.91867002460112.7944048793189640.81767002
460325.9763048793189795.85487002 460611.364904883189758.82587002
460688.0680048793190017.60627002 461149.186104883190398.13777002
 461144.107804883190567.62517002 461530.691704883190577.78177002
461981.3909048793191252.35677002 461935.051704883191338.68737002
462130.1245048793191438.08417002462271.4698048793191356.83177002
 462600.447004883191585.85677002462950.8076048793192145.74307002
462938.2811048793192926.86147002 463159.926804883193226.79717002
 463251.970604883193157.49987002 463500.442604883193623.54027002