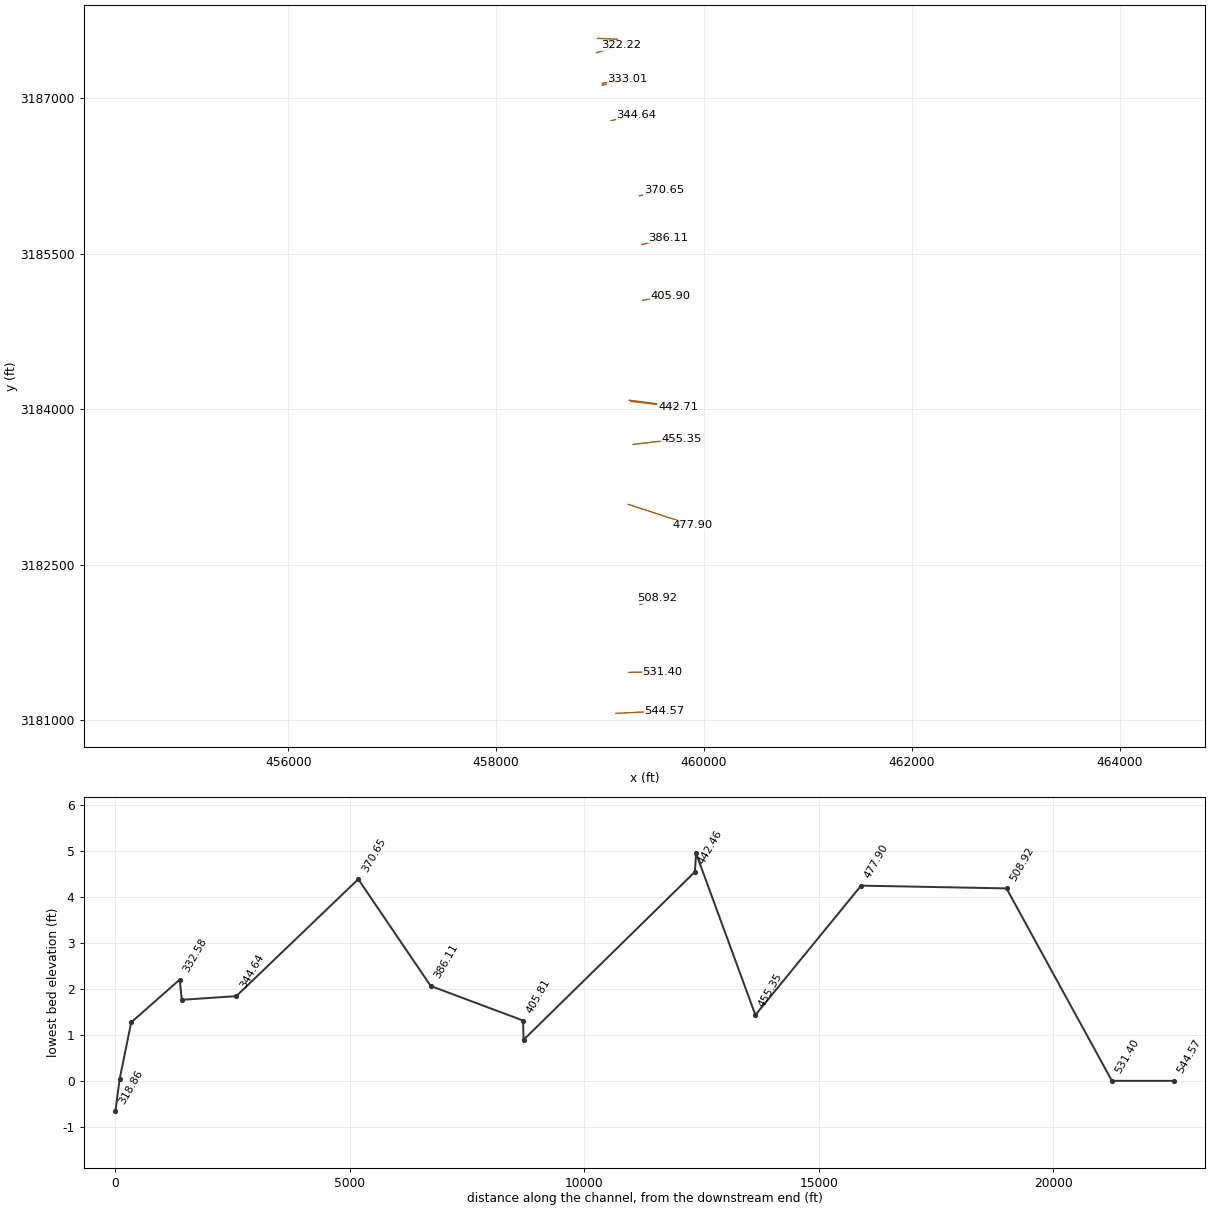
HEC-RAS study wekiva_ras.prj: wekiva_ras

--- wekiva_ras.g01 (geometry) --- (continued)

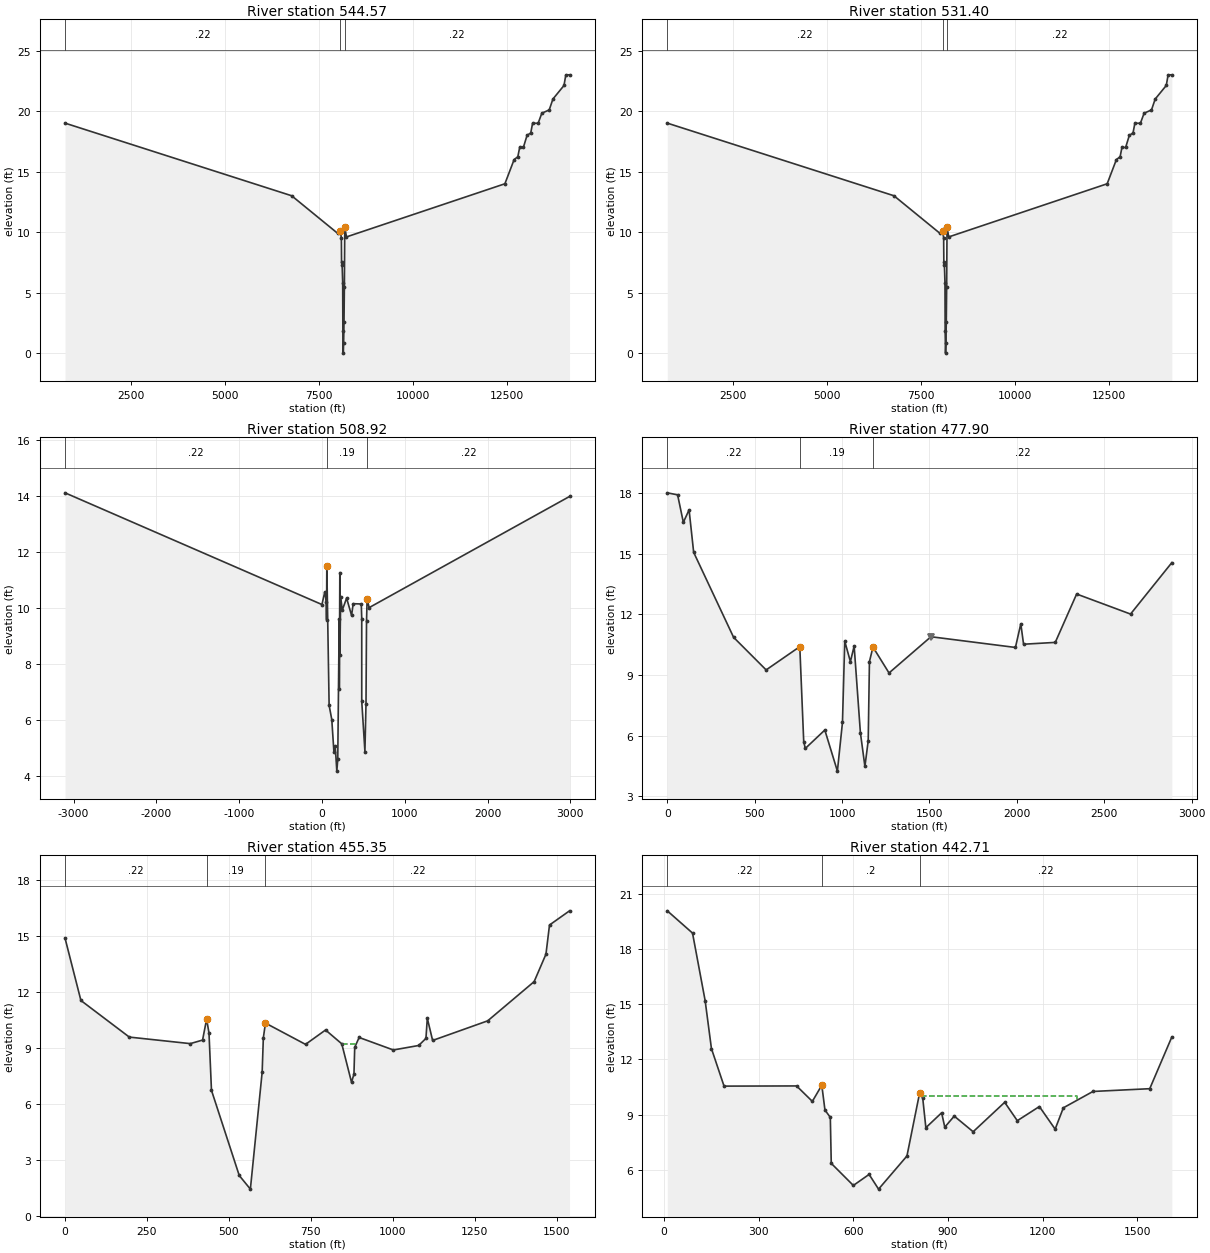
Type RM Length L Ch R = 1 ,544.57  ,1316.962,1316.962,1316.962
BEGIN DESCRIPTION:
WK11
END DESCRIPTION:
Node Name=WK11
XS GIS Cut Line= 2
 459150.085604883181066.69207002459617.8699048793181089.97547002
#Sta/Elev= 30
     760   19.01    6780   13.01    8000    9.91    8075   10.11    8100    9.51
    8105    7.51    8120    7.31    8135    5.81    8140    1.81    8150     .01
    8160     .81    8170    2.61    8180    5.51    8190   10.41    8235    9.61
12443.03      14 12688.3      1612786.41   16.2312835.47      1712933.58      17
13031.69      18 13129.8    18.213178.85      1913326.02      1913424.13   19.83
13620.34    20.113718.46      2114012.78   22.1214061.84      2314159.95      23
#Mann= 3 , 0 , 0
     760     .22       0    8075     .19       0    8190     .22       0
Bank Sta=8075,8190
XS Rating Curve= 0 ,0
Exp/Cntr=0.3,0.1

Type RM Length L Ch R = 1 ,531.40  ,2248.064,2248.064,2248.064
BEGIN DESCRIPTION:
WEK9-copy of WK11
END DESCRIPTION:
Node Name=WEK9-copy of WK1
XS GIS Cut Line= 2
459275.9457048793181462.33767002 459599.796304883181468.68767002
#Sta/Elev= 30
     760   19.01    6780   13.01    8000    9.91    8075   10.11    8100    9.51
    8105    7.51    8120    7.31    8135    5.81    8140    1.81    8150     .01
    8160     .81    8170    2.61    8180    5.51    8190   10.41    8235    9.61
12443.03      14 12688.3      1612786.41   16.2312835.47      1712933.58      17
13031.69      18 13129.8    18.213178.85      1913326.02      1913424.13   19.83
13620.34    20.113718.46      2114012.78   22.1214061.84      2314159.95      23
#Mann= 3 , 0 , 0
     760     .22       0    8075     .19       0    8190     .22       0
Bank Sta=8075,8190
XS Rating Curve= 0 ,0
Exp/Cntr=0.3,0.1

Type RM Length L Ch R = 1 ,508.92  ,3101.706,3101.706,3101.706
BEGIN DESCRIPTION:
XS20
END DESCRIPTION:
Node Name=XS20
XS GIS Cut Line= 2
 459382.978204883182113.81057002459543.4649048793182178.38367002
#Sta/Elev= 30
-3102.51   14.13       0   10.14   34.59   10.59    53.2   10.24   55.67     9.6
   58.88   11.52   86.84    6.54  119.05    6.03  144.51    4.88  160.75    5.07
  179.83    4.19  191.14    4.61  208.59    9.63  209.83    7.12  216.06   11.28
  216.99    8.35  226.31   10.41  245.77    9.94  297.99   10.37  357.95    9.75
  377.47   10.17  475.33   10.16  480.81    9.62  480.85    6.68  519.11    4.89
  532.14    6.59  538.39    9.54  545.77   10.34  569.93   10.03    2990      14
#Mann= 3 , 0 , 0
-3102.51     .22       0   58.88     .19       0  545.77     .22       0
Bank Sta=58.88,545.77
XS Rating Curve= 0 ,0
Exp/Cntr=0.3,0.1

Type RM Length L Ch R = 1 ,477.90  ,2254.396,2254.396,2254.396
BEGIN DESCRIPTION:
XS19
END DESCRIPTION:
Node Name=XS19
XS GIS Cut Line= 2
459271.5415048793183081.79267002 459890.675604883182878.71667002
#Sta/Elev= 30
       0      18   59.04    17.9   91.84   16.54  124.64   17.16  150.88   15.06
  379.37   10.86  565.53    9.25  758.07    10.4   780.5    5.71  789.52    5.37
  901.24    6.28  973.18    4.25 1002.23    6.66 1015.18   10.67  1047.6    9.66
 1069.01   10.43 1104.76    6.15 1130.61    4.48 1149.49    5.75 1156.51    9.66
  1176.7   10.38 1268.56     9.1 1508.51   10.89 1991.75   10.36  2022.5   11.53
  2038.3   10.52 2219.63   10.61 2341.96      13 2650.29   12.01 2886.45   14.55
#Mann= 3 , 0 , 0
       0     .22       0  758.07     .19       0  1176.7     .22       0
Levee=0,,,-1,1508.511,10.89,,
Bank Sta=758.07,1176.7
XS Rating Curve= 0 ,0
Exp/Cntr=0.3,0.1

Type RM Length L Ch R = 1 ,455.35  ,1264.567,1264.567,1264.567
BEGIN DESCRIPTION:
XS18
END DESCRIPTION:
Node Name=XS18
XS GIS Cut Line= 2
 459315.849904883183660.11847002459780.8486048793183714.78067002
#Sta/Elev= 30
       0   14.88    48.5   11.54  196.17    9.58  382.17    9.23  419.67    9.42
  432.03   10.54  439.28     9.8  446.85    6.73  531.56    2.17  565.54    1.44
   601.5     7.7  605.09    9.54  611.58   10.33  733.81    9.19  794.93    9.96
   844.4    9.22  874.17    7.16  881.58     7.6   883.9    9.03  897.32    9.56
 1001.73    8.89 1078.97    9.13 1101.23    9.51 1105.35   10.59 1121.59     9.4
 1289.61   10.45 1431.37   12.55 1467.39   14.02 1478.21   15.58 1539.32   16.34
#Mann= 3 , 0 , 0
       0     .22       0  432.03     .19       0  611.58     .22       0
#XS Ineff= 1 ,-1
   844.4   883.9    9.22
Permanent Ineff=
       T
Bank Sta=432.03,611.58
XS Rating Curve= 0 ,0
Exp/Cntr=0.3,0.1

Type RM Length L Ch R = 1 ,442.71  ,25.1312,25.1312,25.1312
BEGIN DESCRIPTION:
MFL_RailRoad
END DESCRIPTION:
Node Name=MFL_RailRoad
XS GIS Cut Line= 3
459294.4409314813184076.20246875 459738.939404883184021.20627002
459748.8637314813184019.97836875
#Sta/Elev= 30
      10   20.08      90   18.87     130    15.2     150   12.59     190   10.55
     420   10.56     470    9.72     500    10.6     510    9.25     527    8.85
     530    6.35     600    5.15     650    5.75     680    4.95     770    6.75
     810   10.16     820    9.91     830    8.29     880     9.1     890    8.32
     920    8.92     980    8.07    1080    9.67    1120    8.67    1190    9.44
    1240    8.21    1266    9.37    1360   10.26    1540   10.41    1610   13.22
#Mann= 3 , 0 , 0
      10     .22       0     500      .2       0     810     .22       0
#XS Ineff= 1 ,-1
     820    1310      10
Permanent Ineff=
       F
Bank Sta=500,810
XS Rating Curve= 0 ,0
Exp/Cntr=0.3,0.1

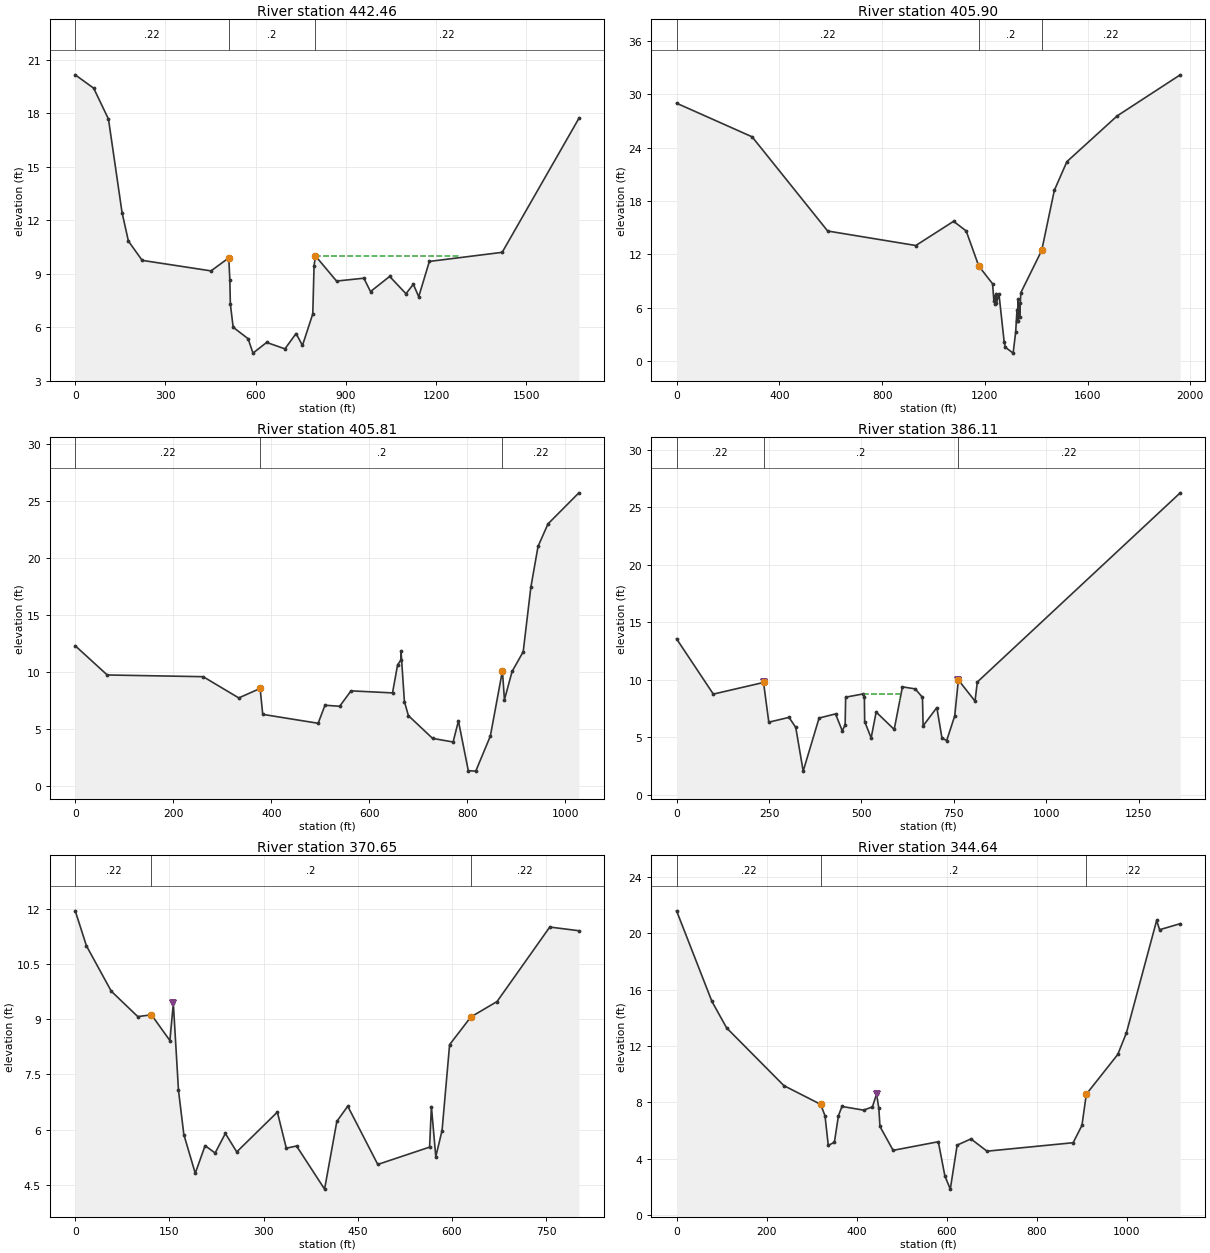
Type RM Length L Ch R = 1 ,442.46  ,3655.741,3655.741,3655.741
BEGIN DESCRIPTION:
XS17
END DESCRIPTION:
Node Name=XS17
XS GIS Cut Line= 2
 459280.081504883184086.22197002459785.7691048793184022.15867002
#Sta/Elev= 30
       0   20.15   61.42    19.4  110.54   17.67  155.69   12.43  176.82   10.83
  222.58    9.75  451.56    9.16  510.58    9.89  514.08    8.64   515.8     7.3
  525.13       6  574.67    5.36  591.09    4.55  636.43    5.15  697.31    4.79
  734.32    5.65   755.5    4.98  789.84    6.75  794.07    9.44  798.73      10
  868.83    8.59   959.7    8.75  981.77       8 1045.46    8.85 1099.65    7.88
 1124.21    8.41 1142.03    7.71 1177.45    9.69 1419.54    10.2 1674.61   17.71
#Mann= 3 , 0 , 0
       0     .22       0  510.58      .2       0  798.73     .22       0
#XS Ineff= 1 ,-1
  798.73 1274.28      10
Permanent Ineff=
       F
Bank Sta=510.58,798.73
XS Rating Curve= 0 ,0
Exp/Cntr=0.3,0.1

Type RM Length L Ch R = 1 ,405.90  ,9.2192,9.2192,9.2192
BEGIN DESCRIPTION:
MFL_RailRoadGage
END DESCRIPTION:
Node Name=MFL_RailRoadGage
XS GIS Cut Line= 2
 459603.299504883185076.81517002 459677.277104883185087.76887002
#Sta/Elev= 30
       0      29  294.06   25.22  588.11   14.63  931.18      13 1078.21   15.72
 1127.22   14.64 1176.23   10.69    1230     8.7    1235     6.8    1240     7.3
    1240     6.4    1245     7.6    1245    6.55    1255     7.5    1275     2.2
    1280    1.55    1310      .9    1320     3.3    1325     5.8    1325     4.5
    1330    6.95    1330    4.55    1335    6.48    1335       5    1340     7.7
 1421.28   12.45 1470.29    19.2  1519.3   22.43 1715.33   27.58 1960.38   32.19
#Mann= 3 , 0 , 0
       0     .22       0 1176.23      .2       0 1421.28     .22       0
Bank Sta=1176.23,1421.28
XS Rating Curve= 0 ,0
Exp/Cntr=0.3,0.1

Type RM Length L Ch R = 1 ,405.81  ,1969.554,1969.554,1969.554
BEGIN DESCRIPTION:
XS16
END DESCRIPTION:
Node Name=XS16
XS GIS Cut Line= 2
459410.1413048793185050.46617002459718.6545048793185096.86167002
#Sta/Elev= 30
       0    12.3   65.29    9.74  261.09    9.59  333.74    7.73  377.28    8.56
  382.63    6.29  495.65    5.51  509.62    7.09  539.61       7  562.74    8.35
  647.44    8.17  657.82   10.64  664.71   11.04  664.79    11.8  671.71    7.41
  679.81    6.18   729.1    4.19  771.02    3.87  781.92    5.71  802.06    1.36
  817.27    1.32  847.04    4.39  871.69   10.11  875.78    7.57   891.4   10.05
  914.04   11.77  929.68   17.42  944.36      21  964.64   22.97  1027.7   25.69
#Mann= 3 , 0 , 0
       0     .22       0  377.28      .2       0  871.69     .22       0
#XS Ineff= 1 ,-1
       0  664.79    11.8
Permanent Ineff=
       T
Bank Sta=377.28,871.69
XS Rating Curve= 0 ,0
Exp/Cntr=0.3,0.1

Type RM Length L Ch R = 1 ,386.11  ,1546.096,1546.096,1546.096
BEGIN DESCRIPTION:
XS15
END DESCRIPTION:
Node Name=XS15
XS GIS Cut Line= 2
 459399.141704883185586.81687002459651.3766048793185653.23407002
#Sta/Elev= 30
       0   13.56   99.37    8.76  235.15    9.77  249.36    6.32  304.14    6.74
  322.28    5.86  342.34    2.07  385.31    6.68  429.82    7.04     448    5.57
  455.79    6.09  457.13    8.49  504.92    8.78  507.78    8.55  508.57    6.38
  526.09    4.95  539.65     7.2  588.42    5.69  610.73    9.39  645.37    9.21
  664.84    8.48  666.61       6  703.68    7.59  717.54    4.95  730.27    4.72
  752.03    6.86  761.89    9.99  806.94    8.15  813.18    9.81 1361.78   26.24
#Mann= 3 , 0 , 0
       0     .22       0  235.15      .2       0  761.89     .22       0
Levee=-1,235.15,9.77,-1,761.89,9.99,,
#XS Ineff= 3 ,-1
  504.92  603.38    8.78  610.73  761.89    9.39  761.89  837.84    9.99
Permanent Ineff=
       F       F       F
Bank Sta=235.15,761.89
XS Rating Curve= 0 ,0
Exp/Cntr=0.3,0.1

Type RM Length L Ch R = 1 ,370.65  ,2601.247,2601.247,2601.247
BEGIN DESCRIPTION:
XS14
END DESCRIPTION:
Node Name=XS14
XS GIS Cut Line= 2
459377.3931048793186056.84457002459614.9912048793186110.32587002
#Sta/Elev= 30
       0   11.94   17.89   10.99   57.42    9.76   99.71    9.07   121.4    9.12
  150.84    8.42  156.28    9.43   164.5    7.07  173.03    5.87  191.23    4.82
  206.89    5.57  222.88    5.37  239.15     5.9  257.33     5.4  322.01    6.48
  336.28     5.5  352.58    5.56  397.24    4.39  416.81    6.23  434.15    6.64
     482    5.06  564.53    5.53  567.41    6.63   574.4    5.27  584.38    5.98
  596.42    8.31  630.25    9.06  672.03    9.48  755.96    11.5  802.37    11.4
#Mann= 3 , 0 , 0
       0     .22       0   121.4      .2       0  630.25     .22       0
Levee=-1,156.28,9.43,0,,,,
Bank Sta=121.4,630.25
XS Rating Curve= 0 ,0
Exp/Cntr=0.3,0.1

Type RM Length L Ch R = 1 ,344.64  ,1162.795,1162.795,1162.795
BEGIN DESCRIPTION:
XS13
END DESCRIPTION:
Node Name=XS13
XS GIS Cut Line= 2
 459106.813404883186782.88367002 459346.807304883186839.11017002
#Sta/Elev= 30
       0   21.58   78.52   15.16  111.24   13.28  238.33    9.19   320.1    7.86
  329.76    7.05  337.03    4.95  350.61    5.17  359.58    7.05   367.4    7.71
  415.46    7.45  435.06    7.68  444.35    8.59  449.38    7.57  451.88    6.29
  481.13     4.6  581.49    5.21  596.09    2.78   608.1    1.85  623.34    4.97
  653.98    5.41  689.68    4.54     881    5.14  900.58    6.37   910.3    8.58
  980.19    11.4  999.48   12.94 1066.58    20.9 1073.12   20.24 1118.93   20.67
#Mann= 3 , 0 , 0
       0     .22       0   320.1      .2       0   910.3     .22       0
Levee=-1,444.3531,8.59,0,,,,
Bank Sta=320.1,910.3
XS Rating Curve= 0 ,0
Exp/Cntr=0.3,0.1

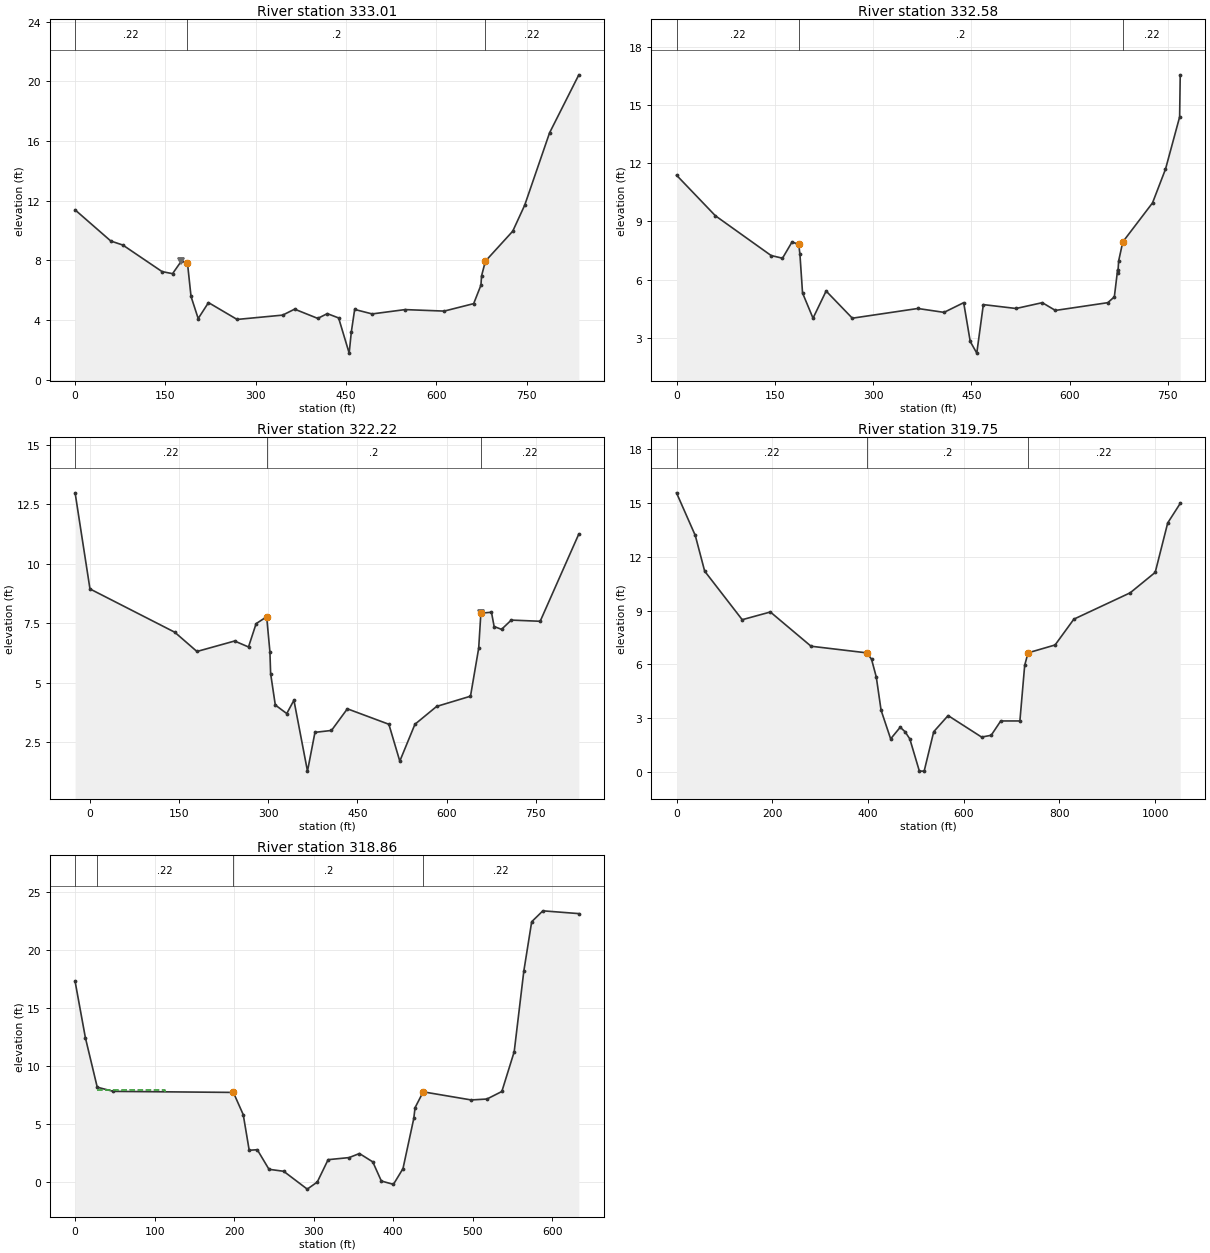
Type RM Length L Ch R = 1 ,333.01  ,43.1102,43.1102,43.1102
BEGIN DESCRIPTION:
XS12
END DESCRIPTION:
Node Name=XS12
XS GIS Cut Line= 2
 459017.819704883187123.44757002459264.5624048793187183.65137002
#Sta/Elev= 30
       0   11.38   59.29    9.29   79.28    9.02  144.39    7.24   161.8     7.1
  176.38    7.94  186.59    7.81   192.5    5.57  204.39    4.09  221.48    5.16
  268.97    4.03  344.66    4.32  364.51    4.72  402.91     4.1  418.79    4.42
  437.56    4.13  455.07    1.77  458.61    3.18   464.2     4.7  493.25     4.4
  547.84    4.69  612.88    4.59  661.78    5.09  673.87    6.33   674.9    6.95
  681.28    7.94  726.65    9.95  746.48   11.69  787.83   16.55   836.4   20.44
#Mann= 3 , 0 , 0
       0     .22       0  186.59      .2       0  681.28     .22       0
Levee=-1,176.38,7.94,0,,,,
Bank Sta=186.59,681.28
XS Rating Curve= 0 ,0
Exp/Cntr=0.3,0.1

Type RM Length L Ch R = 1 ,332.58  ,1035.531,1035.531,1035.531
BEGIN DESCRIPTION:
MFL_Flats
END DESCRIPTION:
Node Name=MFL_Flats
XS GIS Cut Line= 3
459020.8642946283187142.28128962 459030.098904883187144.19097002
459236.797342329 3187186.9353788
#Sta/Elev= 30
       0   11.38   59.29    9.29  144.39    7.24   161.8     7.1  176.38    7.94
  186.59    7.81   188.4    7.31   192.4    5.31   208.4    4.01   228.4    5.41
   268.4    4.01   368.4    4.51   408.4    4.31   438.4    4.81   448.4    2.81
   458.4    2.21   468.4    4.71   518.4    4.51   558.4    4.81   578.4    4.41
   658.4    4.81   668.4    5.11   673.4    6.51  673.87    6.33   674.9    6.95
  681.28    7.94  726.65    9.95  746.48   11.69  768.06   14.38  768.97   16.55
#Mann= 3 , 0 , 0
       0     .22       0  186.59      .2       0  681.28     .22       0
Bank Sta=186.59,681.28
XS Rating Curve= 0 ,0
Exp/Cntr=0.3,0.1

Type RM Length L Ch R = 1 ,322.22  ,247.605,247.605,247.605
BEGIN DESCRIPTION:
XS11
END DESCRIPTION:
Node Name=XS11
XS GIS Cut Line= 2
 458963.185504883187436.30517002459201.5125048793187510.18837002
#Sta/Elev= 30
     -25   12.98       0    8.94  142.61    7.12  179.95    6.31  243.27    6.75
  266.67     6.5  279.47    7.48  297.23    7.77  302.67     6.3  303.89    5.38
  311.74    4.06  331.01     3.7  343.07    4.26  365.88    1.28  378.46    2.91
  406.25    2.99  432.97     3.9  502.78    3.25  521.17     1.7  546.64    3.25
  583.13       4  640.08    4.43  653.87    6.45  657.53    7.92  675.35    7.96
  679.82    7.36  692.29    7.24  708.66    7.63  757.29    7.58   822.3   11.25
#Mann= 3 , 0 , 0
     -25     .22       0  297.23      .2       0  657.53     .22       0
Levee=0,,,-1,657.53,7.92,,
#XS Ineff= 1 ,-1
   79.45  297.23     7.7
Permanent Ineff=
       F
Bank Sta=297.23,657.53
XS Rating Curve= 0 ,0
Exp/Cntr=0.3,0.1

Type RM Length L Ch R = 1 ,319.75  ,88.8451,88.8451,88.8451
BEGIN DESCRIPTION:
MFL_SR46E
END DESCRIPTION:
Node Name=MFL_SR46E
XS GIS Cut Line= 2
459015.1934048793187548.55247002 459144.574904883187545.90667002
#Sta/Elev= 30
       0   15.57   39.22   13.19   58.83    11.2  137.26    8.49  196.09    8.92
  281.06    7.01  397.38    6.64  407.38    6.29  417.38    5.29  427.38    3.44
  447.38    1.84  467.38    2.49  477.38    2.24  487.38    1.84  507.38     .04
  517.38     .04  537.38    2.24  567.38    3.14  637.38    1.94  657.38    2.04
  677.38    2.84  717.38    2.84  727.38    5.94  734.38    6.64  790.89    7.08
  830.11    8.52  947.76    9.99 1000.05   11.13 1026.19   13.89 1052.34   14.98
#Mann= 3 , 0 , 0
       0     .22       0  397.38      .2       0  734.38     .22       0
Bank Sta=397.38,734.38
XS Rating Curve= 0 ,0
Exp/Cntr=0.3,0.1

Type RM Length L Ch R = 1 ,318.86  ,5.4462,5.4462,5.4462
BEGIN DESCRIPTION:
XS10
END DESCRIPTION:
Node Name=XS10
XS GIS Cut Line= 2
458974.1189048793187575.68317002 459166.370904883187566.64927002
#Sta/Elev= 30
       0   17.26   12.98   12.39   27.84    8.14   48.09    7.78     199    7.69
  211.42    5.77  218.91     2.7  229.06    2.75  243.78    1.06  262.24     .89
   291.9    -.65  304.49    -.04  318.13    1.89  344.52    2.07  357.51    2.42
  374.28     1.7  385.06     .05  400.25    -.24  412.27    1.12  425.87    5.45
  427.42    6.37  437.69    7.74   498.1    7.04  517.84    7.12  536.57    7.77
  552.12    11.2  564.22   18.16  574.11   22.41  588.18   23.35  633.37   23.11
#Mann= 4 , 0 , 0
       0     .22       0   27.84     .22       0     199      .2       0
  437.69     .22       0
#XS Ineff= 1 ,-1
   27.84  112.66     7.9
Permanent Ineff=
       F
Bank Sta=199,437.69
XS Rating Curve= 0 ,0
Exp/Cntr=0.5,0.3