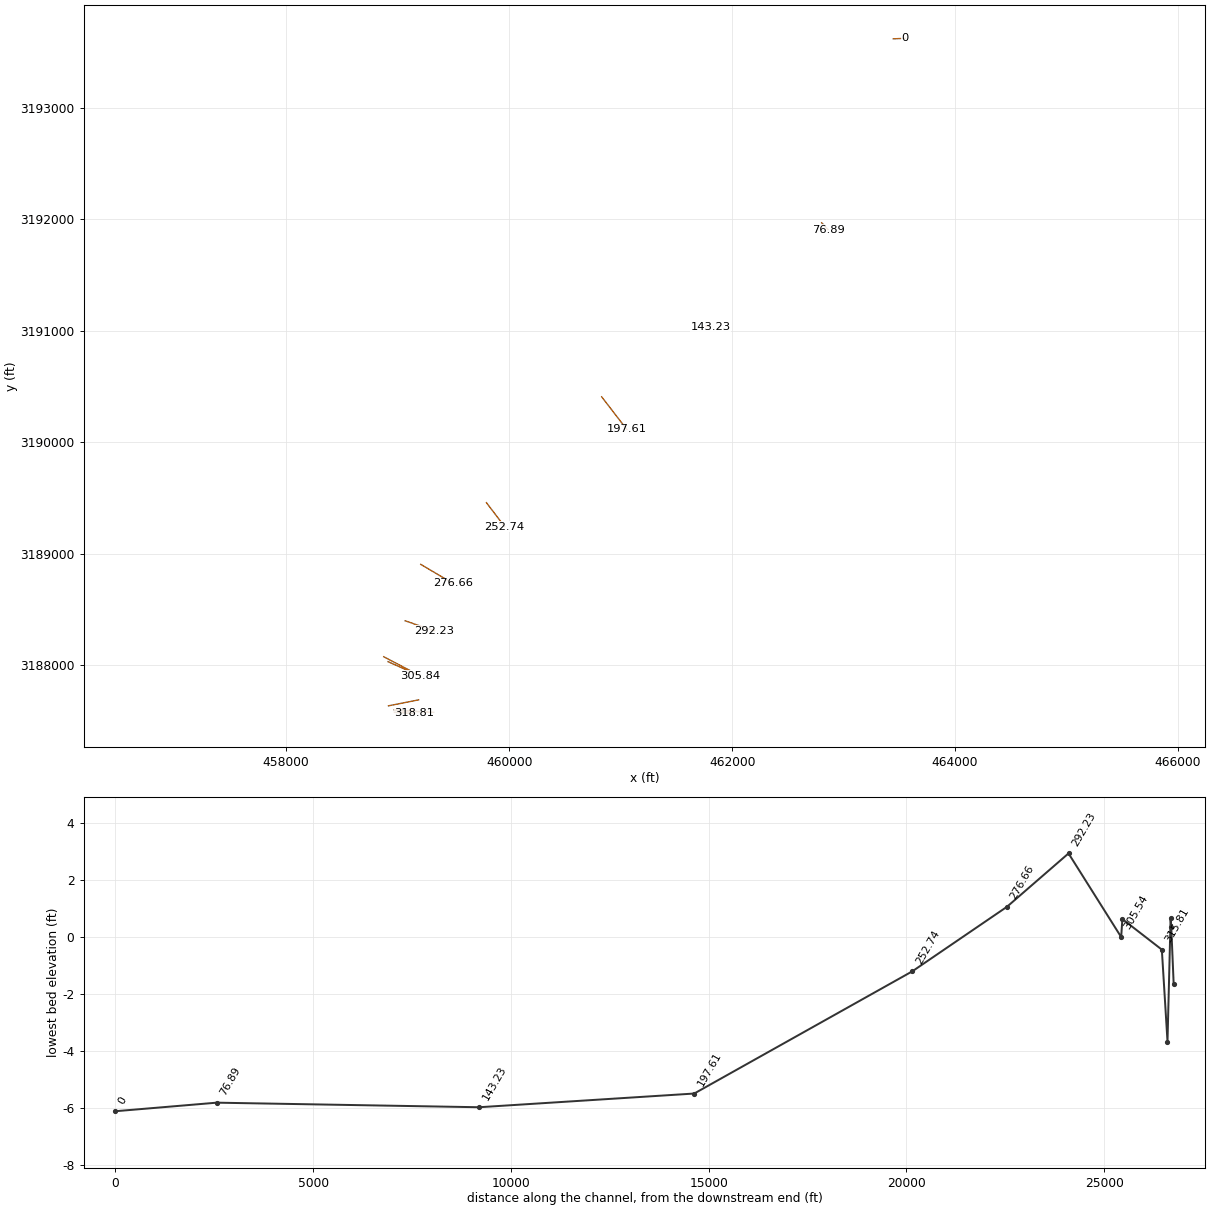
HEC-RAS study wekiva_ras.prj: wekiva_ras

--- wekiva_ras.g01 (geometry) --- (continued)

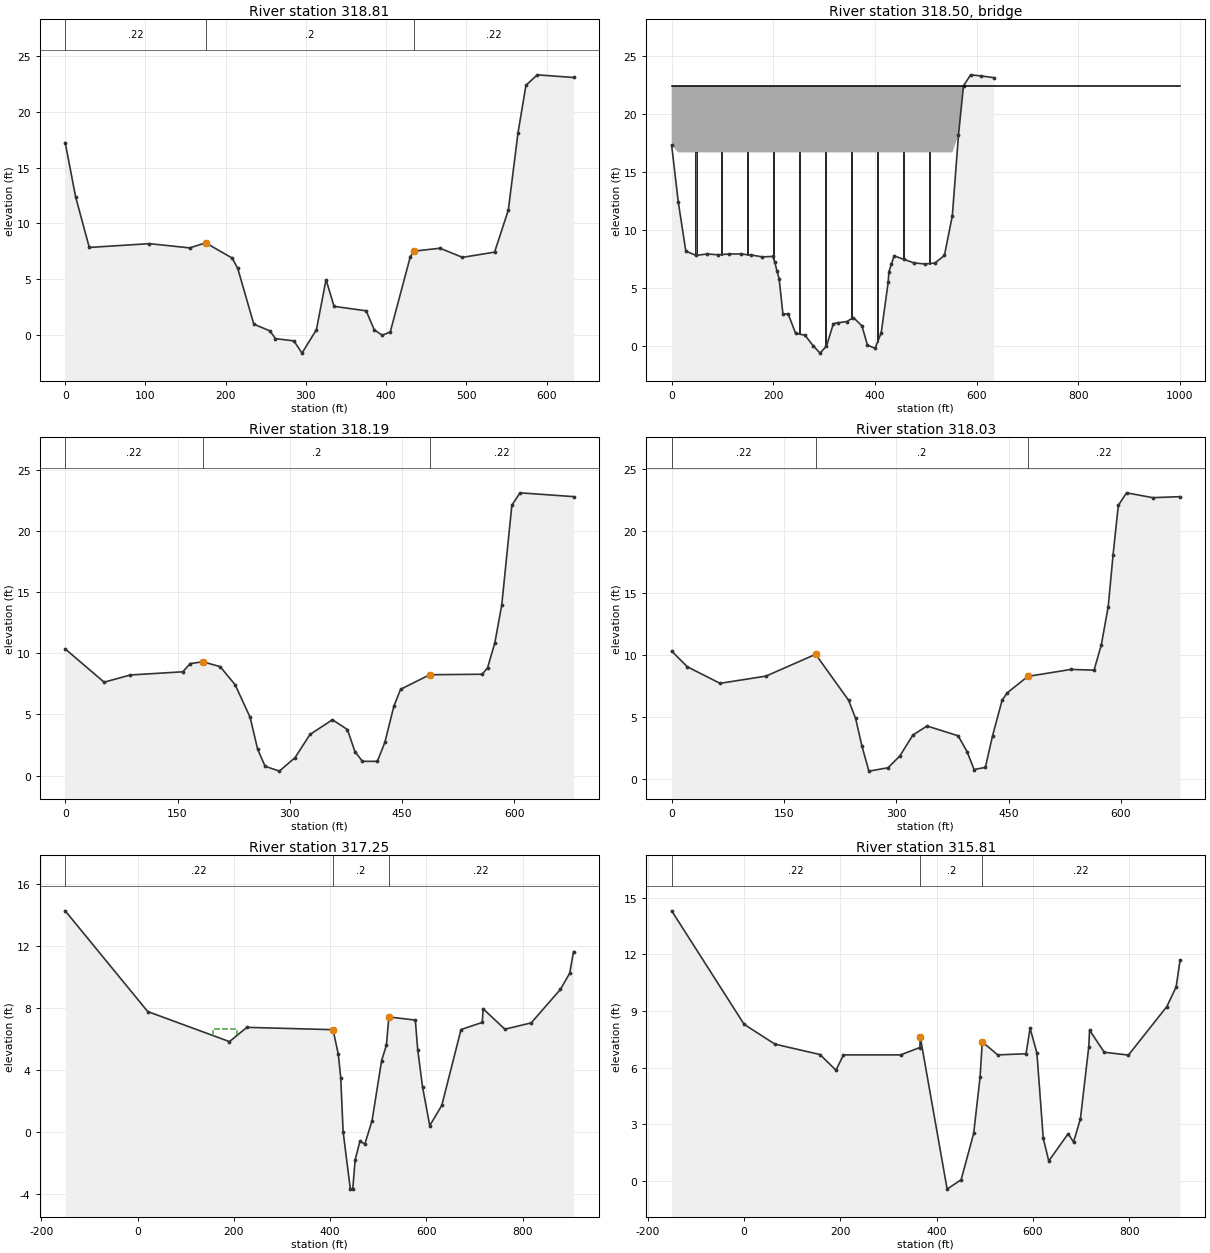
Type RM Length L Ch R = 1 ,318.81  ,61.1549,61.1549,61.1549
BEGIN DESCRIPTION:
MFL_SR46B
END DESCRIPTION:
Node Name=MFL_SR46B
XS GIS Cut Line= 2
 458972.529304883187577.41857002459149.2051048793187568.68737002
#Sta/Elev= 30
       0   17.26   12.98   12.39      30    7.85     105    8.19     155    7.81
     175    8.26     208     6.9     215    5.96     235     .96     255     .36
     262    -.34     285    -.54     295   -1.64     313     .46     325    4.96
     335    2.56     375    2.16     385     .46     395    -.04     405     .26
     430    7.02     435    7.52     467    7.78     495    6.96     535    7.43
  552.12    11.2  564.22   18.16  574.11   22.41  588.18   23.35  633.37   23.11
#Mann= 3 , 0 , 0
       0     .22       0     175      .2       0     435     .22       0
Bank Sta=175,435
XS Rating Curve= 0 ,0
Exp/Cntr=0.5,0.3

Type RM Length L Ch R = 3 ,318.50  ,,,
BEGIN DESCRIPTION:
SR46
SR46
END DESCRIPTION:
Bridge Culvert--1,0,-1,-1, 0
Deck Dist Width WeirC Skew NumUp NumDn MinLoCord MaxHiCord MaxSubmerge Is_Ogee
10,42,2.6,0, 2, 2, , , 0.98, 0, 0,0,,
       0    1000
   22.41   22.41
   16.66   16.66
       0    1000
   22.41   22.41
   16.66   16.66
Pier Skew, UpSta & Num, DnSta & Num=  ,47.6, 2 ,70.62, 2 , 0 , 0 , 0 ,,
    2.51    2.51
      -5      20
    2.51    2.51
      -5      20
Pier Skew, UpSta & Num, DnSta & Num=  ,98.58, 2 ,121.24, 2 , 0 , 0 , 0 ,,
    2.59    2.59
      -5      20
    2.59    2.59
      -5      20
Pier Skew, UpSta & Num, DnSta & Num=  ,149.66, 2 ,172.34, 2 , 0 , 0 , 0 ,,
    2.76    2.76
      -5      20
    2.76    2.76
      -5      20
Pier Skew, UpSta & Num, DnSta & Num=  ,200.99, 2 ,223.47, 2 , 0 , 0 , 0 ,,
    2.49    2.49
      -5      20
    2.49    2.49
      -5      20
Pier Skew, UpSta & Num, DnSta & Num=  ,251.54, 2 ,274.63, 2 , 0 , 0 , 0 ,,
    2.88    2.88
      -5      20
    2.88    2.88
      -5      20
Pier Skew, UpSta & Num, DnSta & Num=  ,302.68, 2 ,325.54, 2 , 0 , 0 , 0 ,,
    2.56    2.56
      -5      20
    2.56    2.56
      -5      20
Pier Skew, UpSta & Num, DnSta & Num=  ,353.48, 2 ,376.5, 2 , 0 , 0 , 0 ,,
    2.72    2.72
      -5      20
    2.72    2.72
      -5      20
Pier Skew, UpSta & Num, DnSta & Num=  ,404.98, 2 ,427.78, 2 , 0 , 0 , 0 ,,
    2.97    2.97
      -5      20
    2.97    2.97
      -5      20
Pier Skew, UpSta & Num, DnSta & Num=  ,455.88, 2 ,478.66, 2 , 0 , 0 , 0 ,,
     2.7     2.7
      -5      20
     2.7     2.7
      -5      20
Pier Skew, UpSta & Num, DnSta & Num=  ,506.88, 2 ,529.66, 2 , 0 , 0 , 0 ,,
    2.41    2.41
      -5      20
    2.41    2.41
      -5      20
BR Coef=-1 , 0 , 0 ,, 0 ,,,0.8,-1,,0,
WSPro=,,,, 1 ,,,, 0 ,,,, 0 ,,,,-1 ,-1 ,-1 , 0 , 0 , 0 , 0 , 0
BR U #Sta/Elev= 44
       0   17.26   12.98   12.39   27.84    8.14   48.09    7.78   69.88     7.9
   91.84    7.83  112.66     7.9  135.55     7.9  156.96    7.81  178.43    7.65
     199    7.69  203.01    7.17   207.4    6.39  211.42    5.77  218.91     2.7
  229.06    2.75  243.78    1.06  262.24     .89  278.06       0   291.9    -.65
  304.49    -.04  318.13    1.89  327.16    1.97  344.52    2.07  357.51    2.42
  374.28     1.7  385.06     .05  400.25    -.24  412.27    1.12  425.87    5.45
  427.42    6.37   432.1    7.01  437.69    7.74  457.24    7.43  476.77    7.13
   498.1    7.04  517.84    7.12  536.57    7.77  552.12    11.2  564.22   18.16
  574.11   22.41  588.18   23.35  609.46   23.25  633.37   23.11
BR U #Mann= 4
       0     .95   27.84    .035     199      .2  437.69    .035
BR U Banks=199,437.69
BR D #Sta/Elev= 49
       0   10.35      21    9.08   41.65     8.4   64.58    7.75   85.98    7.97
  106.38    8.07  125.87    8.33   145.7    8.71  168.11    9.27  192.29   10.09
  210.25    8.74  220.12    7.59  227.57     7.1  236.37    6.38  238.32     6.1
   245.7    4.92   254.2    2.68  263.47     .67  275.36     .81  288.97     .94
  304.74    1.89  322.23    3.58  341.07    4.31  362.87     3.7  363.01    3.72
  382.62    3.52  394.53    2.25  403.96      .8  419.02     .97  428.68    3.53
   440.6    6.16  441.37    6.38  448.17    6.98  459.02     7.5  475.81    8.31
  492.99    8.37  512.85    8.63  533.41    8.87  552.15    8.66  564.21    8.81
   573.9   10.85  583.12   13.93  589.65   18.13  596.63    22.1  607.62   23.11
  623.77   22.89  642.57   22.72   660.5   22.75  679.02    22.8
BR D #Mann= 3
       0      .5  210.25      .2  475.81     .95
BR D Banks=192.29,475.81
BC Design=,, 0 ,, 0 ,,,,,,
BC HTab HWMax=16.66
BC Use User HTab Curves=0
BC User HTab FreeFlow(D)= 0

Type RM Length L Ch R = 1 ,318.19  ,16.1745,16.1745,16.1745
BEGIN DESCRIPTION:
MFL_SR46A
END DESCRIPTION:
Node Name=MFL_SR46A
XS GIS Cut Line= 3
 458972.715004883187593.78647002459149.7894048793187585.95147002
459323.6393266723187578.25914331
#Sta/Elev= 30
       0   10.35      52    7.63      87    8.22     157    8.48     167    9.15
     184     9.3     207     8.9     227    7.42     247    4.76     257    2.16
     267     .76     286     .36     307    1.46     327    3.36     357    4.56
     377    3.76     387    1.96     397    1.16     417    1.16     427    2.71
     439    5.66     448    7.05  486.94    8.24     557    8.28  564.21    8.81
   573.9   10.85  583.12   13.93  596.63    22.1  607.62   23.11  679.02    22.8
#Mann= 3 , 0 , 0
       0     .22       0     184      .2       0  486.94     .22       0
Bank Sta=184,486.94
XS Rating Curve= 0 ,0
Exp/Cntr=0.5,0.3

Type RM Length L Ch R = 1 ,318.03  ,78.5761,78.5761,78.5761
BEGIN DESCRIPTION:
XS9
END DESCRIPTION:
Node Name=XS9
XS GIS Cut Line= 2
 458968.757504883187600.67747002459170.9561048793187586.74517002
#Sta/Elev= 30
       0   10.35      21    9.08   64.58    7.75  125.87    8.33  192.29   10.09
  236.37    6.38   245.7    4.92   254.2    2.68  263.47     .67  288.97     .94
  304.74    1.89  322.23    3.58  341.07    4.31  382.62    3.52  394.53    2.25
  403.96      .8  419.02     .97  428.68    3.53  441.37    6.38  448.17    6.98
  475.81    8.31  533.41    8.87  564.21    8.81   573.9   10.85  583.12   13.93
  589.65   18.13  596.63    22.1  607.62   23.11  642.57   22.72  679.02    22.8
#Mann= 3 , 0 , 0
       0     .22       0  192.29      .2       0  475.81     .22       0
Bank Sta=192.29,475.81
XS Rating Curve= 0 ,0
Exp/Cntr=0.5,0.3

Type RM Length L Ch R = 1 ,317.25  ,143.1102,143.1102,143.1102
BEGIN DESCRIPTION:
MFL_SR46F
END DESCRIPTION:
Node Name=MFL_SR46F
#Sta/Elev= 30
 -150.52    14.3   20.95     7.8  190.85    5.86  226.96    6.78     406    6.63
     417    5.04     422    3.54     427     .04     442   -3.66     447   -3.66
     452   -1.76     462    -.56     472    -.76     487     .74     507    4.64
     517    5.64     522    7.45     577    7.25     582    5.34     592    2.94
     607     .44     632    1.74     672    6.64   716.2     7.1  717.87    7.98
   763.1    6.66  817.89    7.07  878.48    9.23   897.8   10.27  905.78   11.67
#Mann= 3 , 0 , 0
 -150.52     .22       0     406      .2       0     522     .22       0
#XS Ineff= 1 ,-1
  157.53  206.53    6.67
Permanent Ineff=
       F
Bank Sta=406,522
XS Rating Curve= 0 ,0
Exp/Cntr=0.3,0.1

Type RM Length L Ch R = 1 ,315.81  ,997.3753,997.3753,997.3753
BEGIN DESCRIPTION:
XS8
XS8
END DESCRIPTION:
Node Name=XS8
XS GIS Cut Line= 2
 458917.374004883187636.49117002 459187.742604883187689.83957002
#Sta/Elev= 30
 -150.52    14.3       0    8.29   63.91    7.24  157.53    6.69  190.85    5.86
  206.53    6.67  325.03    6.67  365.22    7.06     366    7.63  421.89    -.44
  450.99     .06  477.02    2.51  490.39     5.5  494.86    7.36  527.01    6.67
  585.88    6.73  594.18    8.08  608.44    6.77   621.6    2.26  633.11    1.05
  673.47     2.5   684.5    2.05  698.82    3.28   716.2     7.1  717.87    7.98
  748.38    6.81   798.6    6.66  878.48    9.23   897.8   10.27  905.78   11.67
#Mann= 3 , 0 , 0
 -150.52     .22       0     366      .2       0  494.86     .22       0
#XS Ineff= 1 ,-1
  157.53  206.53    6.67
Permanent Ineff=
       F
Bank Sta=366,494.86
XS Rating Curve= 0 ,0
Exp/Cntr=0.3,0.1

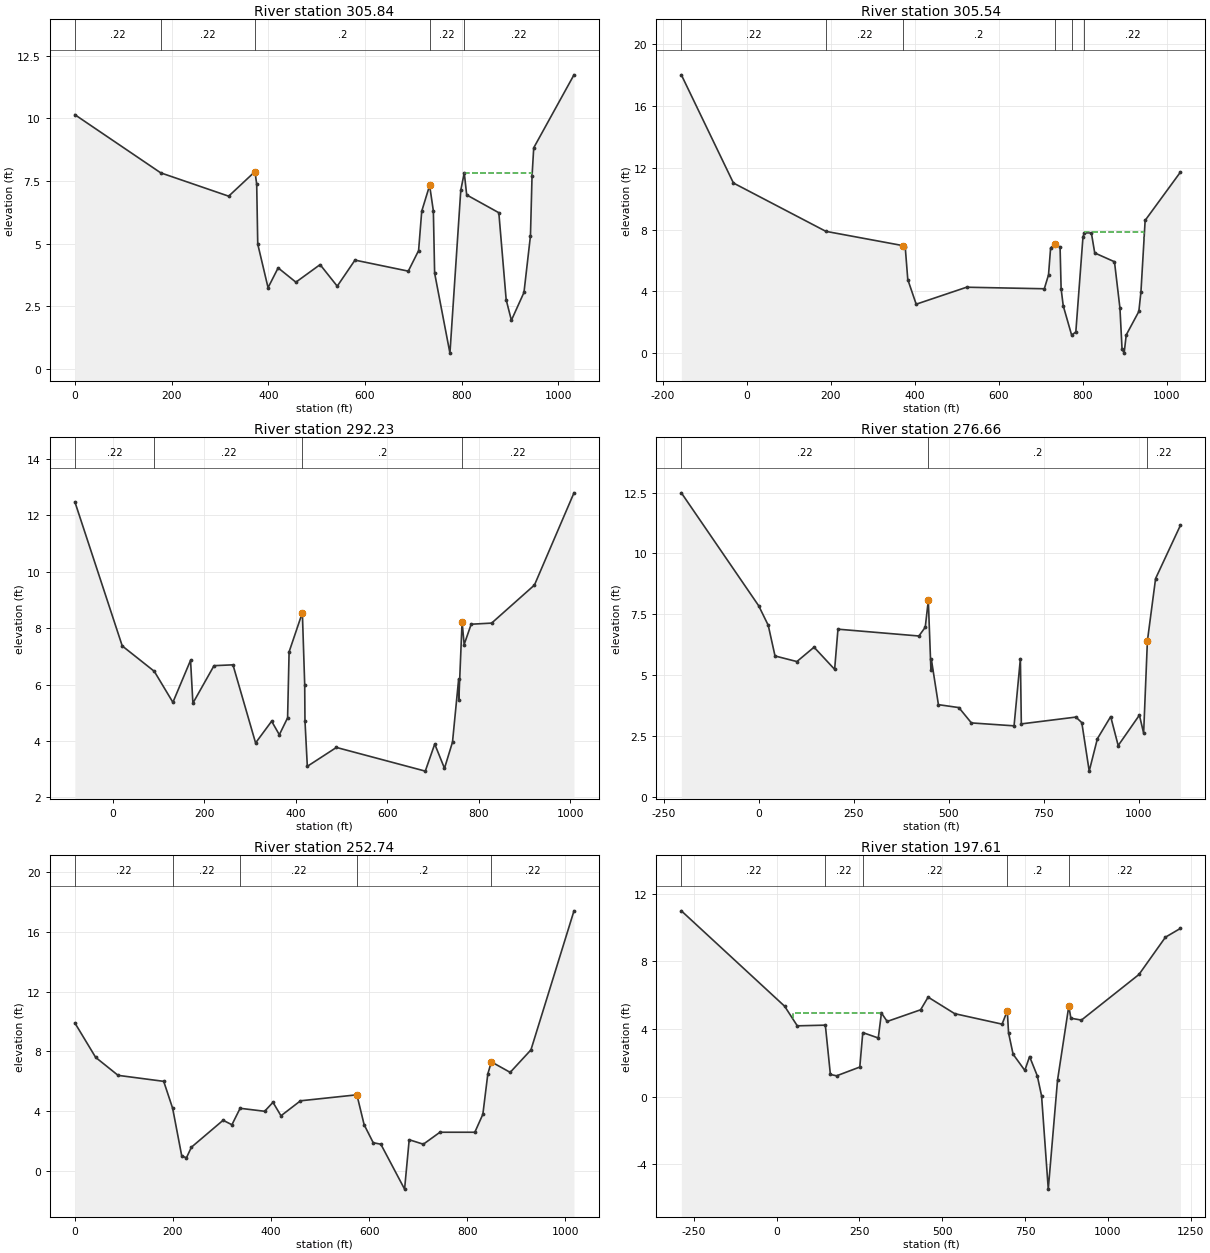
Type RM Length L Ch R = 1 ,305.84  ,30.4134,30.4134,30.4134
BEGIN DESCRIPTION:
XS7
END DESCRIPTION:
Node Name=XS7
XS GIS Cut Line= 2
458912.9379048793188032.57667002 459199.229404883187905.09737002
#Sta/Elev= 30
       0   10.14  177.56    7.82  318.03    6.89  372.37    7.87  375.96    7.37
  378.14    4.98  399.46    3.24  420.29    4.03     457    3.46  507.07    4.16
   542.5     3.3  579.19    4.34  689.43     3.9  710.74    4.72  717.21    6.29
  733.55    7.32  741.28     6.3  743.89    3.82  775.54     .63  797.98    7.13
  805.16    7.82  810.18    6.94  876.64    6.23  891.82    2.76  902.61    1.94
  928.63    3.05  942.04    5.31  945.29    7.68  948.81    8.82 1032.06   11.73
#Mann= 5 , 0 , 0
       0     .22       0  177.56     .22       0  372.37      .2       0
  733.55     .22       0  805.16     .22       0
#XS Ineff= 1 ,-1
  805.16  945.29    7.82
Permanent Ineff=
       F
Bank Sta=372.37,733.55
XS Rating Curve= 0 ,0
Exp/Cntr=0.3,0.1

Type RM Length L Ch R = 1 ,305.54  ,1330.971,1330.971,1330.971
BEGIN DESCRIPTION:
MFL_Maple
END DESCRIPTION:
Node Name=MFL_Maple
XS GIS Cut Line= 4
458874.819588939 3188076.6633844 459012.990904883188004.24317002
459034.858588939 3187992.7815844459109.3117230033187953.75820322
#Sta/Elev= 30
    -156   18.03     -32   11.02     188    7.89  372.37    6.96     377    6.85
     383    4.77     403    3.17     523    4.27     708    4.17     718    5.07
     723    6.82  733.55    7.05   745.5    6.87     748    4.17     753    3.07
     773    1.17     783    1.37     800    7.52     803    7.79     820    7.79
     828    6.49     875    5.92     888    2.92     893     .27     898       0
     903    1.18     933     2.7     938    3.97     948     8.6 1032.06   11.73
#Mann= 6 , 0 , 0
    -156     .22       0     188     .22       0  372.37      .2       0
  733.55     .22       0     773     .22       0     803     .22       0
#XS Ineff= 1 ,-1
  805.16  945.29    7.82
Permanent Ineff=
       F
Bank Sta=372.37,733.55
XS Rating Curve= 0 ,0
Exp/Cntr=0.3,0.1

Type RM Length L Ch R = 1 ,292.23  ,1556.693,1556.693,1556.693
BEGIN DESCRIPTION:
XS6
END DESCRIPTION:
Node Name=XS6
XS GIS Cut Line= 2
 459066.962404883188398.80067002 459329.354904883188309.45017002
#Sta/Elev= 30
  -82.59   12.48   20.95    7.37   90.95    6.47  131.64    5.37  170.22    6.86
  175.34    5.34  221.51    6.67  262.91     6.7  312.35    3.93  347.42     4.7
  364.26    4.22  382.29    4.82  385.58    7.16  414.57    8.55  419.68       6
  420.26    4.72  425.41     3.1  488.98    3.77  683.22    2.93  703.84    3.89
  725.17    3.03  742.68    3.96  756.14     6.2  756.48    5.44  763.62    8.22
  768.16    7.42  783.48    8.14  828.24    8.18   921.8    9.53 1008.19    12.8
#Mann= 4 , 0 , 0
  -82.59     .22       0   90.95     .22       0  414.57      .2       0
  763.62     .22       0
Bank Sta=414.57,763.62
XS Rating Curve= 0 ,0
Exp/Cntr=0.3,0.1

Type RM Length L Ch R = 1 ,276.66  ,2392.52,2392.52,2392.52
BEGIN DESCRIPTION:
XS5
END DESCRIPTION:
Node Name=XS5
XS GIS Cut Line= 2
459206.6051048793188905.35087002 459496.043504883188734.50867002
#Sta/Elev= 30
 -203.47   12.49       0    7.85   25.07    7.05   42.91    5.79  100.41    5.56
  145.54    6.15   199.7    5.24  208.46    6.89  421.34    6.61  438.02    6.97
  446.08    8.07  452.93    5.22  453.93    5.67  472.65    3.79   526.4    3.67
   559.4    3.04  671.59    2.92  688.24    5.68  690.71       3  834.22    3.28
   849.8    3.05  869.25    1.06  890.73    2.39  925.72     3.3  945.46    2.11
 1001.21    3.36 1012.38    2.62 1022.29    6.41 1043.84    8.97 1109.23   11.16
#Mann= 3 , 0 , 0
 -203.47     .22       0  446.08      .2       0 1022.29     .22       0
Bank Sta=446.08,1022.29
XS Rating Curve= 0 ,0
Exp/Cntr=0.3,0.1

Type RM Length L Ch R = 1 ,252.74  ,5512.566,5512.566,5512.566
BEGIN DESCRIPTION:
XS4
END DESCRIPTION:
Node Name=XS4
XS GIS Cut Line= 2
 459796.085804883189458.56807002459959.3749048793189243.81887002
#Sta/Elev= 30
       0     9.9   42.39     7.6   88.08     6.4  181.08       6  199.29     4.2
  217.94       1  227.49      .9  237.53     1.6  302.16     3.4  320.12     3.1
  336.83     4.2  386.81       4  403.81     4.6  420.13     3.7  459.91     4.7
  574.87     5.1  589.66     3.1  608.16     1.9   623.7     1.8  672.08    -1.2
  681.48     2.1  710.32     1.8  744.17     2.6  815.27     2.6  831.64     3.8
  841.78     6.5  848.97     7.3  887.35     6.6  929.63     8.1 1017.41   17.39
#Mann= 5 , 0 , 0
       0     .22       0  199.29     .22       0  336.83     .22       0
  574.87      .2       0  848.97     .22       0
Bank Sta=574.87,848.97
XS Rating Curve= 0 ,0
Exp/Cntr=0.3,0.1

Type RM Length L Ch R = 1 ,197.61  ,5438.025,5438.025,5438.025
BEGIN DESCRIPTION:
XS3
END DESCRIPTION:
Node Name=XS3
XS GIS Cut Line= 2
460829.9461048793190407.87167002 461055.296404883190115.14967002
#Sta/Elev= 30
 -287.57      11   24.29    5.35   62.45    4.19  147.14    4.23  162.34    1.31
  181.07    1.23  251.16    1.75  260.17    3.79  306.92    3.47  316.45    4.95
  333.84    4.45  434.75    5.14  457.35    5.89  537.66    4.91  680.61    4.29
  696.41    5.08  700.12    3.78  713.88    2.51  749.25    1.55  763.67    2.37
  786.91    1.23  799.86     .04  820.09   -5.48  848.03     .97  882.09    5.36
   888.3    4.64   920.2    4.53 1093.85    7.23 1173.86    9.44 1219.12    9.96
#Mann= 5 , 0 , 0
 -287.57     .22       0  147.14     .22       0  260.17     .22       0
  696.41      .2       0  882.09     .22       0
#XS Ineff= 1 ,-1
   48.35  316.45    4.95
Permanent Ineff=
       T
Bank Sta=696.41,882.09
XS Rating Curve= 0 ,0
Exp/Cntr=0.3,0.1

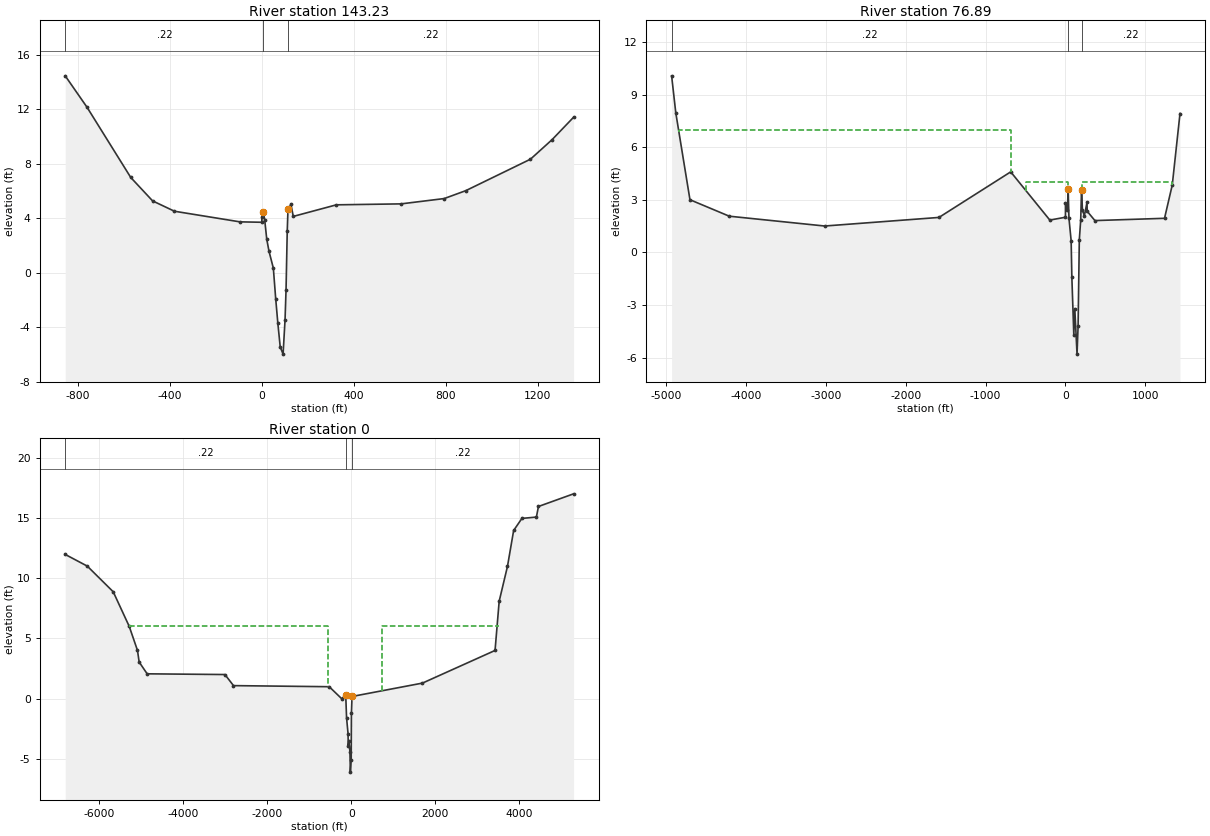
Type RM Length L Ch R = 1 ,143.23  ,6633.826,6633.826,6633.826
BEGIN DESCRIPTION:
XS2
END DESCRIPTION:
Node Name=XS2
XS GIS Cut Line= 2
461765.1722048793191043.89447002461806.0515048793191038.38137002
#Sta/Elev= 30
 -855.27   14.47 -760.24   12.16 -570.18    7.01 -475.15    5.29 -380.12    4.53
  -95.03    3.75       0    3.72     .19    4.13       7    4.48   12.81    3.86
   21.53    2.47    31.3    1.59    50.2     .35   60.36   -1.88   69.85   -3.71
   80.05   -5.43   92.54   -5.96  101.09   -3.44  105.43   -1.23  110.62    3.06
   113.9    4.68   126.9    5.03  136.82    4.15  324.44       5  605.87    5.07
  793.49    5.46   887.3    6.04 1168.73    8.35 1262.54    9.78 1356.34   11.43
#Mann= 3 , 0 , 0
 -855.27     .22       0       7      .2       0   113.9     .22       0
#XS Ineff= 1 ,-1
 -380.12       7    4.48
Permanent Ineff=
       T
Bank Sta=7,113.9
XS Rating Curve= 0 ,0
Exp/Cntr=0.3,0.1

Type RM Length L Ch R = 1 ,76.89   ,2563,2563,2563
BEGIN DESCRIPTION:
XS1
END DESCRIPTION:
Node Name=XS1
XS GIS Cut Line= 2
 462803.448104883191969.26997002 462859.554904883191908.91657002
#Sta/Elev= 30
-4928.99   10.08 -4876.5    7.96-4699.35    3.01-4207.28    2.07 -3013.2    1.51
-1582.93       2 -684.97     4.6 -195.71    1.85       0    2.01     .13     2.8
   24.53    2.41   33.99    3.61   43.96    1.95   71.39     .67   80.11   -1.39
  104.67   -4.69  117.04    -3.2  145.01    -5.8  158.26   -4.21  173.58     .72
  191.04    1.85  201.37    3.56  212.86    2.42  236.92     2.1  270.18    2.86
  272.17    2.35  368.96    1.82 1240.11    1.95 1336.91    3.85  1433.7    7.93
#Mann= 3 , 0 , 0
-4928.99     .22       0   33.99      .2       0  201.37     .22       0
#XS Ineff= 3 ,-1
-4837.13 -684.97       7 -489.26   33.99       4  201.37 1336.91       4
Permanent Ineff=
       F       F       F
Bank Sta=33.99,201.37
XS Rating Curve= 0 ,0
Exp/Cntr=0.3,0.1

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
Type RM Length L Ch R = 1 ,0       ,7.0538,7.0538,7.0538
BEGIN DESCRIPTION:
LoWek
END DESCRIPTION:
Node Name=LoWek
XS GIS Cut Line= 2
  463445.2442725 3193619.5738227  463552.4459684 3193623.8064514
#Sta/Elev= 30
   -6800   11.97-6275.23      11-5658.62    8.87-5278.16       6-5081.38       4
-5042.02    3.04-4851.79    2.06-3001.98       2-2798.63    1.08 -522.45     .99
 -227.26       0    -130     .31    -110    -1.6     -75    -2.9     -70    -3.9
     -55   -3.55     -30    -4.4     -20    -6.1       0    -5.1       5   -1.22
      20     .18  1694.7    1.29  3420.4       4 3518.69    8.09 3715.27   10.97
 3862.71   13.96 4059.28   14.96  4403.3   15.07 4452.44   15.95  5287.9      17
#Mann= 3 , 0 , 0
   -6800     .22       0    -130      .2       0      20     .22       0
#XS Ineff= 2 ,-1
 -5284.8  -561.8       6  743.56 3518.69       6
Permanent Ineff=
       F       F
Bank Sta=-130,20
XS Rating Curve= 0 ,0
Exp/Cntr=0.3,0.1
Stream Node=LtWekiva        ,LtWekiva        , 0 , 0 ,Upstream end
Stream Node=LtWekiva        ,LtWekiva        , 0 , 1 ,Downstream end
Stream Node=ROK             ,ROK             , 0 , 0 ,Upstream end
Stream Node=ROK             ,ROK             , 0 , 1 ,Downstream end
Stream Node=wekiva          ,wek_run         , 0 , 0 ,Upstream end
Stream Node=wekiva          ,wek_run         , 0 , 1 ,Downstream end
Stream Node=wekiva          ,wekiva_riv_up   , 0 , 0 ,Upstream end
Stream Node=wekiva          ,wekiva_riv_up   , 0 , 1 ,Downstream end
Stream Node=wekiva          ,wekiva_riv_down , 0 , 0 ,Upstream end
Stream Node=wekiva          ,wekiva_riv_down , 0 , 1 ,Downstream end
LCMann Table=0

Chan Stop Cuts=-1
Use User Specified Reach Order=0
Roughness Change=ROK             ,ROK             ,160.48  ,18.07   , 5
      50       1      60     .85      75      .7     120      .6     420      .5
Roughness Change=wekiva          ,wekiva_riv_down ,544.57  ,0       , 5
     140       1     200      .8     400     .65     700    .575    2000      .5
Roughness Change=ROK             ,ROK             ,396.13  ,350.27  , 2
      46       1     120      .5
Roughness Change=LtWekiva        ,LtWekiva        ,107.56* ,30.50   , 5
      30       1      50    .773      70    .636     140    .545    1020    .455
Roughness Change=LtWekiva        ,LtWekiva        ,143.98  ,143.98  , 5
      30       1      48    .773      70    .636     120    .545     640    .455
Roughness Change=wekiva          ,wekiva_riv_up   ,678.62  ,579.64  , 5
      90       1     120      .8     200     .75     300     .65    1000      .5
Roughness Change=wekiva          ,wekiva_riv_up   ,747.29  ,711.81  , 5
      90       1     120      .8     200     .75     300     .65    1000      .5
Roughness Change=wekiva          ,wek_run         ,785.19  ,779.51  , 5
      50       1      60      .8      80     .75     100     .65     500      .5
Composite Channel Slope=5

--- wekiva_ras.g06 (geometry) ---

Geom Title=wekiva_ras_2018_ft_10
Program Version=5.03

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
Junct Name=Junc_Rok
Junct Desc=, 0 , 0 ,-1 ,0
Up River,Reach=ROK             ,ROK
Up River,Reach=wekiva          ,wek_run
Dn River,Reach=wekiva          ,wekiva_riv_up
Junc L&A=0,0
Junc L&A=0,0

River Reach=LtWekiva        ,LtWekiva

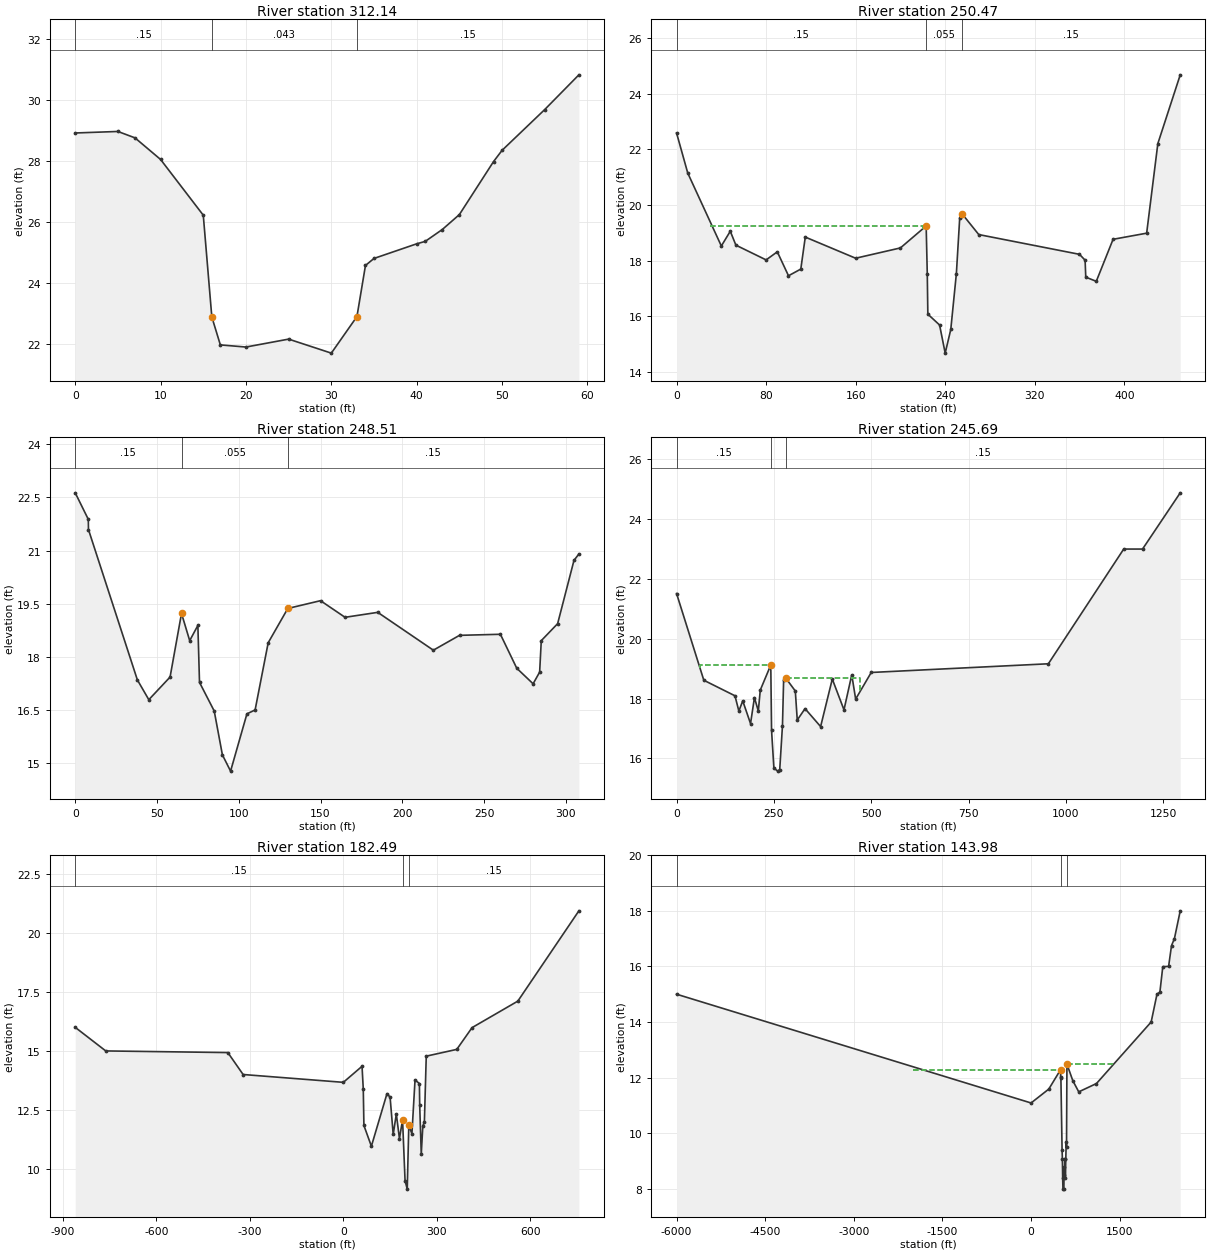
Type RM Length L Ch R = 1 ,312.14  ,6167.191,6167.191,6167.191
BEGIN DESCRIPTION:
TheSprings
END DESCRIPTION:
Node Name=TheSprings
XS GIS Cut Line= 2
461204.5570048793173492.65727002461225.0887048793173489.69387002
#Sta/Elev= 21
       0   28.92       5   28.97       7   28.76      10   28.05      15   26.22
      16   22.88      17   21.96      20   21.89      25   22.15      30   21.69
      33   22.89      34   24.57      35    24.8      40   25.28      41   25.36
      43   25.75      45   26.24      49   27.98      50   28.35      55   29.69
      59   30.83
#Mann= 3 , 0 , 0
       0     .15       0      16    .043       0      33     .15       0
Bank Sta=16,33
XS Rating Curve= 0 ,0
Exp/Cntr=0.3,0.1

Type RM Length L Ch R = 1 ,250.47  ,195.8661,195.8661,195.8661
BEGIN DESCRIPTION:
MFL_SLB_south
END DESCRIPTION:
Node Name=MFL_SLB_south
XS GIS Cut Line= 2
 461695.722804883174963.91247002461744.7818048793175039.17377002
#Sta/Elev= 30
       0  22.582      10  21.142      40  18.522      48  19.052      53  18.552
      80  18.022      90  18.312     100  17.452     111  17.692     115  18.842
     160  18.082     200  18.452     223  19.242     224  17.512   224.5  16.072
     235  15.682     240  14.672     245  15.522     250  17.532     253  19.542
     255  19.682     270  18.932     360  18.222     365  18.012   365.6  17.402
     375  17.252     390  18.762     420  18.982     430  22.202     450  24.672
#Mann= 3 , 0 , 0
       0     .15       0     223    .055       0     255     .15       0
#XS Ineff= 2 ,-1
      30     220   19.24     255     425   19.68
Permanent Ineff=
       F       F
Bank Sta=223,255
XS Rating Curve= 0 ,0
Exp/Cntr=0.3,0.1

Type RM Length L Ch R = 1 ,248.51  ,282.3819,282.3819,282.3819
BEGIN DESCRIPTION:
MFL_SLB_bridge
END DESCRIPTION:
Node Name=MFL_SLB_bridge
XS GIS Cut Line= 2
461657.0487048793175034.72957002461736.0472048793175081.44547002
#Sta/Elev= 30
       0  22.632       8  21.882     8.1  21.592      38  17.342      45  16.782
      58  17.422      65  19.222      70  18.452      75  18.882      76  17.272
      85  16.462      90  15.222      95  14.762     105  16.382     110  16.492
     118  18.392     130  19.362     150  19.582     165  19.112     185  19.252
     219  18.182     235  18.602     260  18.632     270  17.672     280  17.232
     284  17.562     285  18.452     295  18.932     305  20.722     308  20.902
#Mann= 3 , 0 , 0
       0     .15       0      65    .055       0     130     .15       0
#XS Ineff= 2 ,-1
      20      65   19.22     130     300   19.36
Permanent Ineff=
       F       F
Bank Sta=65,130
XS Rating Curve= 0 ,0
Exp/Cntr=0.3,0.1

Type RM Length L Ch R = 1 ,245.69  ,6319.948,6319.948,6319.948
BEGIN DESCRIPTION:
MFL_SLB_north
END DESCRIPTION:
Node Name=MFL_SLB_north
XS GIS Cut Line= 3
461616.7210048793175109.23877002 461714.682104883175129.98127002
462481.3654001193175292.32048682
#Sta/Elev= 30
       0  21.512      70  18.612     150  18.092     160  17.582     170  17.922
     190  17.162     200  18.032     210  17.582     215  18.282     242  19.122
     244  16.932     250  15.672     260  15.572     265  15.622     272  17.092
     275  18.622     280  18.692     305  18.252     310  17.282     330  17.662
     370  17.062     400  18.652     430  17.622     450  18.792     460  17.982
     500  18.872954.9455 19.16271148.509      23  1196.9      231293.682 24.8808
#Mann= 3 , 0 , 0
       0     .15       0     242    .055       0     280     .15       0
#XS Ineff= 2 ,-1
      60     242   19.12     280     470   18.69
Permanent Ineff=
       F       F
Bank Sta=242,280
XS Rating Curve= 0 ,0
Exp/Cntr=0.3,0.1

Type RM Length L Ch R = 1 ,182.49  ,3850.361,3850.361,3850.361
BEGIN DESCRIPTION:
MFL_Sabol
MFL_Sabol
END DESCRIPTION:
Node Name=MFL_Sabol
XS GIS Cut Line= 2
 460724.291904883176565.62067002 461198.426104883176557.15397002
#Sta/Elev= 30
-860.094      16-762.169      15-370.471 14.9302-321.509      14       0  13.668
      60  14.348      64  13.378      66  11.838      90  10.958     140  13.188
     150  13.038     160  11.458     170  12.328     180  11.278     190  12.078
     198   9.498     205   9.138     210  11.838     220  11.488     230  13.768
     244  13.618     245  12.688     250  10.618     255  11.818     260  11.988
     266  14.778363.9624 15.0659412.9247 15.9882559.8115 17.1129755.6606 20.9429
#Mann= 3 , 0 , 0
-860.094     .15       0     190    .055       0     210     .15       0
#XS Ineff= 1 ,-1
      64     120   12.08
Permanent Ineff=
       F
Bank Sta=190,210
XS Rating Curve= 0 ,0
Exp/Cntr=0.3,0.1

Type RM Length L Ch R = 1 ,143.98  ,3642.73,3642.73,3642.73
BEGIN DESCRIPTION:
LW2
END DESCRIPTION:
Node Name=LW2
XS GIS Cut Line= 2
 460933.299004883177665.03007002461212.6995048793177544.37987002
#Sta/Elev= 30
   -6000      15       0  11.086     300  11.586     500  12.286   501.5  12.006
     505  11.986     525   9.386     530   9.086     535   8.386     540   7.986
     555   7.986     560   8.786     565   8.486     570   9.086     575   9.086
     580   8.386     595   9.686     600   9.486     607  12.486     707  11.886
     807  11.486    1107  11.7862032.791      142131.163      152180.349  15.072
2229.535 15.99112327.908      162377.094 16.7483 2426.28      172524.652      18
#Mann= 3 , 0 , 0
   -6000       0       0     500       0       0     607       0       0
#XS Ineff= 2 ,-1
   -2000     500   12.29     607    1400   12.49
Permanent Ineff=
       F       F
Bank Sta=500,607
XS Rating Curve= 0 ,0
Vertical n Elevations= 5
      30      48      70     120     640
Vertical n for Station=-6000
     .22     .22     .22     .22     .22
Vertical n for Station=500
      .2     .17     .14     .12      .1
Vertical n for Station=607
     .22     .22     .22     .22     .22
Vertical n Flow=-1
Exp/Cntr=0.3,0.1

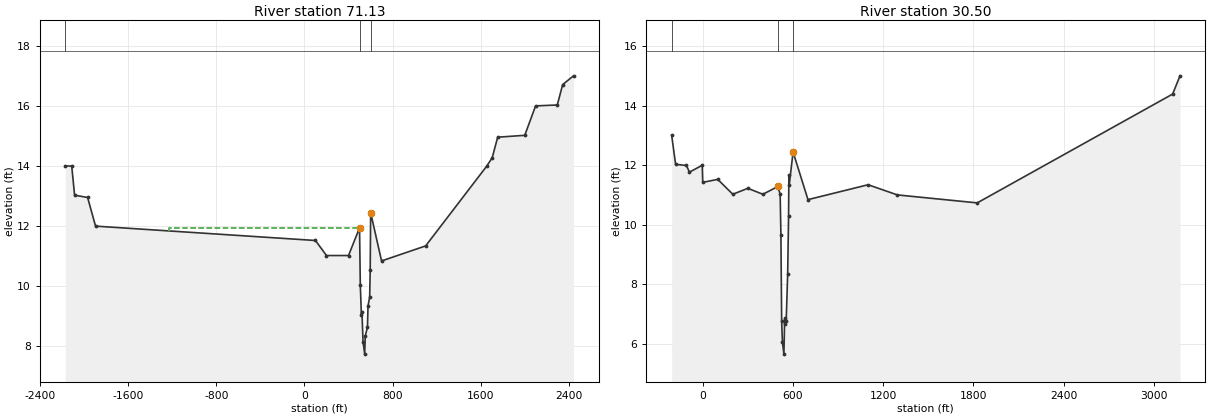
Type RM Length L Ch R = 1 ,71.13   ,4063.156,4063.156,4063.156
BEGIN DESCRIPTION:
LW1
END DESCRIPTION:
Node Name=LW1
XS GIS Cut Line= 2
460177.6475048793179246.18327002 460425.298004883179284.28337002
#Sta/Elev= 30
-2170.99      14-2111.97      14-2085.74 13.0294-1967.72 12.9532-1895.59      12
     100  11.522     200  11.022     400  11.022     500  11.942     507  10.042
     517   9.042     522   9.142     532   8.142     547   7.742     552   8.342
     572   8.642     577   9.342     592   9.642     597  10.542     601  12.442
     700  10.842    1100  11.3421655.207      141704.387 14.27811753.567 14.9583
1999.466 15.02082097.825      162294.545 16.02972343.725 16.70992442.084      17
#Mann= 3 , 0 , 0
-2170.99       0       0     500       0       0     601       0       0
#XS Ineff= 2 ,-1
-1226.79     500   11.94     601    1350   12.44
Permanent Ineff=
       F       F
Bank Sta=500,601
XS Rating Curve= 0 ,0
Vertical n Elevations= 5
      30      50      70     140    1020
Vertical n for Station=-2170.99
     .22     .22     .22     .22     .22
Vertical n for Station=500
      .2     .17     .14     .12      .1
Vertical n for Station=601
     .22     .22     .22     .22     .22
Vertical n Flow=-1
Exp/Cntr=0.3,0.1

Type RM Length L Ch R = 1 ,30.50   ,3049.836,3049.836,3049.836
BEGIN DESCRIPTION:
WK18
END DESCRIPTION:
Node Name=WK18
XS GIS Cut Line= 2
 459515.919704883180360.70577002 459987.937304883180315.19737002
#Sta/Elev= 30
 -206.62      13-180.390 12.0255-108.269 11.9891-88.6005  11.765-3.36730 11.9961
       0  11.422     100  11.522     200  11.022     300  11.222     400  11.022
     500  11.283     515  11.023     520   9.653     525   6.753     530   6.053
     540   5.653     545   6.853     550   6.653     555   6.753     565   8.353
     571  10.293     573  11.663     575  11.323     601  12.442     700  10.842
    1100  11.3421294.801      111825.869 10.7326 3125.62 14.38723174.641      15
#Mann= 3 , 0 , 0
 -206.62       0       0     500       0       0     601       0       0
#XS Ineff= 2 ,-1
     100     500   11.28     601    2450   12.44
Permanent Ineff=
       F       F
Bank Sta=500,601
XS Rating Curve= 0 ,0
Vertical n Elevations= 5
      30      50      70     140    1020
Vertical n for Station=-206.62
     .22     .22     .22     .22     .22
Vertical n for Station=500
      .2     .17     .14     .12      .1
Vertical n for Station=601
     .22     .22     .22     .22     .22
Vertical n Flow=-1
Exp/Cntr=0.3,0.1

River Reach=ROK             ,ROK

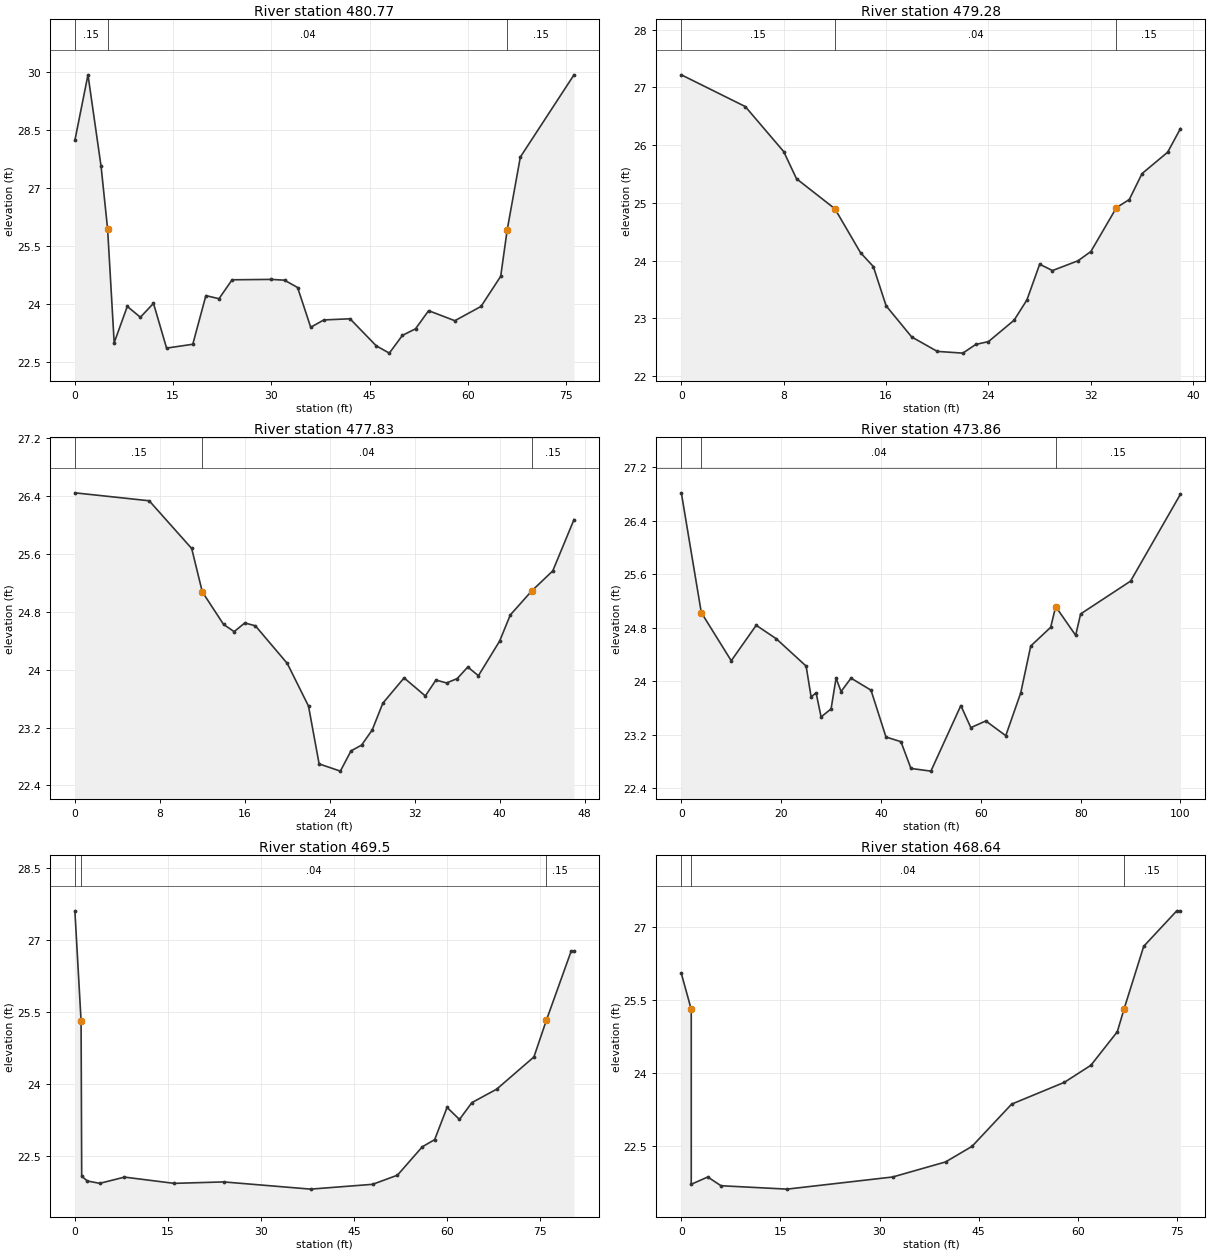
Type RM Length L Ch R = 1 ,480.77  ,149.0814,149.0814,149.0814
BEGIN DESCRIPTION:
RokSpr02
END DESCRIPTION:
Node Name=RokSpr02
XS GIS Cut Line= 2
451026.6781048793181095.07657002451022.5373048793181071.37427002
#Sta/Elev= 30
       0  28.228       2  29.928       4  27.558       5  25.928       6  22.988
       8  23.928      10  23.648      12  24.008      14  22.848      18  22.948
      20  24.208      22  24.128      24  24.618      30  24.628      32  24.608
      34  24.418      36  23.388      38  23.578      42  23.608      46  22.908
      48  22.718      50  23.178      52  23.348      54  23.818      58  23.558
      62  23.928      65  24.708      66  25.918      68  27.798   76.19  29.928
#Mann= 3 , 0 , 0
       0     .15       0       5     .04       0      66     .15       0
Bank Sta=5,66
XS Rating Curve= 0 ,0
Exp/Cntr=0.3,0.1

Type RM Length L Ch R = 1 ,479.28  ,145.1115,145.1115,145.1115
BEGIN DESCRIPTION:
RokSpr03
END DESCRIPTION:
Node Name=RokSpr03
XS GIS Cut Line= 2
451082.3677048793181066.28987002451051.4643048793181054.43647002
#Sta/Elev= 24
       0  27.218       5  26.668       8  25.888       9  25.418      12  24.898
      14  24.138      15  23.898      16  23.218      18  22.678      20  22.428
      22  22.398      23  22.548      24  22.598      26  22.968      27  23.318
      28  23.938      29  23.828      31  23.998      32  24.158      34  24.918
      35  25.058      36  25.508      38  25.878      39  26.288
#Mann= 3 , 0 , 0
       0     .15       0      12     .04       0      34     .15       0
Bank Sta=12,34
XS Rating Curve= 0 ,0
Exp/Cntr=0.3,0.1

Type RM Length L Ch R = 1 ,477.83  ,396.8176,396.8176,396.8176
BEGIN DESCRIPTION:
RokSpr04
END DESCRIPTION:
Node Name=RokSpr04
XS GIS Cut Line= 2
 451097.184404883181024.59137002 451068.609404883181013.79637002
#Sta/Elev= 28
       0  26.448       7  26.338      11  25.678      12  25.078      14  24.628
      15  24.528      16  24.648      17  24.608      20  24.088      22  23.498
      23  22.698      25  22.598      26  22.878      27  22.958      28  23.168
      29  23.538      31  23.888      33  23.638      34  23.858      35  23.818
      36  23.878      37  24.038      38  23.918      40  24.398      41  24.758
      43  25.088      45  25.368      47  26.078
#Mann= 3 , 0 , 0
       0     .15       0      12     .04       0      43     .15       0
Bank Sta=12,43
XS Rating Curve= 0 ,0
Exp/Cntr=0.3,0.1

Type RM Length L Ch R = 1 ,473.86  ,436.3189,436.3189,436.3189
BEGIN DESCRIPTION:
RokSpr05
END DESCRIPTION:
Node Name=RokSpr05
XS GIS Cut Line= 2
451175.4950048793180987.69237002451172.3109048793180957.39027002
#Sta/Elev= 30
       0  26.818       4  25.028      10  24.308      15  24.838      19  24.638
      25  24.228      26  23.768      27  23.828      28  23.468      30  23.588
      31  24.048      32  23.848      34  24.048      38  23.868      41  23.168
      44  23.098      46  22.698      50  22.658      56  23.638      58  23.308
      61  23.408      65  23.188      68  23.828      70  24.528      74  24.808
      75  25.118      79  24.688      80  25.008      90  25.498     100  26.798
#Mann= 3 , 0 , 0
       0     .15       0       4     .04       0      75     .15       0
Bank Sta=4,75
XS Rating Curve= 0 ,0
Exp/Cntr=0.3,0.1

Type RM Length L Ch R = 1 ,469.5   ,86.1877,86.1877,86.1877
BEGIN DESCRIPTION:
RokSpr08
END DESCRIPTION:
Node Name=RokSpr08
XS GIS Cut Line= 2
 451256.572004883181058.88917002451286.3376048793181034.67977002
#Sta/Elev= 21
       0  27.608       1  25.318     1.1  22.088       2  21.988       4  21.938
       8  22.068      16  21.938      24  21.968      38  21.818      48  21.918
      52  22.108      56  22.698      58  22.848      60  23.518      62  23.268
      64  23.618      68  23.898      74  24.568      76  25.328      80  26.768
   80.46  26.768
#Mann= 3 , 0 , 0
       0     .15       0       1     .04       0      76     .15       0
Bank Sta=1,76
XS Rating Curve= 0 ,0
Exp/Cntr=0.3,0.1

Type RM Length L Ch R = 1 ,468.64  ,242.6181,242.6181,242.6181
BEGIN DESCRIPTION:
RokSpr09
END DESCRIPTION:
Node Name=RokSpr09
XS GIS Cut Line= 2
 451276.415704883181079.12987002 451298.510204883181052.33677002
#Sta/Elev= 17
       0  26.048     1.5  25.308     1.5  21.708       4  21.858       6  21.678
      16  21.608      32  21.858      40  22.168      44  22.488      50  23.358
      58  23.808      62  24.158      66  24.848      67  25.308      70  26.608
      75  27.338   75.56  27.338
#Mann= 3 , 0 , 0
       0     .15       0     1.5     .04       0      67     .15       0
Bank Sta=1.5,67
XS Rating Curve= 0 ,0
Exp/Cntr=0.3,0.1