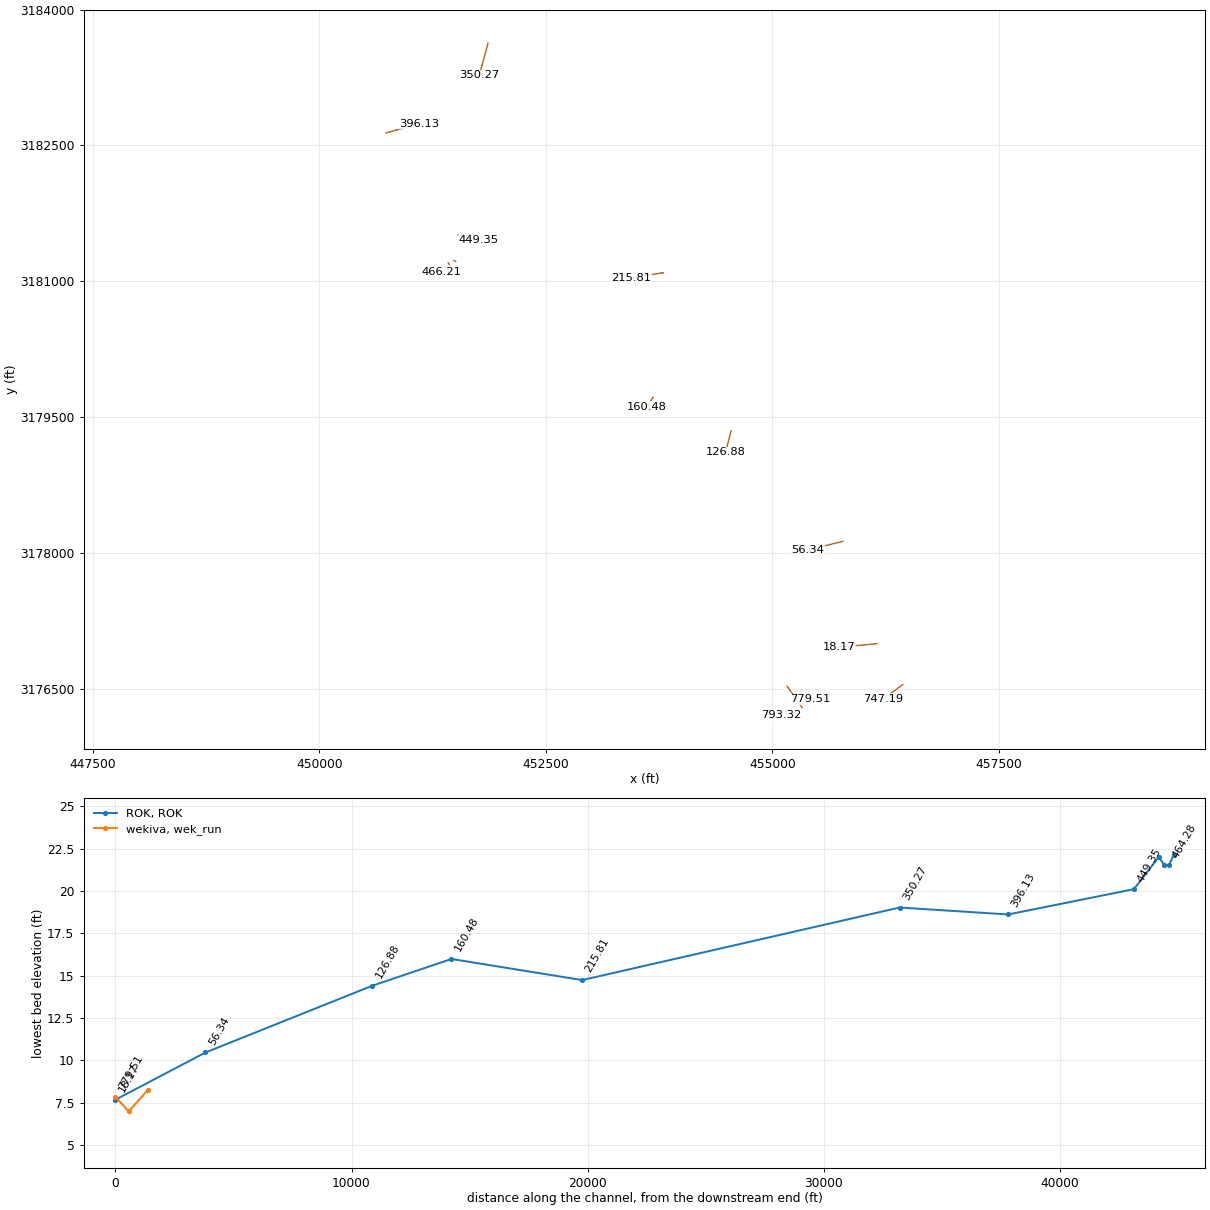
HEC-RAS study wekiva_ras.prj: wekiva_ras

--- wekiva_ras.g06 (geometry) --- (continued)

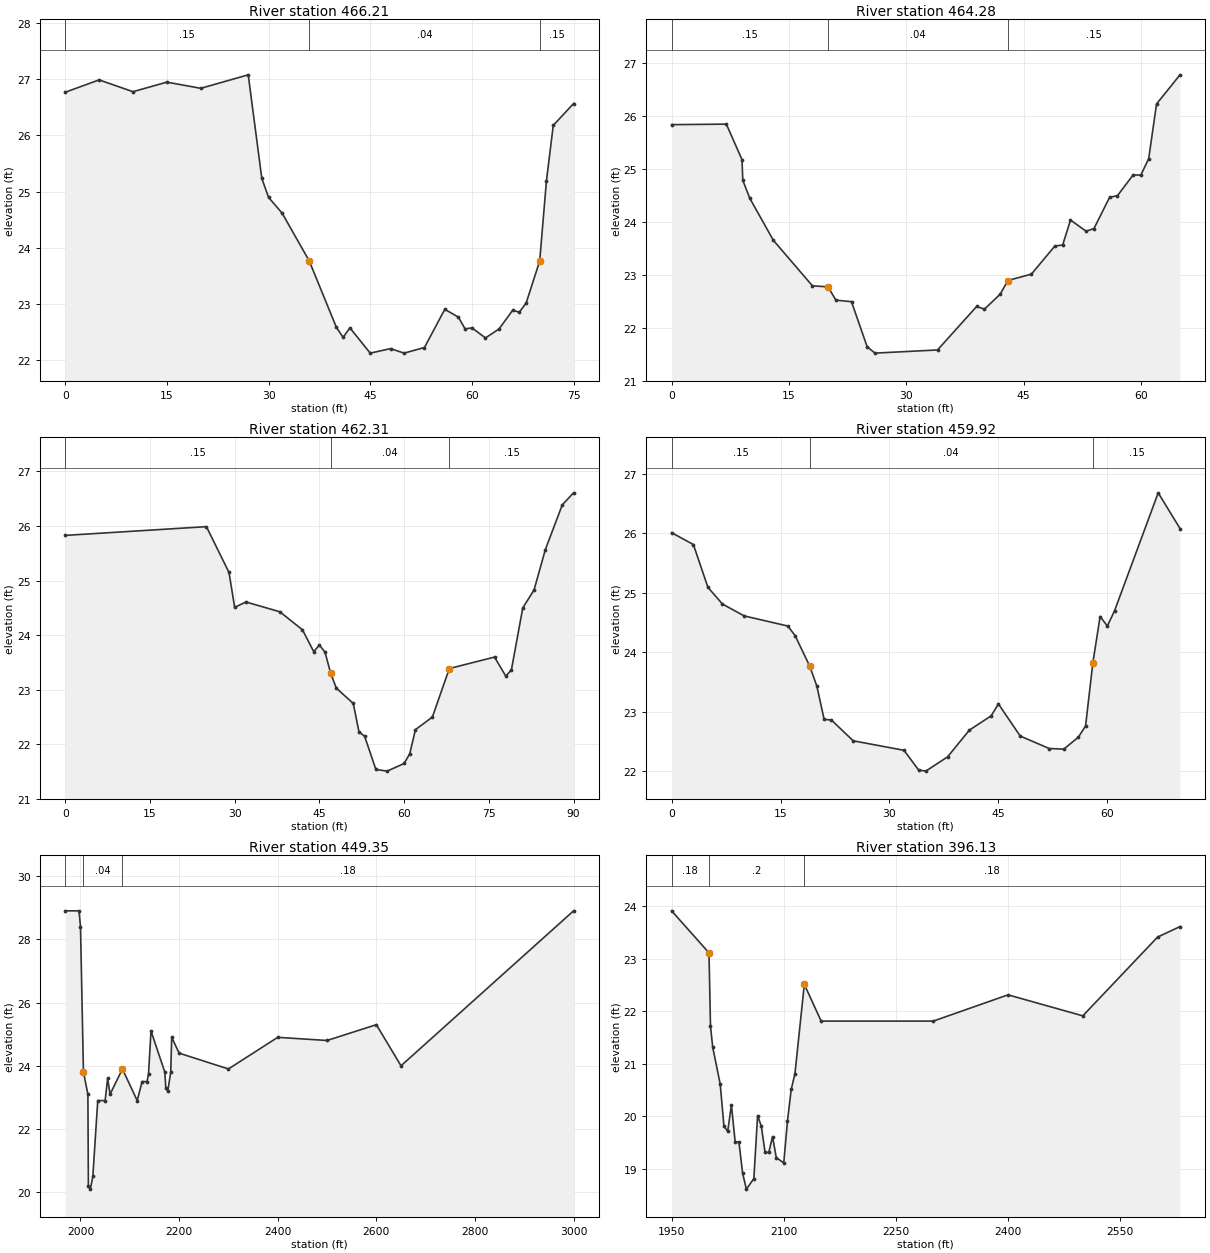
Type RM Length L Ch R = 1 ,466.21  ,193.2415,193.2415,193.2415
BEGIN DESCRIPTION:
RokSpr11
END DESCRIPTION:
Node Name=RokSpr11
XS GIS Cut Line= 2
451331.5027048793181121.98737002 451349.007504883181107.29797002
#Sta/Elev= 30
       0  26.768       5  26.988      10  26.778      15  26.948      20  26.838
      27  27.078      29  25.238      30  24.898      32  24.618      36  23.768
      40  22.588      41  22.408      42  22.578      45  22.128      48  22.208
      50  22.128      53  22.228      56  22.908      58  22.768      59  22.558
      60  22.578      62  22.398      64  22.558      66  22.888      67  22.858
      68  23.018      70  23.768      71  25.198      72  26.178      75  26.568
#Mann= 3 , 0 , 0
       0     .15       0      36     .04       0      70     .15       0
Bank Sta=36,70
XS Rating Curve= 0 ,0
Exp/Cntr=0.3,0.1

Type RM Length L Ch R = 1 ,464.28  ,196.4567,196.4567,196.4567
BEGIN DESCRIPTION:
RokSpr12
END DESCRIPTION:
Node Name=RokSpr12
XS GIS Cut Line= 2
 451376.887304883181161.36027002 451390.891104883181147.35337002
#Sta/Elev= 30
       0  25.828       7  25.838       9  25.168     9.1  24.778      10  24.438
      13  23.648      18  22.788      20  22.768      21  22.518      23  22.488
      25  21.638      26  21.518      34  21.578      39  22.398      40  22.348
      42  22.628      43  22.888      46  23.008      49  23.538      50  23.558
      51  24.028      53  23.818      54  23.868      56  24.458      57  24.488
      59  24.878      60  24.878      61  25.188      62  26.218      65  26.768
#Mann= 3 , 0 , 0
       0     .15       0      20     .04       0      43     .15       0
Bank Sta=20,43
XS Rating Curve= 0 ,0
Exp/Cntr=0.3,0.1

Type RM Length L Ch R = 1 ,462.31  ,239.5341,239.5341,239.5341
BEGIN DESCRIPTION:
RokSpr13
END DESCRIPTION:
Node Name=RokSpr13
XS GIS Cut Line= 2
451422.9117048793181205.33417002 451436.623104883181181.58607002
#Sta/Elev= 30
       0  25.828      25  25.988      29  25.148      30  24.508      32  24.608
      38  24.428      42  24.098      44  23.698      45  23.818      46  23.688
      47  23.298      48  23.028      51  22.748      52  22.228      53  22.148
      55  21.538      57  21.508      60  21.648      61  21.828      62  22.268
      65  22.498      68  23.388      76  23.598      78  23.248      79  23.368
      81  24.498      83  24.828      85  25.568      88  26.388      90  26.608
#Mann= 3 , 0 , 0
       0     .15       0      47     .04       0      68     .15       0
Bank Sta=47,68
XS Rating Curve= 0 ,0
Exp/Cntr=0.3,0.1

Type RM Length L Ch R = 1 ,459.92  ,1057.185,1057.185,1057.185
BEGIN DESCRIPTION:
RokSpr14
END DESCRIPTION:
Node Name=RokSpr14
XS GIS Cut Line= 2
451484.9297048793181229.40207002 451504.259604883181220.38617002
#Sta/Elev= 30
       0  26.008       3  25.808       5  25.088       7  24.808      10  24.608
      16  24.438      17  24.278      19  23.768      20  23.428      21  22.868
      22  22.858      25  22.508      32  22.348      34  22.018      35  21.998
      38  22.238      41  22.688      44  22.928      45  23.128      48  22.588
      52  22.378      54  22.368      56  22.568      57  22.758      58  23.818
      59  24.598      60  24.438      61  24.698      67  26.678      70  26.078
#Mann= 3 , 0 , 0
       0     .15       0      19     .04       0      58     .15       0
Bank Sta=19,58
XS Rating Curve= 0 ,0
Exp/Cntr=0.3,0.1

Type RM Length L Ch R = 1 ,449.35  ,5321.588,5321.588,5321.588
BEGIN DESCRIPTION:
ROK7
END DESCRIPTION:
Node Name=ROK7
XS GIS Cut Line= 2
 451531.470204883181508.48117002 451753.720604883181451.33097002
#Sta/Elev= 30
    1969    28.9    1997    28.9    2000    28.4    2006    23.8    2015    23.1
    2016    20.2    2020    20.1    2025    20.5    2035    22.9    2050    22.9
    2055    23.6    2060    23.1    2085    23.9    2115    22.9    2125    23.5
    2135    23.5    2138   23.75    2143    25.1    2171    23.8    2173    23.3
    2177    23.2    2183    23.8    2185    24.9    2200    24.4    2300    23.9
    2400    24.9    2500    24.8    2600    25.3    2650      24    3000    28.9
#Mann= 3 , 0 , 0
    1969     .18       0    2006     .04       0    2085     .18       0
Bank Sta=2006,2085
XS Rating Curve= 0 ,0
Exp/Cntr=0.3,0.1

Type RM Length L Ch R = 1 ,396.13  ,4586.122,4586.122,4586.122
BEGIN DESCRIPTION:
ROK6
END DESCRIPTION:
Node Name=ROK6
XS GIS Cut Line= 2
450737.7186048793182638.78337002451099.6693048793182740.38357002
#Sta/Elev= 30
    1950   23.91    2000   23.11    2002   21.71    2005   21.31    2015   20.61
    2020   19.81    2025   19.71    2030   20.21    2035   19.51    2040   19.51
    2045   18.91    2050   18.61    2060   18.81    2065   20.01    2070   19.81
    2075   19.31    2080   19.31    2085   19.61    2090   19.21    2100   19.11
    2105   19.91    2110   20.51    2115   20.81  2127.5   22.51    2150   21.81
    2300   21.81    2400   22.31    2500   21.91    2600   23.41    2630   23.61
#Mann= 3 , 0 , 0
    1950     .18       0    2000      .2       0  2127.5     .18       0
Bank Sta=2000,2127.5
XS Rating Curve= 0 ,0
Vertical n Elevations= 5
      46      49      51      54     120
Vertical n for Station=1950
     .22     .22     .22     .22     .22
Vertical n for Station=2000
      .2     .17     .14     .12      .1
Vertical n for Station=2127.5
     .22     .22     .22     .22     .22
Vertical n Flow=-1
Exp/Cntr=0.3,0.1

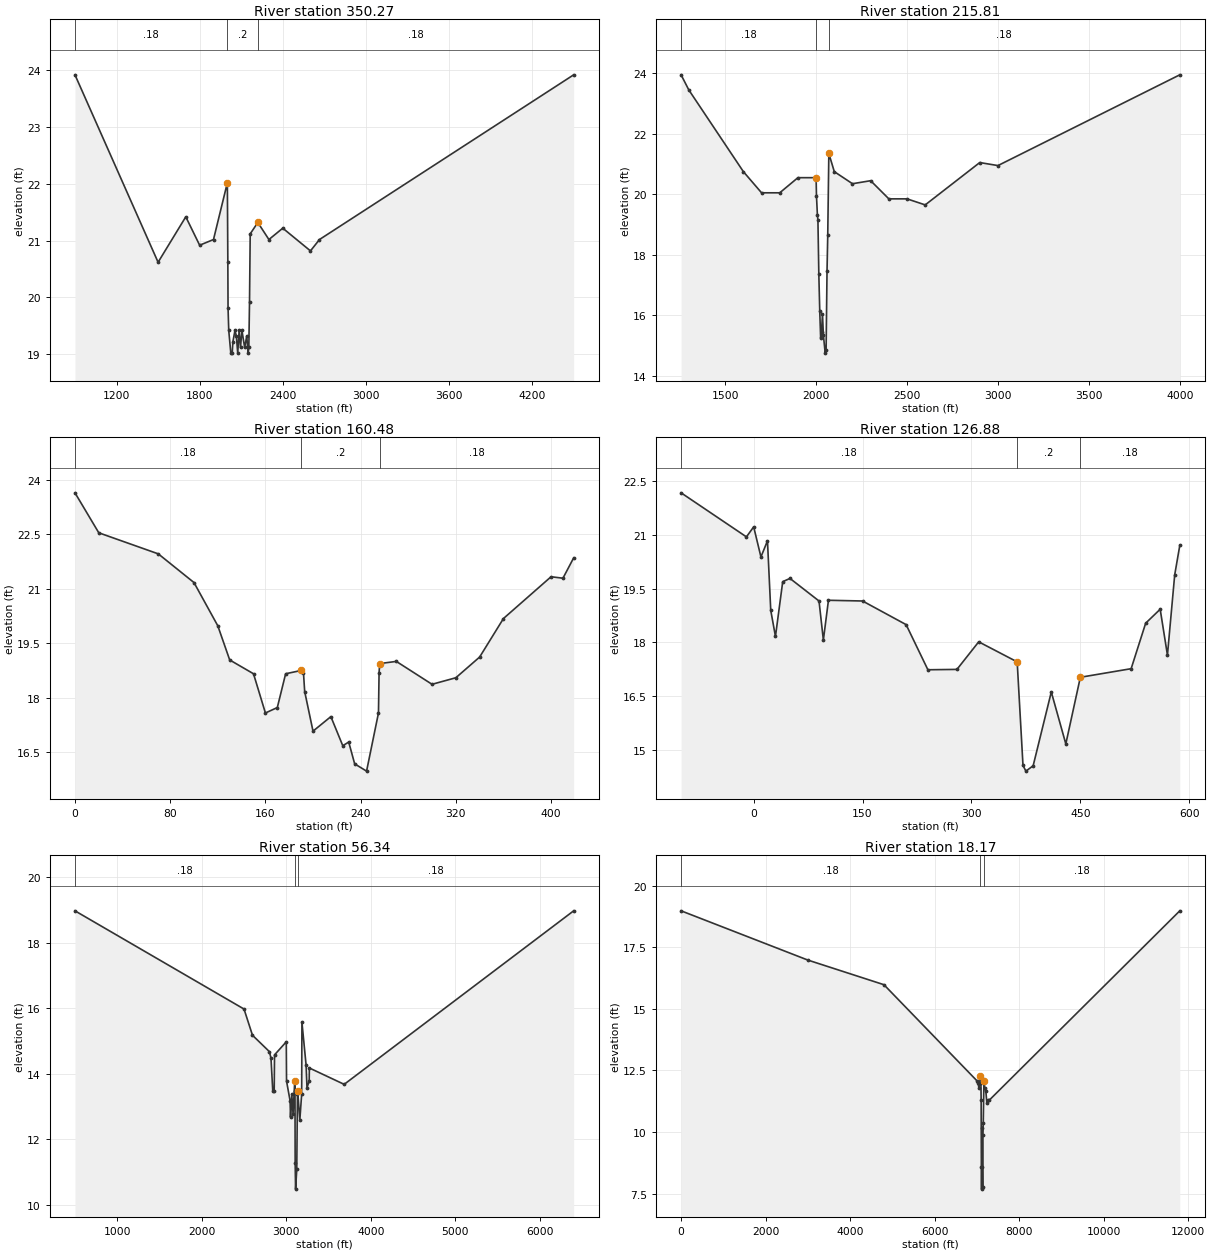
Type RM Length L Ch R = 1 ,350.27  ,13446.29,13446.29,13446.29
BEGIN DESCRIPTION:
ROK5
END DESCRIPTION:
Node Name=ROK5
XS GIS Cut Line= 2
 451861.670804883183629.38537002 451766.420704883183273.78467002
#Sta/Elev= 30
     900   23.92    1500   20.62    1700   21.42    1800   20.92    1900   21.02
    2000   22.02  2003.5   20.63    2005   19.82    2010   19.42    2025   19.02
    2035   19.02    2040   19.22    2055   19.42    2065   19.32    2075   19.02
    2085   19.42    2095   19.12    2105   19.42    2125   19.12    2140   19.32
    2150   19.02    2155   19.12    2160   19.92    2165   21.12    2220   21.32
    2300   21.02    2400   21.22    2600   20.82    2665   21.02    4500   23.92
#Mann= 3 , 0 , 0
     900     .18       0    2000      .2       0    2220     .18       0
Bank Sta=2000,2220
XS Rating Curve= 0 ,0
Vertical n Elevations= 5
      46      49      51      54     120
Vertical n for Station=900
     .22     .22     .22     .22     .22
Vertical n for Station=2000
      .2     .17     .14     .12      .1
Vertical n for Station=2220
     .22     .22     .22     .22     .22
Vertical n Flow=-1
Exp/Cntr=0.3,0.1

Type RM Length L Ch R = 1 ,215.81  ,5532.677,5532.677,5532.677
BEGIN DESCRIPTION:
ROK4
END DESCRIPTION:
Node Name=ROK4
XS GIS Cut Line= 2
 453798.424704883181095.73027002453442.8240048793181038.58017002
#Sta/Elev= 30
  1257.5   23.94    1300   23.44    1600   20.74    1700   20.04    1800   20.04
    1900   20.54    2000   20.54    2002   19.94    2007   19.32    2010   19.14
    2015   17.34    2020   16.14    2025   15.24    2030   15.44    2035   16.04
    2040   15.34    2050   14.74    2055   14.84    2060   17.44    2064   18.64
    2070   21.34    2100   20.74    2200   20.34    2300   20.44    2400   19.84
    2500   19.84    2600   19.64    2900   21.04    3000   20.94    4000   23.94
#Mann= 3 , 0 , 0
  1257.5     .18       0    2000      .2       0    2070     .18       0
Bank Sta=2000,2070
XS Rating Curve= 0 ,0
Vertical n Elevations= 5
      48      51      55      60     250
Vertical n for Station=1257.5
     .22     .22     .22     .22     .22
Vertical n for Station=2000
      .2     .17     .14     .12      .1
Vertical n for Station=2070
     .22     .22     .22     .22     .22
Vertical n Flow=-1
Exp/Cntr=0.3,0.1

Type RM Length L Ch R = 1 ,160.48  ,3360.203,3360.203,3360.203
BEGIN DESCRIPTION:
ROK3
END DESCRIPTION:
Node Name=ROK3
XS GIS Cut Line= 2
 453683.837304883179720.61477002 453618.766804883179618.24147002
#Sta/Elev= 30
       0  23.645      20  22.545      70  21.965     100  21.175     120  19.985
     130  19.045     150  18.665     160  17.585     170  17.735     177  18.665
     190  18.755     192  18.685     193  18.175     200  17.085     215  17.485
     225  16.685     230  16.785     235  16.185     245  15.985     255  17.585
   255.5  18.685     256  18.945     270  19.005     300  18.375     320  18.555
     340  19.125     360  20.185     400  21.335     410  21.295     419  21.855
#Mann= 3 , 0 , 0
       0     .18       0     190      .2       0     256     .18       0
Bank Sta=190,256
XS Rating Curve= 0 ,0
Vertical n Elevations= 5
      50      60      75     120     420
Vertical n for Station=0
     .22     .22     .22     .22     .22
Vertical n for Station=190
      .2     .17     .14     .12      .1
Vertical n for Station=256
     .22     .22     .22     .22     .22
Vertical n Flow=-1
Exp/Cntr=0.3,0.1

Type RM Length L Ch R = 1 ,126.88  ,7053.478,7053.478,7053.478
BEGIN DESCRIPTION:
ROK2
END DESCRIPTION:
Node Name=ROK2
XS GIS Cut Line= 2
454544.9803048793179351.14227002 454484.226104883179114.52637002
#Sta/Elev= 30
    -100  22.173     -10  20.943       0  21.223      10  20.383      19  20.833
    23.5  18.893      30  18.163      40  19.693      50  19.783      90  19.153
      96  18.063     103  19.173     150  19.153     210  18.493     240  17.233
     280  17.243     310  18.013     363  17.453     371  14.563     375  14.403
     385  14.553     410  16.613     430  15.163     450  17.023     520  17.263
     540  18.533     560  18.923     570  17.643     580  19.883     587  20.703
#Mann= 3 , 0 , 0
    -100     .18       0     363      .2       0     450     .18       0
Bank Sta=363,450
XS Rating Curve= 0 ,0
Vertical n Elevations= 5
      50      60      75     120     420
Vertical n for Station=-100
     .22     .22     .22     .22     .22
Vertical n for Station=363
      .2     .17     .14     .12      .1
Vertical n for Station=450
     .22     .22     .22     .22     .22
Vertical n Flow=-1
Exp/Cntr=0.3,0.1

Type RM Length L Ch R = 1 ,56.34   ,3817.881,3817.881,3817.881
BEGIN DESCRIPTION:
ROK1
END DESCRIPTION:
Node Name=ROK1
XS GIS Cut Line= 2
455779.6287048793178130.27437002455392.2779048793178035.02417002
#Sta/Elev= 30
     500   18.97    2500   15.97    2600   15.17    2800   14.67    2819   14.47
    2840   13.47    2857   13.47    2861   14.57    3000   14.97    3003   13.77
    3045   13.17    3050   12.67    3065   13.37    3080   12.77    3100   13.77
    3103   13.47    3105   11.27    3110   10.47    3124   11.07    3132   13.37
    3135   13.47    3160   12.57    3182   13.37    3185   15.57    3234   14.27
    3245   13.57    3271   13.77    3273   14.17    3685   13.67    6400   18.97
#Mann= 3 , 0 , 0
     500     .18       0    3100      .2       0    3135     .18       0
Bank Sta=3100,3135
XS Rating Curve= 0 ,0
Vertical n Elevations= 5
      50      60      75     120     420
Vertical n for Station=500
     .22     .22     .22     .22     .22
Vertical n for Station=3100
      .2     .17     .14     .12      .1
Vertical n for Station=3135
     .22     .22     .22     .22     .22
Vertical n Flow=-1
Exp/Cntr=0.3,0.1

Type RM Length L Ch R = 1 ,18.17   ,1816.503,1816.503,1816.503
BEGIN DESCRIPTION:
WK16
END DESCRIPTION:
Node Name=WK16
XS GIS Cut Line= 2
 456154.279404883176999.97207002455735.1786048793176961.87207002
#Sta/Elev= 23
       0   18.98    3000   16.98    4800   15.98    7000   12.08    7025   11.98
    7050   11.78    7075   12.28    7095   11.98    7100   11.28    7105    8.58
    7110    7.68    7125   10.18    7130    8.58    7135    7.78    7140    9.88
    7150   10.38    7165   12.08    7185   11.78    7210   11.68    7235   11.18
    7260   11.28    7285   11.28   11800   18.98
#Mann= 3 , 0 , 0
       0     .18       0    7075      .2       0    7165     .18       0
Bank Sta=7075,7165
XS Rating Curve= 0 ,0
Vertical n Elevations= 5
      50      60      75     120     420
Vertical n for Station=0
     .22     .22     .22     .22     .22
Vertical n for Station=7075
      .2     .17     .14     .12      .1
Vertical n for Station=7165
     .22     .22     .22     .22     .22
Vertical n Flow=-1
Exp/Cntr=0.3,0.1

River Reach=wekiva          ,wek_run

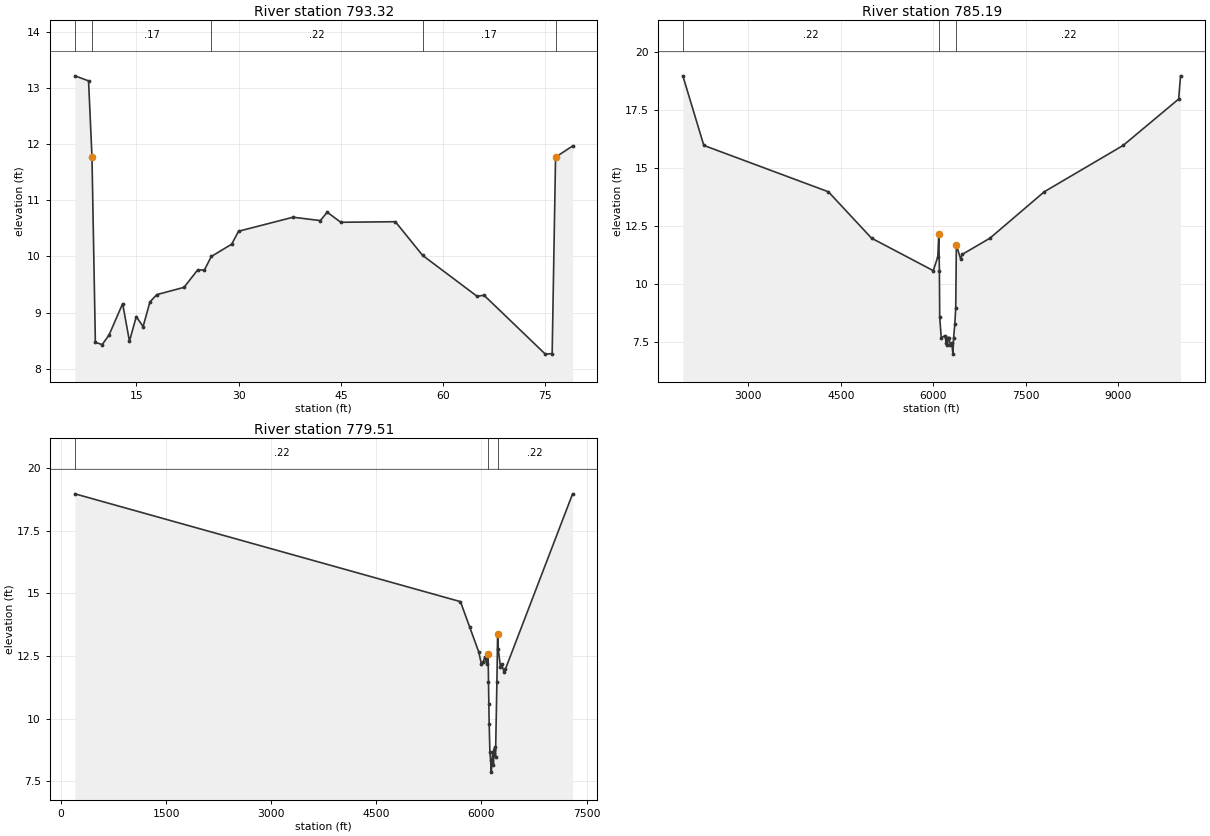
Type RM Length L Ch R = 1 ,793.32  ,813.0906,813.0906,813.0906
BEGIN DESCRIPTION:
WekSpr6
WekSpr6
END DESCRIPTION:
Node Name=WekSpr6
XS GIS Cut Line= 2
     455071.1753     3176243.645     455098.0644     3176211.408
#Sta/Elev= 30
       6   13.22       8   13.13     8.5   11.78       9    8.47      10    8.43
      11     8.6      13    9.16      14    8.49      15    8.93      16    8.75
      17    9.19      18    9.32      22    9.45      24    9.76      25    9.76
      26      10      29   10.22      30   10.45      38    10.7      42   10.64
      43   10.79      45   10.61      53   10.62      57   10.02      65    9.29
      66    9.31      75    8.26      76    8.27    76.5   11.77      79   11.97
#Mann= 5 ,-1 , 0
       6     .22       0     8.5     .17       0      26     .22       0
      57     .17       0    76.5     .22       0
Bank Sta=8.5,76.5
XS Rating Curve= 0 ,0
Exp/Cntr=0.3,0.1

Type RM Length L Ch R = 1 ,785.19  ,567.8806,567.8806,567.8806
BEGIN DESCRIPTION:
WEK13
END DESCRIPTION:
Node Name=WEK13
XS GIS Cut Line= 2
 455163.677404883176530.07117002455328.7778048793176295.12067002
#Sta/Elev= 30
    1940   18.99    2280   15.99    4300   13.99    5000   11.99    6000   10.59
    6075   11.19    6090   12.19    6100   10.59    6105    8.59    6130    7.69
    6190    7.79    6210    7.49    6220    7.69    6230    7.39    6240    7.69
    6250    7.69    6280    7.39    6300    7.49    6320    6.99    6330    7.69
    6350    8.29    6365    8.99    6375   11.69    6445   11.09    6470   11.29
    6920   11.99    7800   13.99    9080   15.99    9980   17.99   10010   18.99
#Mann= 3 , 0 , 0
    1940     .22       0    6090      .2       0    6375     .22       0
Bank Sta=6090,6375
XS Rating Curve= 0 ,0
Exp/Cntr=0.3,0.1

Type RM Length L Ch R = 1 ,779.51  ,3231.857,3231.857,3231.857
BEGIN DESCRIPTION:
WK17
END DESCRIPTION:
Node Name=WK17
XS GIS Cut Line= 2
      455414.687     3176429.959      455415.957     3176385.507
#Sta/Elev= 28
     200   18.97    5700   14.67    5830   13.67    5960   12.67    6000   12.17
    6025   12.27    6050   12.47    6075   12.17    6095   12.57    6100   11.47
    6105   10.57    6110    9.77    6120    8.67    6130    8.37    6140    7.87
    6160    8.67    6170    8.17    6180    8.77    6190    8.87    6200    8.47
    6220   11.47    6230   13.37    6240   12.77    6270   12.07    6290   12.17
    6320   11.87    6340   11.97    7300   18.97
#Mann= 3 , 0 , 0
     200     .22       0    6095      .2       0    6230     .22       0
Bank Sta=6095,6230
XS Rating Curve= 0 ,0
Exp/Cntr=0.3,0.1

River Reach=wekiva          ,wekiva_riv_up

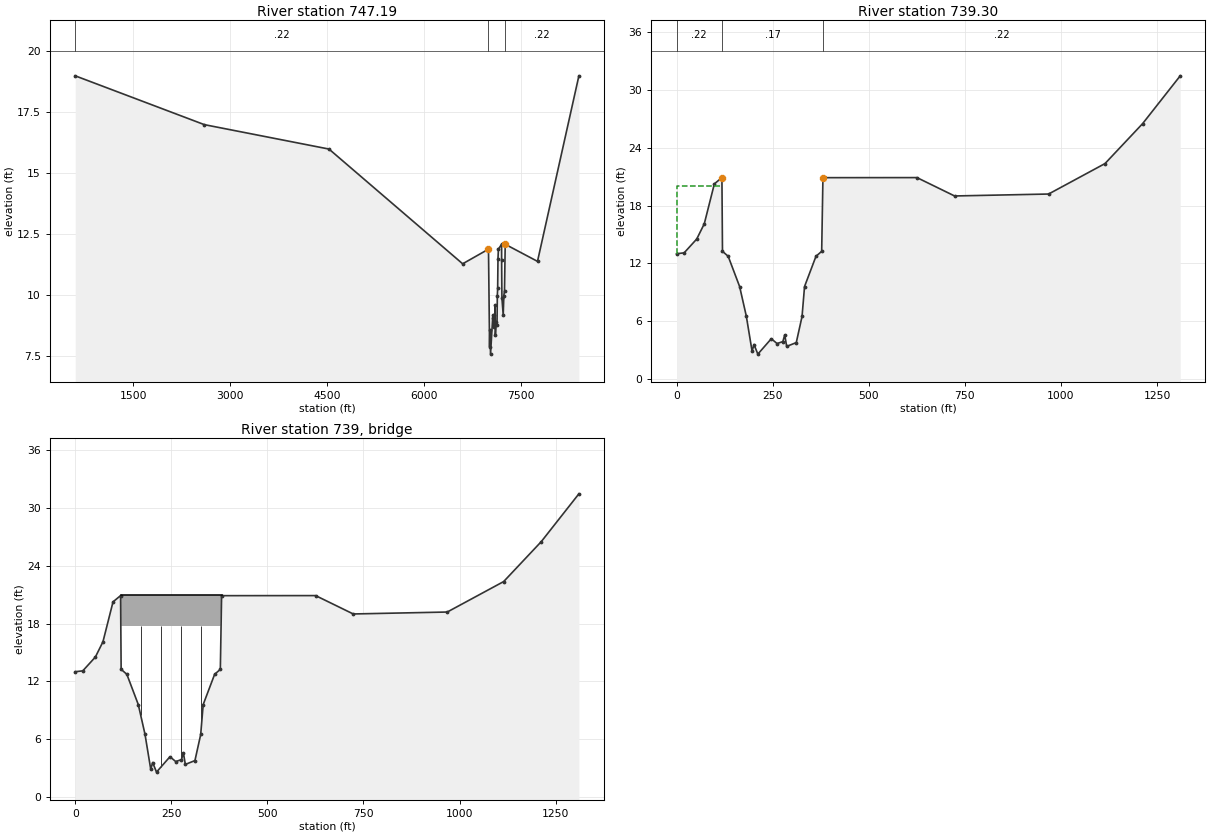
Type RM Length L Ch R = 1 ,747.19  ,799,799,799
BEGIN DESCRIPTION:
WEK12
END DESCRIPTION:
Node Name=WEK12
XS GIS Cut Line= 2
456440.0300048793176549.12117002 456224.129604883176390.37087002
#Sta/Elev= 30
     600   18.97    2600   16.97    4530   15.97    6600   11.27    7000   11.87
    7017    7.87    7022    8.57    7032    7.57    7067    9.17    7077    9.07
    7082    8.67    7092    9.17    7097    8.87    7102    9.57    7107    8.37
    7117    8.87    7132    8.77    7137    9.97    7142   10.27    7147   11.48
  7153.5   11.87    7203   12.07  7203.5   11.41    7208    9.87    7228    9.17
    7238    9.97    7248   10.17    7259   12.07    7759   11.37    8400   18.97
#Mann= 3 , 0 , 0
     600     .22       0    7000      .2       0    7259     .22       0
Bank Sta=7000,7259
XS Rating Curve= 0 ,0
Exp/Cntr=0.3,0.1

Type RM Length L Ch R = 1 ,739.30  ,50,50,50
BEGIN DESCRIPTION:
interpolation of WEK12 amd WK15
END DESCRIPTION:
#Sta/Elev= 30
       0      13  19.669   13.09  52.451  14.527   72.12  16.109  98.345  20.257
  118.01  20.907 119.465   13.25 134.331   12.73 164.063    9.59 181.465    6.52
 196.465    2.87 201.465    3.57 211.465    2.57 246.465    4.17 261.465    3.67
 276.465    3.87 281.465    4.57 286.465    3.37 311.465    3.77 326.465    6.48
 332.965    9.59 362.697   12.73 377.563   13.25  380.83  20.901 625.468  20.908
 723.322      19 967.956  19.2011114.737  22.3661212.591  26.5151310.444   31.48
#Mann= 3 , 0 , 0
       0     .22       0  118.01     .17       0  380.83     .22       0
#XS Ineff= 1 ,-1
       0  118.01      20
Permanent Ineff=
       F
Bank Sta=118.01,380.83
XS Rating Curve= 0 ,0
Exp/Cntr=0.3,0.1

Type RM Length L Ch R = 3 ,739     ,,,
Bridge Culvert--1,0,-1,-1, 0
Deck Dist Width WeirC Skew NumUp NumDn MinLoCord MaxHiCord MaxSubmerge Is_Ogee
10,30,2.6,0, 2, 2, , , 0.98, 0, 0,0,,
     118   380.9
      21      21
   17.75   17.75
     118   380.9
      21      21
   17.75   17.75
Pier Skew, UpSta & Num, DnSta & Num=  ,170.5, 2 ,170.5, 2 , 0 , 0 , 0 ,,
       1       1
       0      21
       1       1
       0      21
Pier Skew, UpSta & Num, DnSta & Num=  ,223, 2 ,223, 2 , 0 , 0 , 0 ,,
       1       1
       0      21
       1       1
       0      21
Pier Skew, UpSta & Num, DnSta & Num=  ,275.5, 2 ,275.5, 2 , 0 , 0 , 0 ,,
       1       1
       0      21
       1       1
       0      21
Pier Skew, UpSta & Num, DnSta & Num=  ,328, 2 ,328, 2 , 0 , 0 , 0 ,,
       1       1
       0      21
       1       1
       0      21
BR Coef=-1 , 0 , 0 ,, 0 ,,,0.8,-1,,0,
WSPro=,,,, 1 ,,,, 0 ,,,, 0 ,,,,-1 ,-1 ,-1 , 0 , 0 , 0 , 0 , 0
BC Design=,, 0 ,, 0 ,,,,,,
BC Use User HTab Curves=0
BC User HTab FreeFlow(D)= 0