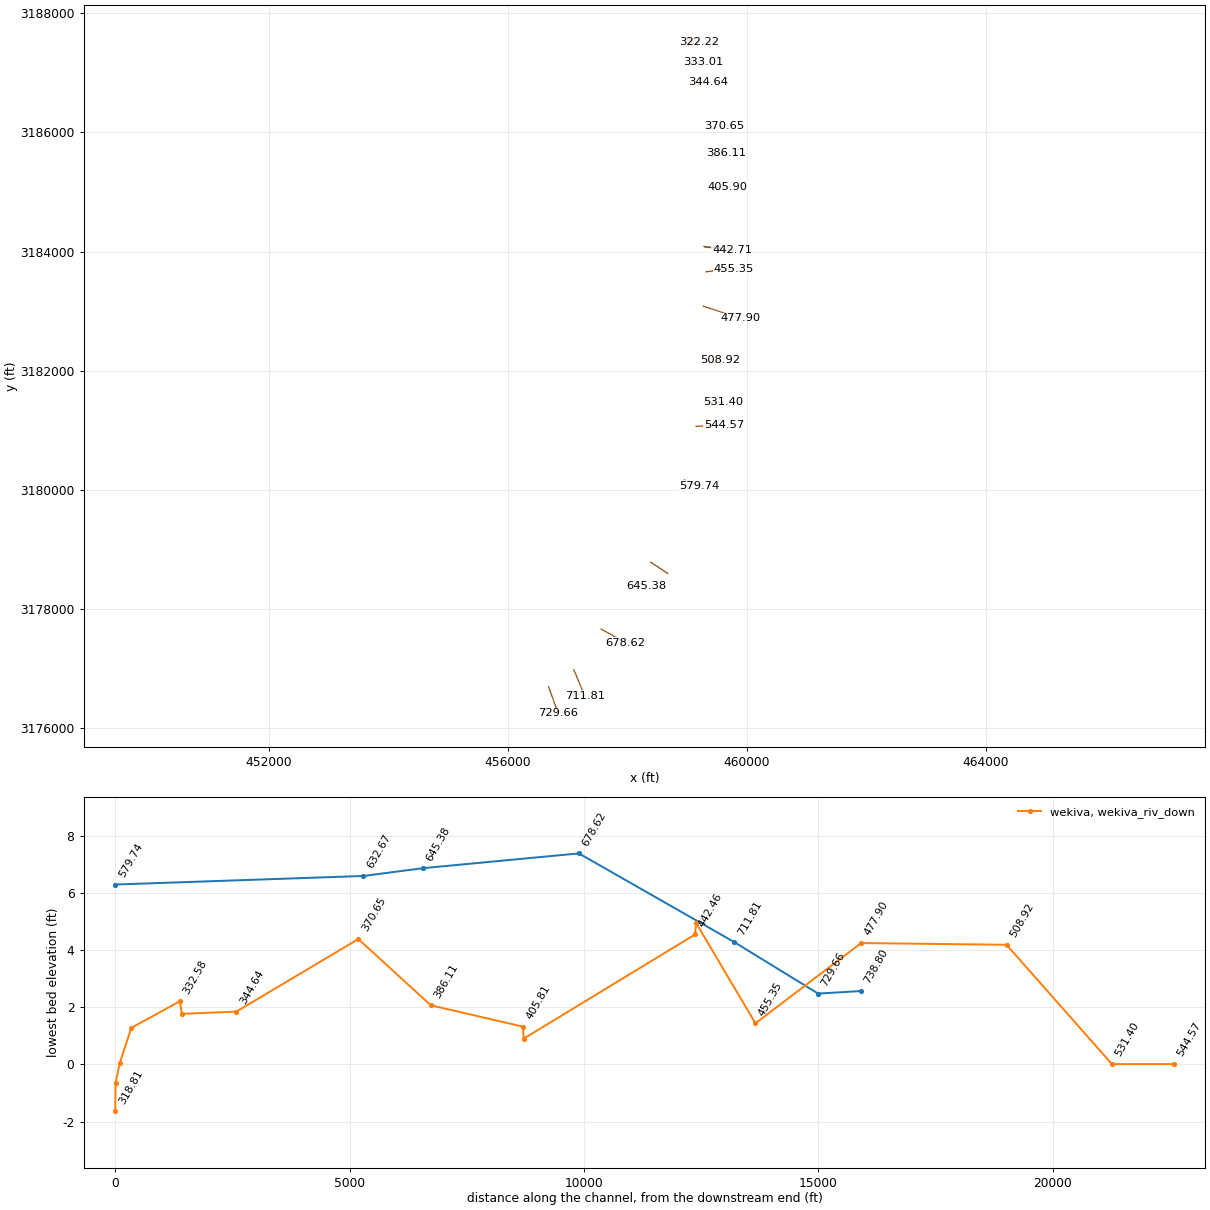
HEC-RAS study wekiva_ras.prj: wekiva_ras

--- wekiva_ras.g06 (geometry) --- (continued)

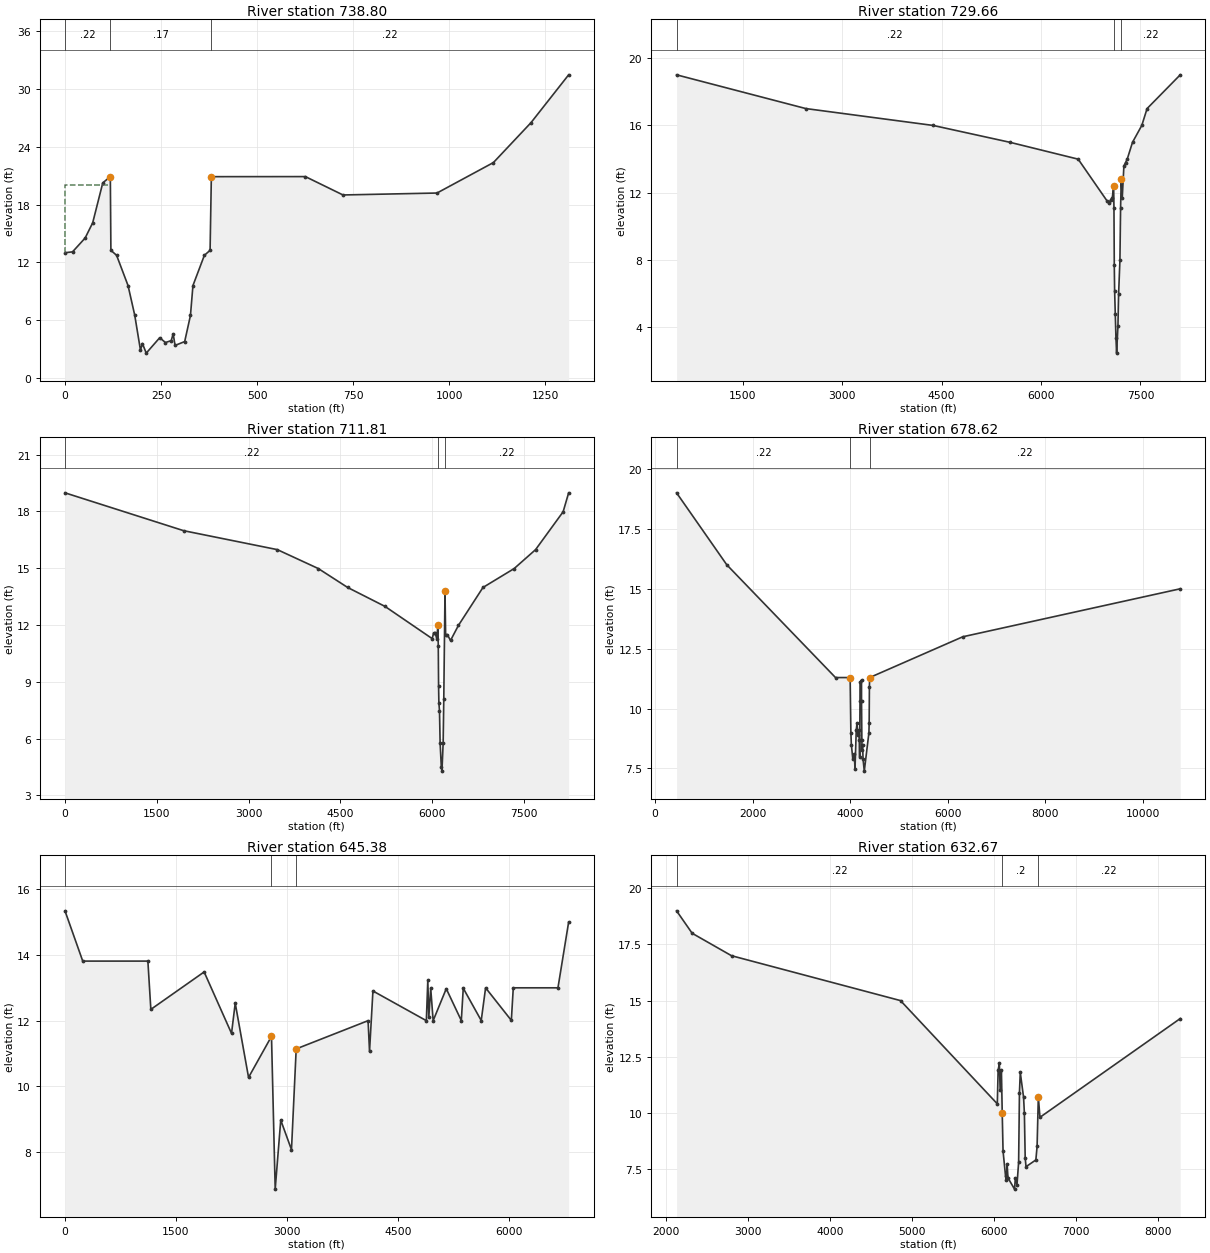
Type RM Length L Ch R = 1 ,738.80  ,914,914,914
BEGIN DESCRIPTION:
interpolation of WEK12 amd WK15
END DESCRIPTION:
#Sta/Elev= 30
       0      13  19.669   13.09  52.451  14.527   72.12  16.109  98.345  20.257
  118.01  20.907 119.465   13.25 134.331   12.73 164.063    9.59 181.465    6.52
 196.465    2.87 201.465    3.57 211.465    2.57 246.465    4.17 261.465    3.67
 276.465    3.87 281.465    4.57 286.465    3.37 311.465    3.77 326.465    6.48
 332.965    9.59 362.697   12.73 377.563   13.25  380.83  20.901 625.468  20.908
 723.322      19 967.956  19.2011114.737  22.3661212.591  26.5151310.444   31.48
#Mann= 3 , 0 , 0
       0     .22       0  118.01     .17       0  380.83     .22       0
#XS Ineff= 1 ,-1
       0  118.01      20
Permanent Ineff=
       F
Bank Sta=118.01,380.83
XS Rating Curve= 0 ,0
Exp/Cntr=0.3,0.1

Type RM Length L Ch R = 1 ,729.66  ,1785.368,1785.368,1785.368
BEGIN DESCRIPTION:
WK15
END DESCRIPTION:
Node Name=WK15
XS GIS Cut Line= 2
 456677.599504883176700.20887002 456838.889904883176250.62797002
#Sta/Elev= 29
     500   18.98    2450   16.98    4370   15.98    5530   14.98    6560   13.98
    7000   11.48    7025   11.38    7050   11.58    7075   11.68    7095   12.38
    7100   11.08    7105    7.68    7110    6.18    7120    4.78    7130    3.38
    7140    2.48    7160    4.08    7170    5.98    7190    7.98    7200   11.08
    7210   12.78    7225   11.68    7250   13.58    7275   13.78    7300   13.98
    7380   14.98    7520   15.98    7600   16.98    8100   18.98
#Mann= 3 , 0 , 0
     500     .22       0    7095     .17       0    7210     .22       0
Bank Sta=7095,7210
XS Rating Curve= 0 ,0
Exp/Cntr=0.3,0.1

Type RM Length L Ch R = 1 ,711.81  ,3318.996,3318.996,3318.996
BEGIN DESCRIPTION:
WK14
END DESCRIPTION:
Node Name=WK14
XS GIS Cut Line= 2
457102.1360048793176981.74307002 457281.206304883176548.67217002
#Sta/Elev= 30
       1   18.98    1940   16.98    3470   15.98    4140   14.98    4620   13.98
    5230   12.98    6000   11.28    6025   11.58    6050   11.58    6075   11.28
    6095   11.98    6100   10.88    6105    8.78    6110    7.88    6120    7.48
    6130    5.78    6150    4.48    6160    4.28    6180    5.78    6190    8.08
    6210   13.78    6220   11.48    6250   11.48    6300   11.18    6430   11.98
    6830   13.98    7340   14.98    7690   15.98    8140   17.98    8230   18.98
#Mann= 3 , 0 , 0
       1     .22       0    6095     .17       0    6210     .22       0
Bank Sta=6095,6210
XS Rating Curve= 0 ,0
Exp/Cntr=0.3,0.1

Type RM Length L Ch R = 1 ,678.62  ,3324.147,3324.147,3324.147
BEGIN DESCRIPTION:
WEK11
END DESCRIPTION:
Node Name=WEK11
XS GIS Cut Line= 2
457559.9719048793177663.64977002 457967.642704883177438.85927002
#Sta/Elev= 30
     440   18.99    1470   15.99    3700   11.29    4000   11.29    4015    8.99
    4025    8.49    4055    7.89    4085    8.09    4100    7.49    4125    9.09
    4140    9.39    4165    8.89    4175    9.09    4190    8.69    4195    7.99
    4202   10.32    4203   11.09    4233   11.19  4233.5   10.32    4240    8.69
    4245    8.29    4255    8.49    4265    7.89    4290    7.39    4385    8.99
    4390    9.39    4395   10.89    4400   11.29    6310   12.99   10770   14.99
#Mann= 3 , 0 , 0
     440     .22       0    4000      .2       0    4400     .22       0
Bank Sta=4000,4400
XS Rating Curve= 0 ,0
Vertical n Elevations= 5
     110     130     250     550    1000
Vertical n for Station=440
     .22     .22     .22     .22     .22
Vertical n for Station=4000
      .2     .19    .185    .115      .1
Vertical n for Station=4400
     .22     .22     .22     .22     .22
Vertical n Flow=-1
Exp/Cntr=0.3,0.1

Type RM Length L Ch R = 1 ,645.38  ,1271.129,1271.129,1271.129
BEGIN DESCRIPTION:
MFL_Swamp
END DESCRIPTION:
Node Name=MFL_Swamp
XS GIS Cut Line= 2
 458158.511704883178457.50277002458316.381727685 3178386.7275856
#Sta/Elev= 30
       0  15.343     240  13.813    1120  13.813    1160  12.343    1880  13.483
    2250  11.613    2300  12.533    2480  10.273    2790  11.523    2840   6.873
    2915   8.973    3060   8.073 3123.69 11.14064094.677      124114.359 11.0629
4160.284 12.90364881.959      124901.641 13.22834914.763 12.10014941.005 12.9811
4973.809      125150.947 12.97325354.329 12.00285380.571 12.98775623.317  12.004
5682.363      13 6030.08 12.00846056.322      136659.905      136804.241      15
#Mann= 3 , 0 , 0
       0       0       0    2790       0       0 3123.69       0       0
Bank Sta=2790,3123.69
XS Rating Curve= 0 ,0
Vertical n Elevations= 5
     110     130     250     550    1000
Vertical n for Station=0
     .22     .22     .22     .22     .22
Vertical n for Station=2790
      .2     .19    .185    .115      .1
Vertical n for Station=3123.69
     .22     .22     .22     .22     .22
Vertical n Flow=-1
Exp/Cntr=0.3,0.1

Type RM Length L Ch R = 1 ,632.67  ,5292.979,5292.979,5292.979
BEGIN DESCRIPTION:
WK12
END DESCRIPTION:
Node Name=WK12
XS GIS Cut Line= 2
 458386.943904883178788.98237002458672.6945048793178598.48197002
#Sta/Elev= 30
    2130      19    2320      18    2800      17    4860      15    6040    10.4
    6050    11.9    6065    12.2    6075      11    6090    11.9    6100      10
    6110     8.3    6140     7.2    6150       7    6160     7.7    6170     7.1
    6250     6.6    6260     7.1    6280     6.8    6300     7.8    6310    10.9
    6320    11.8    6360    10.7    6370      10    6380       8    6390     7.6
    6510     7.9    6525     8.5    6540    10.7    6560     9.8    8270    14.2
#Mann= 3 , 0 , 0
    2130     .22       0    6100      .2       0    6540     .22       0
Bank Sta=6100,6540
XS Rating Curve= 0 ,0
Vertical n Elevations= 5
     110     130     250     550    1000
Vertical n for Station=2130
     .22     .22     .22     .22     .22
Vertical n for Station=6100
      .2     .19    .185    .115      .1
Vertical n for Station=6540
     .22     .22     .22     .22     .22
Vertical n Flow=-1
Exp/Cntr=0.3,0.1

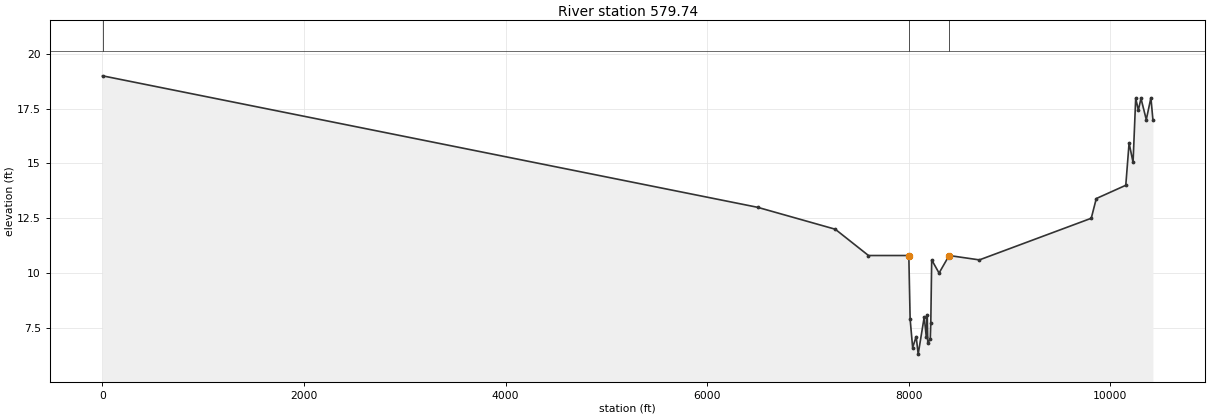
Type RM Length L Ch R = 1 ,579.74  ,3517.093,3517.093,3517.093
BEGIN DESCRIPTION:
WEK10
END DESCRIPTION:
Node Name=WEK10
XS GIS Cut Line= 2
 458952.095004883180166.93507002 459206.095504883180065.33487002
#Sta/Elev= 30
       1      19    6500      13    7270      12    7600    10.8    8000    10.8
    8013     7.9    8038     6.6    8073     7.1    8093     6.3    8153       8
    8173     7.1    8183     8.1    8188     6.8    8213       7    8218     7.7
    8227    10.6    8300      10    8400    10.8    8700    10.6    9810    12.5
    9860    13.410152.57 14.005210185.37  15.93410224.74 15.050110250.98 17.9763
10277.23 17.435310303.47 17.967810355.96      1710401.89      1810421.57      17
#Mann= 3 , 0 , 0
       1       0       0    8000       0       0    8400       0       0
Bank Sta=8000,8400
XS Rating Curve= 0 ,0
Vertical n Elevations= 5
     110     130     250     550    1000
Vertical n for Station=1
     .22     .22     .22     .22     .22
Vertical n for Station=8000
      .2     .19    .185    .115      .1
Vertical n for Station=8400
     .22     .22     .22     .22     .22
Vertical n Flow=-1
Exp/Cntr=0.3,0.1

River Reach=wekiva          ,wekiva_riv_down

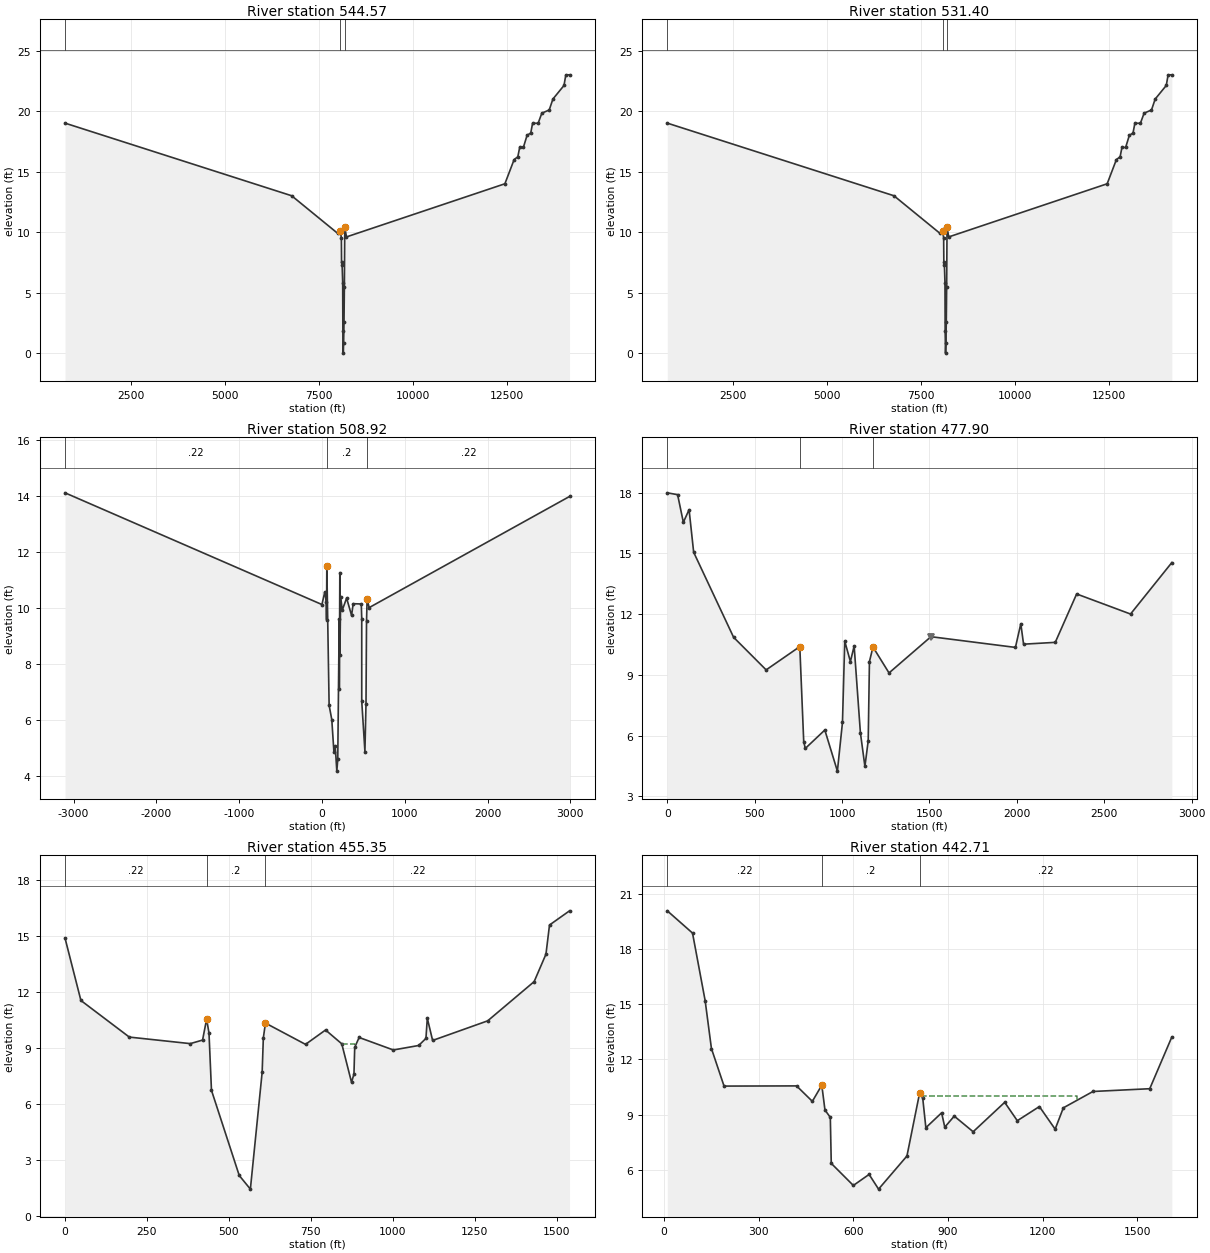
Type RM Length L Ch R = 1 ,544.57  ,1316.962,1316.962,1316.962
BEGIN DESCRIPTION:
WK11
END DESCRIPTION:
Node Name=WK11
XS GIS Cut Line= 2
 459150.085604883181066.69207002459617.8699048793181089.97547002
#Sta/Elev= 30
     760   19.01    6780   13.01    8000    9.91    8075   10.11    8100    9.51
    8105    7.51    8120    7.31    8135    5.81    8140    1.81    8150     .01
    8160     .81    8170    2.61    8180    5.51    8190   10.41    8235    9.61
12443.03      14 12688.3      1612786.41 16.225112835.47      1712933.58      17
13031.69      18 13129.8  18.19613178.85      1913326.02      1913424.13  19.833
13620.34 20.096213718.46      2114012.78  22.12114061.84      2314159.95      23
#Mann= 3 , 0 , 0
     760       0       0    8075       0       0    8190       0       0
Bank Sta=8075,8190
XS Rating Curve= 0 ,0
Vertical n Elevations= 5
     140     200     400     700    2000
Vertical n for Station=760
     .22     .22     .22     .22     .22
Vertical n for Station=8075
      .2     .16     .13    .115      .1
Vertical n for Station=8190
     .22     .22     .22     .22     .22
Vertical n Flow=-1
Exp/Cntr=0.3,0.1

Type RM Length L Ch R = 1 ,531.40  ,2248.064,2248.064,2248.064
BEGIN DESCRIPTION:
WEK9-copy of WK11
END DESCRIPTION:
Node Name=WEK9-copy of WK1
XS GIS Cut Line= 2
459275.9457048793181462.33767002 459599.796304883181468.68767002
#Sta/Elev= 30
     760   19.01    6780   13.01    8000    9.91    8075   10.11    8100    9.51
    8105    7.51    8120    7.31    8135    5.81    8140    1.81    8150     .01
    8160     .81    8170    2.61    8180    5.51    8190   10.41    8235    9.61
12443.03      14 12688.3      1612786.41 16.225112835.47      1712933.58      17
13031.69      18 13129.8  18.19613178.85      1913326.02      1913424.13  19.833
13620.34 20.096213718.46      2114012.78  22.12114061.84      2314159.95      23
#Mann= 3 , 0 , 0
     760       0       0    8075       0       0    8190       0       0
Bank Sta=8075,8190
XS Rating Curve= 0 ,0
Vertical n Elevations= 5
     140     200     400     700    2000
Vertical n for Station=760
     .22     .22     .22     .22     .22
Vertical n for Station=8075
      .2     .16     .13    .115      .1
Vertical n for Station=8190
     .22     .22     .22     .22     .22
Vertical n Flow=-1
Exp/Cntr=0.3,0.1

Type RM Length L Ch R = 1 ,508.92  ,3101.706,3101.706,3101.706
BEGIN DESCRIPTION:
XS20
END DESCRIPTION:
Node Name=XS20
XS GIS Cut Line= 2
 459382.978204883182113.81057002459543.4649048793182178.38367002
#Sta/Elev= 30
-3102.51   14.13       0   10.14   34.59   10.59    53.2   10.24   55.67     9.6
   58.88   11.52   86.84    6.54  119.05    6.03  144.51    4.88  160.75    5.07
  179.83    4.19  191.14    4.61  208.59    9.63  209.83    7.12  216.06   11.28
  216.99    8.35  226.31   10.41  245.77    9.94  297.99   10.37  357.95    9.75
  377.47   10.17  475.33   10.16  480.81    9.62  480.85    6.68  519.11    4.89
  532.14    6.59  538.39    9.54  545.77   10.34  569.93   10.03    2990      14
#Mann= 3 , 0 , 0
-3102.51     .22       0   58.88      .2       0  545.77     .22       0
Bank Sta=58.88,545.77
XS Rating Curve= 0 ,0
Vertical n Elevations= 5
     140     200     400     700    2000
Vertical n for Station=-3102.51
     .22     .22     .22     .22     .22
Vertical n for Station=58.88
      .2     .16     .13    .115      .1
Vertical n for Station=545.77
     .22     .22     .22     .22     .22
Vertical n Flow=-1
Exp/Cntr=0.3,0.1

Type RM Length L Ch R = 1 ,477.90  ,2254.396,2254.396,2254.396
BEGIN DESCRIPTION:
XS19
END DESCRIPTION:
Node Name=XS19
XS GIS Cut Line= 2
459271.5415048793183081.79267002 459890.675604883182878.71667002
#Sta/Elev= 30
       0 17.995459.04105 17.903991.84163 16.5384124.6422 17.1636150.8827 15.0603
379.3715   10.86565.5315    9.25758.0715    10.4780.5015    5.71789.5215    5.37
901.2415    6.28973.1815    4.251002.232    6.661015.182   10.671047.601    9.66
1069.011   10.431104.761    6.151130.611    4.481149.491    5.751156.511    9.66
1176.702   10.381268.562     9.11508.511   10.891991.751   10.362022.501   11.53
2038.302   10.522219.632   10.612341.962      132650.287 12.00882886.451   14.55
#Mann= 3 , 0 , 0
       0       0       0758.0715       0       01176.702       0       0
Levee=0,,,-1,1508.511,10.89,,
Bank Sta=758.0715,1176.702
XS Rating Curve= 0 ,0
Vertical n Elevations= 5
     140     200     400     700    2000
Vertical n for Station=0
     .22     .22     .22     .22     .22
Vertical n for Station=758.0715
      .2     .16     .13    .115      .1
Vertical n for Station=1176.702
     .22     .22     .22     .22     .22
Vertical n Flow=-1
Exp/Cntr=0.3,0.1

Type RM Length L Ch R = 1 ,455.35  ,1264.567,1264.567,1264.567
BEGIN DESCRIPTION:
XS18
END DESCRIPTION:
Node Name=XS18
XS GIS Cut Line= 2
 459315.849904883183660.11847002459780.8486048793183714.78067002
#Sta/Elev= 30
       0   14.88    48.5   11.54  196.17    9.58  382.17    9.23  419.67    9.42
  432.03   10.54  439.28     9.8  446.85    6.73  531.56    2.17  565.54    1.44
   601.5     7.7  605.09    9.54  611.58   10.33  733.81    9.19  794.93    9.96
   844.4    9.22  874.17    7.16  881.58     7.6   883.9    9.03  897.32    9.56
 1001.73    8.89 1078.97    9.13 1101.23    9.51 1105.35   10.59 1121.59     9.4
 1289.61   10.45 1431.37   12.55 1467.39   14.02 1478.21   15.58 1539.32   16.34
#Mann= 3 , 0 , 0
       0     .22       0  432.03      .2       0  611.58     .22       0
#XS Ineff= 1 ,-1
   844.4   883.9    9.22
Permanent Ineff=
       T
Bank Sta=432.03,611.58
XS Rating Curve= 0 ,0
Vertical n Elevations= 5
     140     200     400     700    2000
Vertical n for Station=0
     .22     .22     .22     .22     .22
Vertical n for Station=432.03
      .2     .16     .13    .115      .1
Vertical n for Station=611.58
     .22     .22     .22     .22     .22
Vertical n Flow=-1
Exp/Cntr=0.3,0.1

Type RM Length L Ch R = 1 ,442.71  ,25.1312,25.1312,25.1312
BEGIN DESCRIPTION:
MFL_RailRoad
END DESCRIPTION:
Node Name=MFL_RailRoad
XS GIS Cut Line= 3
459294.4409314813184076.20246875 459738.939404883184021.20627002
459748.8637314813184019.97836875
#Sta/Elev= 30
      10  20.083      90  18.873     130  15.203     150  12.593     190  10.553
     420  10.563     470   9.723     500  10.603     510   9.253     527    8.85
     530    6.35     600    5.15     650    5.75     680    4.95     770    6.75
     810   10.16     820    9.91     830    8.29     880     9.1     890    8.32
     920    8.92     980    8.07    1080    9.67    1120    8.67    1190    9.44
    1240    8.21    1266    9.37    1360   10.26    1540   10.41    1610   13.22
#Mann= 3 , 0 , 0
      10     .22       0     500      .2       0     810     .22       0
#XS Ineff= 1 ,-1
     820    1310      10
Permanent Ineff=
       F
Bank Sta=500,810
XS Rating Curve= 0 ,0
Vertical n Elevations= 5
     140     200     400     700    2000
Vertical n for Station=10
     .22     .22     .22     .22     .22
Vertical n for Station=500
      .2     .16     .13    .115      .1
Vertical n for Station=810
     .22     .22     .22     .22     .22
Vertical n Flow=-1
Exp/Cntr=0.3,0.1

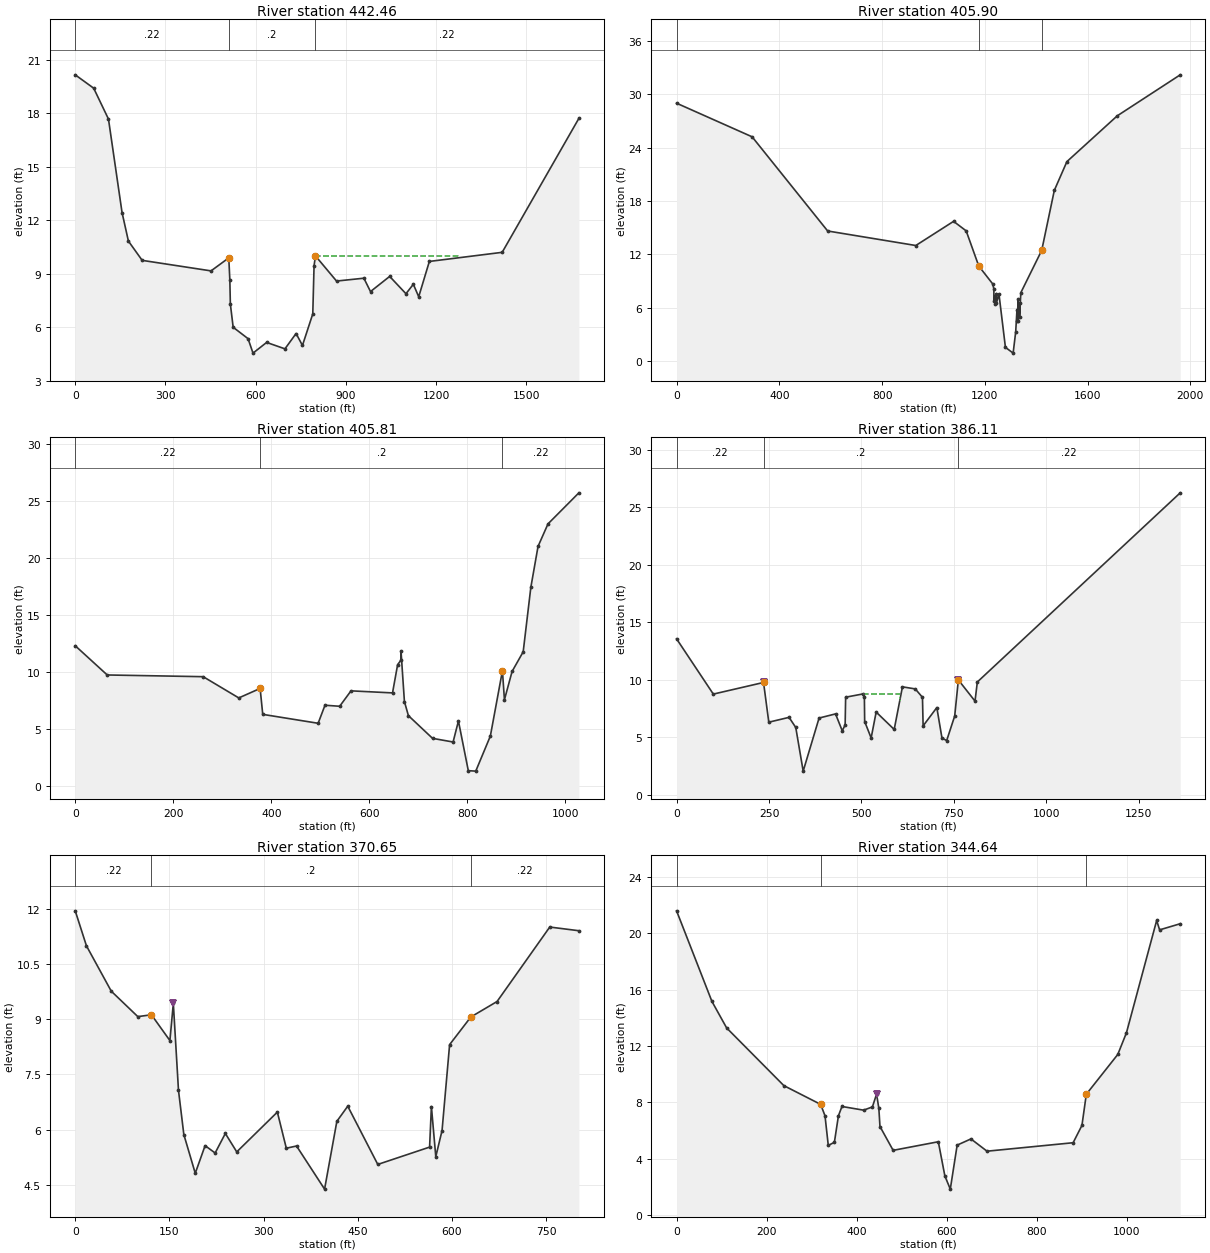
Type RM Length L Ch R = 1 ,442.46  ,3655.741,3655.741,3655.741
BEGIN DESCRIPTION:
XS17
END DESCRIPTION:
Node Name=XS17
XS GIS Cut Line= 2
 459280.081504883184086.22197002459785.7691048793184022.15867002
#Sta/Elev= 30
       0   20.15   61.42    19.4  110.54   17.67  155.69   12.43  176.82   10.83
  222.58    9.75  451.56    9.16  510.58    9.89  514.08    8.64   515.8     7.3
  525.13       6  574.67    5.36  591.09    4.55  636.43    5.15  697.31    4.79
  734.32    5.65   755.5    4.98  789.84    6.75  794.07    9.44  798.73      10
  868.83    8.59   959.7    8.75  981.77       8 1045.46    8.85 1099.65    7.88
 1124.21    8.41 1142.03    7.71 1177.45    9.69 1419.54    10.2 1674.61   17.71
#Mann= 3 , 0 , 0
       0     .22       0  510.58      .2       0  798.73     .22       0
#XS Ineff= 1 ,-1
  798.73 1274.28      10
Permanent Ineff=
       F
Bank Sta=510.58,798.73
XS Rating Curve= 0 ,0
Vertical n Elevations= 5
     140     200     400     700    2000
Vertical n for Station=0
     .22     .22     .22     .22     .22
Vertical n for Station=510.58
      .2     .16     .13    .115      .1
Vertical n for Station=798.73
     .22     .22     .22     .22     .22
Vertical n Flow=-1
Exp/Cntr=0.3,0.1

Type RM Length L Ch R = 1 ,405.90  ,9.2192,9.2192,9.2192
BEGIN DESCRIPTION:
MFL_RailRoadGage
END DESCRIPTION:
Node Name=MFL_RailRoadGage
XS GIS Cut Line= 2
 459603.299504883185076.81517002 459677.277104883185087.76887002
#Sta/Elev= 30
       0      29 294.057 25.2198588.1141 14.6321931.1806      131078.209 15.7152
1127.219 14.64491176.228 10.6903    1230     8.7    1235    8.14    1235     6.8
    1240     7.3    1240     6.4    1245     7.6    1245    6.55    1255     7.5
    1280    1.55    1310      .9    1320     3.3    1325     5.8    1325     4.5
    1330    6.95    1330    4.55    1335    6.48    1335       5    1340     7.7
1421.276  12.4551470.285 19.19661519.295 22.43141715.333 27.5808 1960.38 32.1892
#Mann= 3 , 0 , 0
       0       0       01176.228       0       01421.276       0       0
Bank Sta=1176.228,1421.276
XS Rating Curve= 0 ,0
Vertical n Elevations= 5
     140     200     400     700    2000
Vertical n for Station=0
     .22     .22     .22     .22     .22
Vertical n for Station=1176.228
      .2     .16     .13    .115      .1
Vertical n for Station=1421.276
     .22     .22     .22     .22     .22
Vertical n Flow=-1
Exp/Cntr=0.3,0.1

Type RM Length L Ch R = 1 ,405.81  ,1969.554,1969.554,1969.554
BEGIN DESCRIPTION:
XS16
END DESCRIPTION:
Node Name=XS16
XS GIS Cut Line= 2
459410.1413048793185050.46617002459718.6545048793185096.86167002
#Sta/Elev= 30
       0    12.3   65.29    9.74  261.09    9.59  333.74    7.73  377.28    8.56
  382.63    6.29  495.65    5.51  509.62    7.09  539.61       7  562.74    8.35
  647.44    8.17  657.82   10.64  664.71   11.04  664.79    11.8  671.71    7.41
  679.81    6.18   729.1    4.19  771.02    3.87  781.92    5.71  802.06    1.36
  817.27    1.32  847.04    4.39  871.69   10.11  875.78    7.57   891.4   10.05
  914.04   11.77  929.68   17.42  944.36      21  964.64   22.97  1027.7   25.69
#Mann= 3 , 0 , 0
       0     .22       0  377.28      .2       0  871.69     .22       0
#XS Ineff= 1 ,-1
       0  664.79    11.8
Permanent Ineff=
       T
Bank Sta=377.28,871.69
XS Rating Curve= 0 ,0
Vertical n Elevations= 5
     140     200     400     700    2000
Vertical n for Station=0
     .22     .22     .22     .22     .22
Vertical n for Station=337.28
      .2     .16     .13    .115      .1
Vertical n for Station=871.69
     .22     .22     .22     .22     .22
Vertical n Flow=-1
Exp/Cntr=0.3,0.1

Type RM Length L Ch R = 1 ,386.11  ,1546.096,1546.096,1546.096
BEGIN DESCRIPTION:
XS15
END DESCRIPTION:
Node Name=XS15
XS GIS Cut Line= 2
 459399.141704883185586.81687002459651.3766048793185653.23407002
#Sta/Elev= 30
       0   13.56   99.37    8.76  235.15    9.77  249.36    6.32  304.14    6.74
  322.28    5.86  342.34    2.07  385.31    6.68  429.82    7.04     448    5.57
  455.79    6.09  457.13    8.49  504.92    8.78  507.78    8.55  508.57    6.38
  526.09    4.95  539.65     7.2  588.42    5.69  610.73    9.39  645.37    9.21
  664.84    8.48  666.61       6  703.68    7.59  717.54    4.95  730.27    4.72
  752.03    6.86  761.89    9.99  806.94    8.15  813.18    9.81 1361.78   26.24
#Mann= 3 , 0 , 0
       0     .22       0  235.15      .2       0  761.89     .22       0
Levee=-1,235.15,9.77,-1,761.89,9.99,,
#XS Ineff= 3 ,-1
  504.92  603.38    8.78  610.73  761.89    9.39  761.89  837.84    9.99
Permanent Ineff=
       F       F       F
Bank Sta=235.15,761.89
XS Rating Curve= 0 ,0
Vertical n Elevations= 5
     140     200     400     700    2000
Vertical n for Station=0
     .22     .22     .22     .22     .22
Vertical n for Station=235.15
      .2     .16     .13    .115      .1
Vertical n for Station=761.89
     .22     .22     .22     .22     .22
Vertical n Flow=-1
Exp/Cntr=0.3,0.1

Type RM Length L Ch R = 1 ,370.65  ,2601.247,2601.247,2601.247
BEGIN DESCRIPTION:
XS14
END DESCRIPTION:
Node Name=XS14
XS GIS Cut Line= 2
459377.3931048793186056.84457002459614.9912048793186110.32587002
#Sta/Elev= 30
       0   11.94   17.89   10.99   57.42    9.76   99.71    9.07   121.4    9.12
  150.84    8.42  156.28    9.43   164.5    7.07  173.03    5.87  191.23    4.82
  206.89    5.57  222.88    5.37  239.15     5.9  257.33     5.4  322.01    6.48
  336.28     5.5  352.58    5.56  397.24    4.39  416.81    6.23  434.15    6.64
     482    5.06  564.53    5.53  567.41    6.63   574.4    5.27  584.38    5.98
  596.42    8.31  630.25    9.06  672.03    9.48  755.96    11.5  802.37    11.4
#Mann= 3 , 0 , 0
       0     .22       0   121.4      .2       0  630.25     .22       0
Levee=-1,156.28,9.43,0,,,,
Bank Sta=121.4,630.25
XS Rating Curve= 0 ,0
Vertical n Elevations= 5
     140     200     400     700    2000
Vertical n for Station=0
     .22     .22     .22     .22     .22
Vertical n for Station=121.4
      .2     .16     .13    .115      .1
Vertical n for Station=630.25
     .22     .22     .22     .22     .22
Vertical n Flow=-1
Exp/Cntr=0.3,0.1

Type RM Length L Ch R = 1 ,344.64  ,1162.795,1162.795,1162.795
BEGIN DESCRIPTION:
XS13
END DESCRIPTION:
Node Name=XS13
XS GIS Cut Line= 2
 459106.813404883186782.88367002 459346.807304883186839.11017002
#Sta/Elev= 30
       0 21.584778.52126 15.1629111.2384 13.2809238.3331    9.19320.1031    7.86
329.7631    7.05337.0331    4.95350.6131    5.17359.5831    7.05367.4031    7.71
415.4631    7.45435.0631    7.68444.3531    8.59449.3831    7.57451.8831    6.29
481.1331     4.6581.4931    5.21596.0931    2.78608.1031    1.85623.3431    4.97
653.9831    5.41689.6831    4.54881.0031    5.14900.5831    6.37910.3031    8.58
980.1931    11.4999.4831   12.94 1066.58 20.89951073.124  20.2351118.928 20.6697
#Mann= 3 , 0 , 0
       0       0       0320.1031       0       0910.3031       0       0
Levee=-1,444.3531,8.59,0,,,,
Bank Sta=320.1031,910.3031
XS Rating Curve= 0 ,0
Vertical n Elevations= 5
     140     200     400     700    2000
Vertical n for Station=0
     .22     .22     .22     .22     .22
Vertical n for Station=320.1031
      .2     .16     .13    .115      .1
Vertical n for Station=910.3031
     .22     .22     .22     .22     .22
Vertical n Flow=-1
Exp/Cntr=0.3,0.1

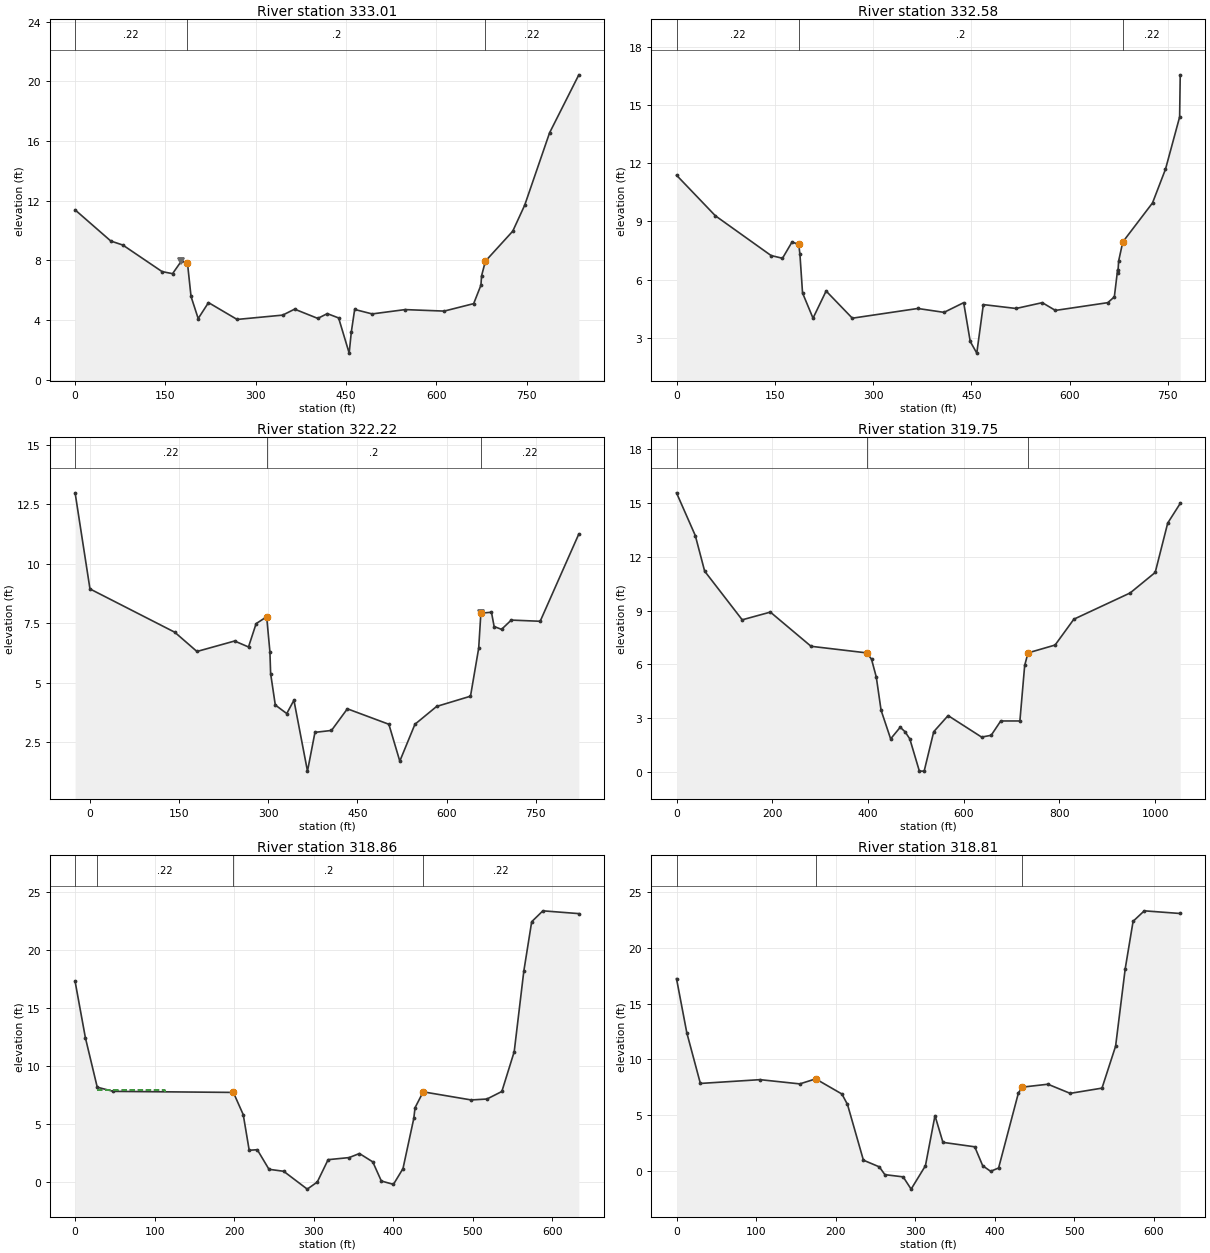
Type RM Length L Ch R = 1 ,333.01  ,43.1102,43.1102,43.1102
BEGIN DESCRIPTION:
XS12
END DESCRIPTION:
Node Name=XS12
XS GIS Cut Line= 2
 459017.819704883187123.44757002459264.5624048793187183.65137002
#Sta/Elev= 30
       0   11.38   59.29    9.29   79.28    9.02  144.39    7.24   161.8     7.1
  176.38    7.94  186.59    7.81   192.5    5.57  204.39    4.09  221.48    5.16
  268.97    4.03  344.66    4.32  364.51    4.72  402.91     4.1  418.79    4.42
  437.56    4.13  455.07    1.77  458.61    3.18   464.2     4.7  493.25     4.4
  547.84    4.69  612.88    4.59  661.78    5.09  673.87    6.33   674.9    6.95
  681.28    7.94  726.65    9.95  746.48   11.69  787.83   16.55   836.4   20.44
#Mann= 3 , 0 , 0
       0     .22       0  186.59      .2       0  681.28     .22       0
Levee=-1,176.38,7.94,0,,,,
Bank Sta=186.59,681.28
XS Rating Curve= 0 ,0
Vertical n Elevations= 5
     140     200     400     700    2000
Vertical n for Station=0
     .22     .22     .22     .22     .22
Vertical n for Station=186.59
      .2     .16     .13    .115      .1
Vertical n for Station=681.28
     .22     .22     .22     .22     .22
Vertical n Flow=-1
Exp/Cntr=0.3,0.1

Type RM Length L Ch R = 1 ,332.58  ,1035.531,1035.531,1035.531
BEGIN DESCRIPTION:
MFL_Flats
END DESCRIPTION:
Node Name=MFL_Flats
XS GIS Cut Line= 3
459020.8642946283187142.28128962 459030.098904883187144.19097002
459236.797342329 3187186.9353788
#Sta/Elev= 30
       0   11.38   59.29    9.29  144.39    7.24   161.8     7.1  176.38    7.94
  186.59    7.81   188.4   7.313   192.4   5.313   208.4   4.013   228.4   5.413
   268.4   4.013   368.4   4.513   408.4   4.313   438.4   4.813   448.4   2.813
   458.4   2.213   468.4   4.713   518.4   4.513   558.4   4.813   578.4   4.413
   658.4   4.813   668.4   5.113   673.4   6.513  673.87    6.33   674.9    6.95
  681.28    7.94  726.65    9.95  746.48   11.69  768.06   14.38  768.97   16.55
#Mann= 3 , 0 , 0
       0     .22       0  186.59      .2       0  681.28     .22       0
Bank Sta=186.59,681.28
XS Rating Curve= 0 ,0
Vertical n Elevations= 5
     140     200     400     700    2000
Vertical n for Station=0
     .22     .22     .22     .22     .22
Vertical n for Station=186.59
      .2     .16     .13    .115      .1
Vertical n for Station=681.28
     .22     .22     .22     .22     .22
Vertical n Flow=-1
Exp/Cntr=0.3,0.1

Type RM Length L Ch R = 1 ,322.22  ,247.605,247.605,247.605
BEGIN DESCRIPTION:
XS11
END DESCRIPTION:
Node Name=XS11
XS GIS Cut Line= 2
 458963.185504883187436.30517002459201.5125048793187510.18837002
#Sta/Elev= 30
     -25   12.98       0    8.94  142.61    7.12  179.95    6.31  243.27    6.75
  266.67     6.5  279.47    7.48  297.23    7.77  302.67     6.3  303.89    5.38
  311.74    4.06  331.01     3.7  343.07    4.26  365.88    1.28  378.46    2.91
  406.25    2.99  432.97     3.9  502.78    3.25  521.17     1.7  546.64    3.25
  583.13       4  640.08    4.43  653.87    6.45  657.53    7.92  675.35    7.96
  679.82    7.36  692.29    7.24  708.66    7.63  757.29    7.58   822.3   11.25
#Mann= 3 , 0 , 0
     -25     .22       0  297.23      .2       0  657.53     .22       0
Levee=0,,,-1,657.53,7.92,,
#XS Ineff= 1 ,-1
   79.45  297.23     7.7
Permanent Ineff=
       F
Bank Sta=297.23,657.53
XS Rating Curve= 0 ,0
Vertical n Elevations= 5
     140     200     400     700    2000
Vertical n for Station=-25
     .22     .22     .22     .22     .22
Vertical n for Station=297.23
      .2     .16     .13    .115      .1
Vertical n for Station=657.53
     .22     .22     .22     .22     .22
Vertical n Flow=-1
Exp/Cntr=0.3,0.1

Type RM Length L Ch R = 1 ,319.75  ,88.8451,88.8451,88.8451
BEGIN DESCRIPTION:
MFL_SR46E
END DESCRIPTION:
Node Name=MFL_SR46E
XS GIS Cut Line= 2
459015.1934048793187548.55247002 459144.574904883187545.90667002
#Sta/Elev= 30
       0 15.574539.21763 13.191758.82645 11.2012137.2617  8.4857196.0882  8.9167
281.0597  7.0082397.3756    6.64407.3756    6.29417.3756    5.29427.3756    3.44
447.3756    1.84467.3756    2.49477.3756    2.24487.3756    1.84507.3756     .04
517.3755     .04537.3755    2.24567.3755    3.14637.3755    1.94657.3755    2.04
677.3755    2.84717.3755    2.84727.3755    5.94734.3755    6.64790.8889  7.0777
830.1066    8.52947.7595  9.9863 1000.05 11.12971026.195 13.8866 1052.34 14.9834
#Mann= 3 , 0 , 0
       0       0       0397.3756       0       0734.3755       0       0
Bank Sta=397.3756,734.3755
XS Rating Curve= 0 ,0
Vertical n Elevations= 5
     140     200     400     700    2000
Vertical n for Station=0
     .22     .22     .22     .22     .22
Vertical n for Station=397.3756
      .2     .16     .13    .115      .1
Vertical n for Station=734.3755
     .22     .22     .22     .22     .22
Vertical n Flow=-1
Exp/Cntr=0.3,0.1

Type RM Length L Ch R = 1 ,318.86  ,5.4462,5.4462,5.4462
BEGIN DESCRIPTION:
XS10
END DESCRIPTION:
Node Name=XS10
XS GIS Cut Line= 2
458974.1189048793187575.68317002 459166.370904883187566.64927002
#Sta/Elev= 30
       0   17.26   12.98   12.39   27.84    8.14   48.09    7.78     199    7.69
  211.42    5.77  218.91     2.7  229.06    2.75  243.78    1.06  262.24     .89
   291.9    -.65  304.49    -.04  318.13    1.89  344.52    2.07  357.51    2.42
  374.28     1.7  385.06     .05  400.25    -.24  412.27    1.12  425.87    5.45
  427.42    6.37  437.69    7.74   498.1    7.04  517.84    7.12  536.57    7.77
  552.12    11.2  564.22   18.16  574.11   22.41  588.18   23.35  633.37   23.11
#Mann= 4 , 0 , 0
       0     .22       0   27.84     .22       0     199      .2       0
  437.69     .22       0
#XS Ineff= 1 ,-1
   27.84  112.66     7.9
Permanent Ineff=
       F
Bank Sta=199,437.69
XS Rating Curve= 0 ,0
Vertical n Elevations= 5
     140     200     400     700    2000
Vertical n for Station=0
     .22     .22     .22     .22     .22
Vertical n for Station=199
      .2     .16     .13    .115      .1
Vertical n for Station=457.24
     .22     .22     .22     .22     .22
Vertical n Flow=-1
Exp/Cntr=0.5,0.3

Type RM Length L Ch R = 1 ,318.81  ,61.1549,61.1549,61.1549
BEGIN DESCRIPTION:
MFL_SR46B
END DESCRIPTION:
Node Name=MFL_SR46B
XS GIS Cut Line= 2
 458972.529304883187577.41857002459149.2051048793187568.68737002
#Sta/Elev= 30
       0   17.26   12.98   12.39      30    7.85     105    8.19     155    7.81
     175    8.26     208     6.9     215    5.96     235     .96     255     .36
     262    -.34     285    -.54     295   -1.64     313     .46     325    4.96
     335    2.56     375    2.16     385     .46     395    -.04     405     .26
     430    7.02     435    7.52     467    7.78     495    6.96     535    7.43
  552.12    11.2  564.22   18.16  574.11   22.41  588.18   23.35  633.37   23.11
#Mann= 3 , 0 , 0
       0       0       0     175       0       0     435       0       0
Bank Sta=175,435
XS Rating Curve= 0 ,0
Vertical n Elevations= 5
     140     200     400     700    2000
Vertical n for Station=0
     .22     .22     .22     .22     .22
Vertical n for Station=175
      .2     .16     .13    .115      .1
Vertical n for Station=435
     .22     .22     .22     .22     .22
Vertical n Flow=-1
Exp/Cntr=0.5,0.3